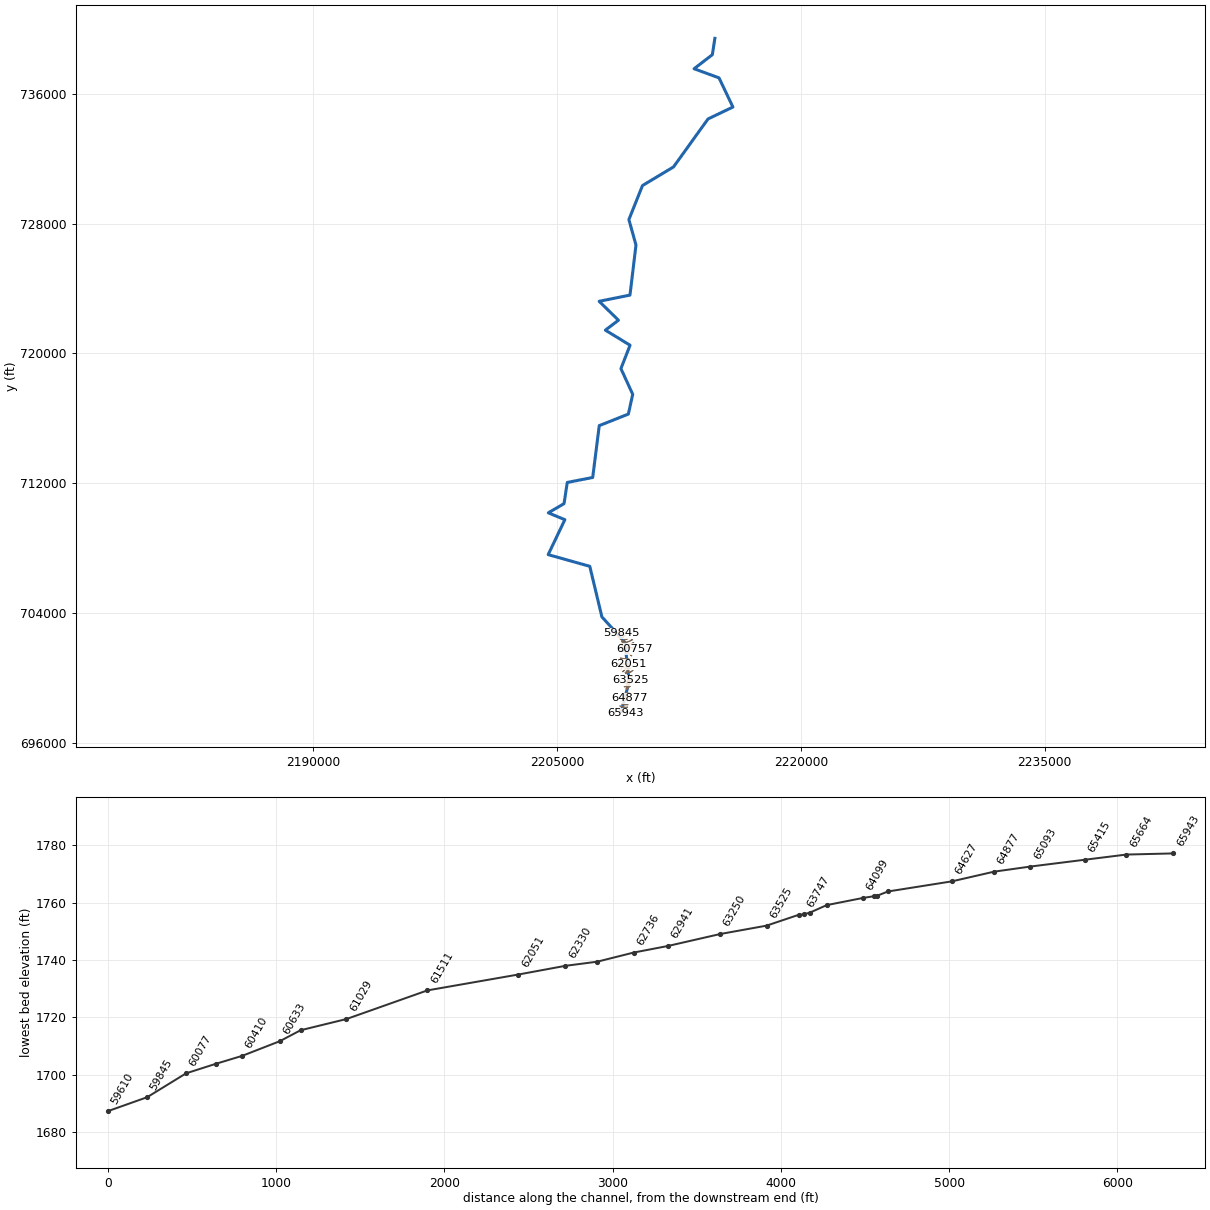
--- SANDRN1.prj (project) ---

Proj Title=SANDRN1
Current Plan=p01
Default Exp/Contr=0,0
English Units
Geom File=g01
Flow File=f01
Plan File=p01
BEGIN DESCRIPTION:
---------- MODELED AS PART OF WVEMD CTP PROGRAM, 2023----------
Stream Name: Sand Run
Flood Zone:  AFH
Upshur County, WV
HEC-RAS Version: RAS 6.3
Vertical Datum: NAVD88
Projection: NAD 1983 StatePlane West Virginia S FIPS 4702 (US Feet)
Terrain: 1-meter LIDAR (FEMA Region III 3DEP collected 2016-2018)
Land Use: 2019 NLCD
Hydrologic Method:
WV SIR2010-5033 regression equations
Additional Model Notes:
None
END DESCRIPTION:
DSS Export Rating Curves= 0
DSS Export Rating Curve Sorted= 0
DSS Export Volume Flow Curves= 0
DXF OffsetX= 0
DXF OffsetY= 0
DXF ScaleX= 0
DXF ScaleY= 0

--- SANDRN1.p01 (plan) ---

Plan Title=Floodplain
Program Version=6.30
Short Identifier=Floodplain
Geom File=g01
Flow File=f01
Subcritical Flow
K Sum by GR= 0
Std Step Tol= 0.01
Critical Tol= 0.01
Num of Std Step Trials= 20
Max Error Tol= 0.3
Flow Tol Ratio= 0.001
Split Flow NTrial= 30
Split Flow Tol= 0.02
Split Flow Ratio= 0.02
Log Output Level= 0
Friction Slope Method= 1
Unsteady Friction Slope Method= 2
Unsteady Bridges Friction Slope Method= 1
Parabolic Critical Depth
Global Vel Dist= 0 , 0 , 0
Global Log Level= 0
CheckData=False
Encroach Param=-1 ,0,0, 0
Mapping Interval=1HOUR
Computation Time Step Use Courant=        0
Computation Time Step Use Time Series=    0
Computation Time Step Count To Double=0
Computation Time Step Max Doubling=0
Computation Time Step Max Halving=0
Computation Time Step Residence Courant=0
Run HTab= 0
Run UNet= 0
Run Sediment= 0
Run PostProcess= 0
Run WQNet= 0
Run RASMapper=-1
UNET Theta= 0
UNET Theta Warmup= 0
UNET ZTol= 0
UNET ZSATol= 0
UNET MxIter= 0
UNET Max Iter WO Improvement= 0
UNET MaxInSteps= 0
UNET DtIC= 0
UNET DtMin= 0
UNET MaxCRTS= 0
UNET WFStab= 0
UNET SFStab= 0
UNET WFX= 1
UNET SFX= 1
UNET Gravity=32.17405
UNET 1D Methodology=Finite Difference
UNET DSS MLevel= 1
UNET Pardiso=0
UNET DZMax Abort= 0
UNET Use Existing IB Tables= 0
UNET Froude Reduction=False
UNET Froude Limit= 0
UNET Froude Power= 0
UNET D1 Cores= 0
UNET WindReference=Eulerian
UNET WindDragFormulation=Hsu (1988)
UNET D2 Coriolis=0
UNET D2 Cores= 0
UNET D2 Theta= 1
UNET D2 Theta Warmup= 1
UNET D2 Z Tol= 0.01
UNET D2 Volume Tol= 0.01
UNET D2 Max Iterations= 20
UNET D2 Equation= 0
UNET D2 RampUpFraction=0.1
UNET D2 TimeSlices= 1
UNET D2 Turbulence Formulation=Non-Conservative (original)
UNET D2 Eddy Viscosity=0.3
UNET D2 Transverse Eddy Viscosity=0.1
UNET D2 Smagorinsky Mixing=0
UNET D2 BCVolumeCheck=0
UNET D2 Cores=0
UNET D2 SolverType=PARDISO (Direct)
UNET D2 Minimum Iterations= 3
UNET D2 Maximum Iterations= 30
UNET D2 Restart Number= 10
UNET D2 Relaxation Coeff=1.3
UNET D2 SOR Precondition Iterations= 10
UNET D2 ILUT Maximum Fill= 8
UNET D2 ILUT Tolerance=1E-08
UNET D2 Convergence Tolerance=0.00001
UNET D1D2 MaxIter= 0
UNET D1D2 ZTol=0.01
UNET D1D2 QTol=0.1
UNET D1D2 MinQTol=1
Write IC File= 0
Write IC File at Fixed DateTime=0
Write IC File at Sim End=0
Echo Input=False
Echo Parameters=False
Echo Output=False
Write Detailed= 0
HDF Write Warmup=0
HDF Write Time Slices=0
HDF Flush=0
HDF Compression= 1
HDF Chunk Size= 1
HDF Spatial Parts= 1
HDF Use Max Rows=0
HDF Fixed Rows= 1
Calibration Method= 0
Calibration Iterations= 20
Calibration Max Change=0.05
Calibration Tolerance=0.2
Calibration Maximum=1.5
Calibration Minimum=0.5
Calibration Optimization Method= 1
WQ AD Non Conservative
WQ ULTIMATE=-1
WQ Max Comp Step=1HOUR
WQ Output Interval=15MIN
WQ Output Selected Increments= 0
WQ Output face flow=0
WQ Output face velocity=0
WQ Output face area=0
WQ Output face dispersion=0
WQ Output cell volume=0
WQ Output cell surface area=0
WQ Output cell continuity=0
WQ Output cumulative cell continuity=0
WQ Output face conc=0
WQ Output face dconc_dx=0
WQ Output face courant=0
WQ Output face peclet=0
WQ Output face adv mass=0
WQ Output face disp mass=0
WQ Output cell mass=0
WQ Output cell source sink temp=0
WQ Output nsm pathways=0
WQ Output nsm derived pathways=0
WQ Create Restart=0
WQ Fixed Restart=0
WQ System Summary=0
WQ Write To DSS=0
Sorting and Armoring Iterations= 10
XS Update Threshold= 0.02
Bed Roughness Predictor= 0
Hydraulics Update Threshold= 0.02
Energy Slope Method= 1
Volume Change Method= 1
Sediment Retention Method= 0
Sediment TS Multiplier= 1
Warm Up Method= 0
XS Weighting Method= 0
Number of US Weighted Cross Sections= 1
Number of DS Weighted Cross Sections= 1
Upstream XS Weight=0
Main XS Weight=1
Downstream XS Weight=0
Number of DS XS's Weighted with US Boundary= 1
Upstream Boundary Weight= 1
Weight of XSs Associated with US Boundary= 0
Number of US XS's Weighted with DS Boundary= 1
Downstream Boundary Weight= 0.5
Weight of XSs Associated with DS Boundary= 0.5
Percentile Method= 0
Sediment Output Level= 3
Mass or Volume Output= 0
Output Increment Type= 1
Profile and TS Output Increment= 1
Transport Output Increment 1
XS Output Flag= 0
XS Output Increment= 10
Read HDF5 Sediment Hotstart= 0
Sediment Hotstart Type= 0
Write Gradation File= 0
Read Gradation Hotstart= 0
Write HDF5 File= 1
Write Binary Output= 1
Write DSS Sediment File= 0
DSS Sediment Output Type= 1
SV Curve= 0
Specific Gage Flag= 0
Subcell Erosion Methods= 0
Subcell Deposition Methods= 0
Advection Scheme= 1
Matrix Solver= 0
Implicit Weighting Factor= 1
Maximum Outer Loop Convergence Iterations= 5
Convergence Maximum Absolute= 0.001
Convergence RMSE= 0.0001
Grain Fractions Max Abs Error= 0.001
Max Subgrid Regions= 1
Max Subgrid Length Scale= 3.402823E+38
Initial Layer Thickness= 3.402823E+38
Min Layer Thickness= 3.402823E+38
Max Layer Thickness= 3.402823E+38
Number of Layers= 5

--- SANDRN1.f01 (steady flow) ---

Flow Title=Flows
Program Version=6.31
Number of Profiles= 1
Profile Names=01pct
River Rch & RM=SANDRN1,Main,65943
     453
River Rch & RM=SANDRN1,Main,63250
     555
River Rch & RM=SANDRN1,Main,58076
     664
River Rch & RM=SANDRN1,Main,56911
    1140
River Rch & RM=SANDRN1,Main,54529
    1980
River Rch & RM=SANDRN1,Main,50871
    2350
River Rch & RM=SANDRN1,Main,44110
    2650
River Rch & RM=SANDRN1,Main,35675
    3530
River Rch & RM=SANDRN1,Main,28433
    3940
River Rch & RM=SANDRN1,Main,12780
    5330
Boundary for River Rch & Prof#=SANDRN1,Main            , 1
Up Type= 0
Dn Type= 3
Dn Slope=0.00278
DSS Import GetInterval= 0
DSS Import GetPeak= 0
DSS Import FillOption= 0

--- SANDRN1.g01 (geometry) ---

Geom Title=Geometry
Program Version=6.31

River Reach=SANDRN1         ,Main
Reach XY= 30
2208954.00400001697970.7780000122209434.10100003699801.569000006
2209171.63200001 702214.01700002     2207758.469703778.560000002
2207012.23900002706893.167999998      2204452.36707613.070000008
2205478.68700001709763.7919999962204460.54399998710187.258000001
     2205428.208710751.6009999962205626.57600001712057.224000007
2207191.69200005712362.5610000192207594.75400001715554.403999999
     2209386.941716267.4679999952209654.56199999717481.976000011
     2208929.108719067.3240000012209491.01900001      720506.184
2207971.40300001721434.2709999982208777.55499999722045.832000002
2207588.02900003723210.7480000112209485.78200002723592.090000004
     2209854.619726673.6449999962209418.64800002728241.851999998
2210256.07799998730337.5730000142212164.64800003731484.346000001
2214285.92400004734437.3000000122215818.50300002 735171.71100001
2214965.07700004      736966.5882213430.40900001737530.016000003
2214553.71600002738394.861000016     2214709.475      739401.843

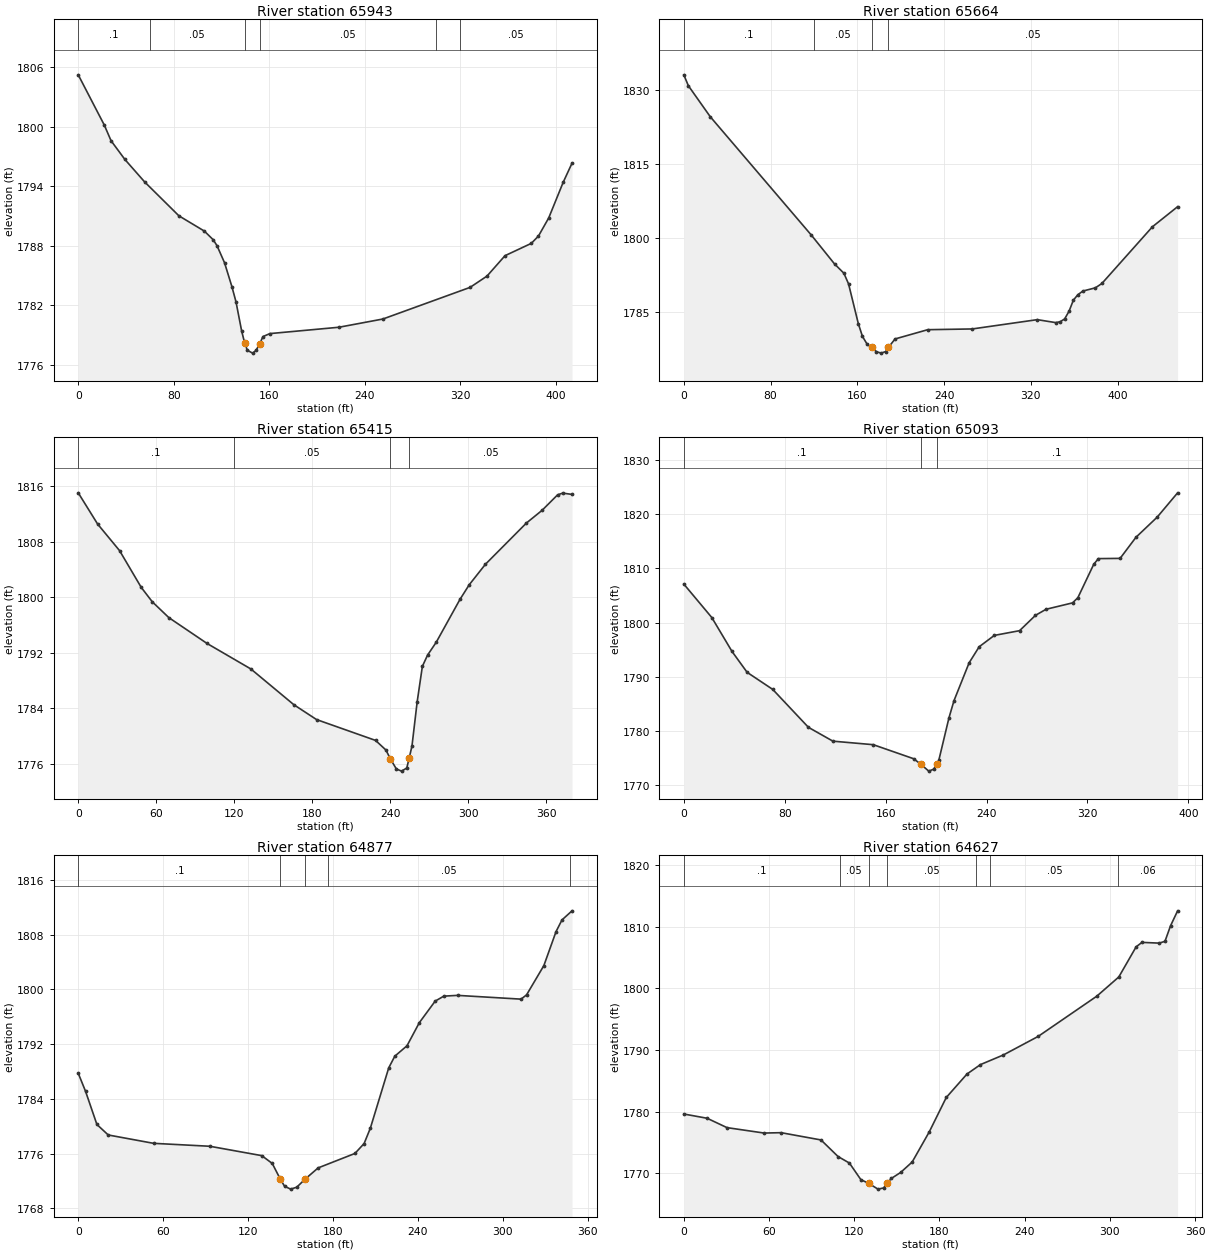
Type RM Length L Ch R = 1 ,65943   ,278,279,280.3
XS GIS Cut Line= 2
2208845.62172589698064.7491517272209191.69422643697838.528599428
#Sta/Elev= 30
       0 1805.25    21.8 1800.19    27.5  1798.6    39.1 1796.71    55.6 1794.45
    84.3 1791.03   105.6 1789.49     113 1788.62   116.2 1788.02   122.5  1786.3
   128.7 1783.88   132.1 1782.36   136.9 1779.38  139.34 1778.22   141.6 1777.47
     146 1777.18   148.9 1777.45   151.8 1778.09   154.7 1778.85   160.5 1779.15
   218.3 1779.79   255.1 1780.62   328.1 1783.81   342.3 1784.95   357.4 1787.01
   379.4 1788.25   385.4 1788.99     394 1790.82   406.1 1794.41   413.5 1796.34
#Mann= 6 ,-1,0
       0      .1       0      60     .05       0  139.34    .045       0
   151.8     .05       0     300     .06       0     320     .05       0
Bank Sta=139.34,151.8
XS Rating Curve= 0 ,0
Exp/Cntr(USF)=0,0
Exp/Cntr=0.3,0.1

Type RM Length L Ch R = 1 ,65664   ,241.1,249.2,251
XS GIS Cut Line= 4
2208880.07916101 698287.97340532 2208998.4329599698268.497463731
2209175.21458355698199.5825934942209319.03692143698222.054833789
#Sta/Elev= 30
       0 1833.07     4.2 1830.86    24.4 1824.59   117.7 1800.62     139 1794.81
   147.6 1792.94   151.9 1790.78   160.9 1782.74   164.7 1780.17     169 1778.59
   173.1 1777.93   177.6 1777.07   181.9 1776.78   186.2  1777.1   188.7 1777.96
   194.8 1779.65   224.9 1781.52   265.9 1781.67   325.9 1783.55     343 1782.95
   347.1 1783.14   351.1 1783.69   355.2 1785.25   359.2  1787.5   363.3 1788.59
   367.9 1789.33   379.5 1789.99   385.5 1790.87   432.1 1802.34   455.3  1806.4
#Mann= 4 ,-1,0
       0      .1       0  119.95     .05       0   173.1    .045       0
   188.7     .05       0
Bank Sta=173.1,188.7
XS Rating Curve= 0 ,0
Exp/Cntr(USF)=0,0
Exp/Cntr=0.3,0.1

Type RM Length L Ch R = 1 ,65415   ,321.8,322,321.2
XS GIS Cut Line= 3
2208977.97187858698440.2129656592209178.73950073 698374.48547031
 2209347.2408979 698378.07060642
#Sta/Elev= 30
       0 1815.01    14.9 1810.52    31.8 1806.69    48.5 1801.39      57 1799.32
    69.7 1797.05    99.1 1793.33   132.8 1789.66   165.9 1784.51   183.3 1782.38
   228.7 1779.38   236.7 1777.99  240.04 1776.74   244.7 1775.27   248.7 1774.96
   252.7 1775.41   254.5 1776.79   256.7 1778.58   260.7 1784.94   264.7 1790.04
   268.7 1791.66   275.4 1793.52   293.6 1799.67   300.7 1801.77   313.2 1804.73
   344.7 1810.66   356.7 1812.48   368.7 1814.72   372.7 1814.97   379.8 1814.78
#Mann= 4 ,-1,0
       0      .1       0     120     .05       0  240.04    .045       0
   254.5     .05       0
Bank Sta=240.04,254.5
XS Rating Curve= 0 ,0
Exp/Cntr(USF)=0,0
Exp/Cntr=0.3,0.1

Type RM Length L Ch R = 1 ,65093   ,220.2,215.4,209.8
XS GIS Cut Line= 3
 2209057.9608204698640.739169521 2209324.9310351698643.435838357
2209443.58446386698605.682474662
#Sta/Elev= 30
       0 1807.11    22.2 1800.93    38.2 1794.68    50.2 1790.82    70.5 1787.67
    98.8 1780.67   118.2 1778.12   150.2 1777.47   182.2 1774.88   187.7  1773.9
   194.2 1772.59   198.2 1772.96   200.41773.873   202.2 1774.62   210.2 1782.41
   214.2 1785.59   226.2 1792.58   234.2 1795.55   246.2 1797.64   266.2 1798.51
   278.8 1801.34   287.2 1802.46   308.2 1803.64   312.4 1804.59     325 1810.76
   328.7 1811.81   345.9 1811.85   358.5 1815.75   375.3 1819.46   391.5 1823.95
#Mann= 3 ,-1,0
       0      .1       0   187.7    .045       0   200.4      .1       0
Bank Sta=187.7,200.4
XS Rating Curve= 0 ,0
Exp/Cntr(USF)=0,0
Exp/Cntr=0.3,0.1

Type RM Length L Ch R = 1 ,64877   ,244.4,250.4,255.6
XS GIS Cut Line= 4
2209126.98213117698874.1751749072209213.26205056698870.898722272
2209371.62392792698805.3696695742209458.99599818698779.158048494
#Sta/Elev= 30
       0 1787.74     5.2 1785.08    13.2 1780.25    21.2 1778.72    53.2  1777.5
      93 1777.07   129.7  1775.7   137.1 1774.56  142.83 1772.25   145.8 1771.23
   150.1 1770.81   154.4 1771.09   160.3 1772.27   169.5 1773.91   195.5 1776.02
     202 1777.47   206.4 1779.71   219.4 1788.53   223.7 1790.23   232.3 1791.75
     241 1795.12   252.2 1798.27   258.3    1799     268 1799.11   312.9 1798.56
   316.8 1799.19     329 1803.46   337.6 1808.42   341.8 1810.13   348.9 1811.46
#Mann= 5 ,-1,0
       0      .1       0  142.83    .045       0   160.3      .1       0
  176.34     .05       0  347.73      .1       0
Bank Sta=142.83,160.3
XS Rating Curve= 0 ,0
Exp/Cntr(USF)=0,0
Exp/Cntr=0.3,0.1

Type RM Length L Ch R = 1 ,64627   ,373.2,380.6,385.8
XS GIS Cut Line= 3
2209183.86669564699060.9184929892209389.19106077699076.208605286
2209528.98637319699052.181285963
#Sta/Elev= 30
       0 1779.62    16.4 1778.93    30.4 1777.41    56.5 1776.53    68.5 1776.59
    96.6 1775.41   108.6 1772.72   116.6 1771.66   124.7 1768.96   130.1 1768.38
   136.7 1767.43   140.7 1767.62   143.1 1768.37   146.1 1769.16   152.7 1770.14
   160.8 1771.83   172.8 1776.71   184.8  1782.3   199.4 1786.11   208.9 1787.64
     225  1789.2   249.5 1792.21   290.8 1798.74   306.3 1801.86   318.5 1806.75
   322.6 1807.47   334.7 1807.35   338.8 1807.64   342.7 1810.15   347.7 1812.59
#Mann= 7 ,-1,0
       0      .1       0     110     .05       0   130.1    .045       0
   143.1     .05       0  205.89      .1       0  215.89     .05       0
  305.89     .06       0
Bank Sta=130.1,143.1
XS Rating Curve= 0 ,0
Exp/Cntr(USF)=0,0
Exp/Cntr=0.3,0.1

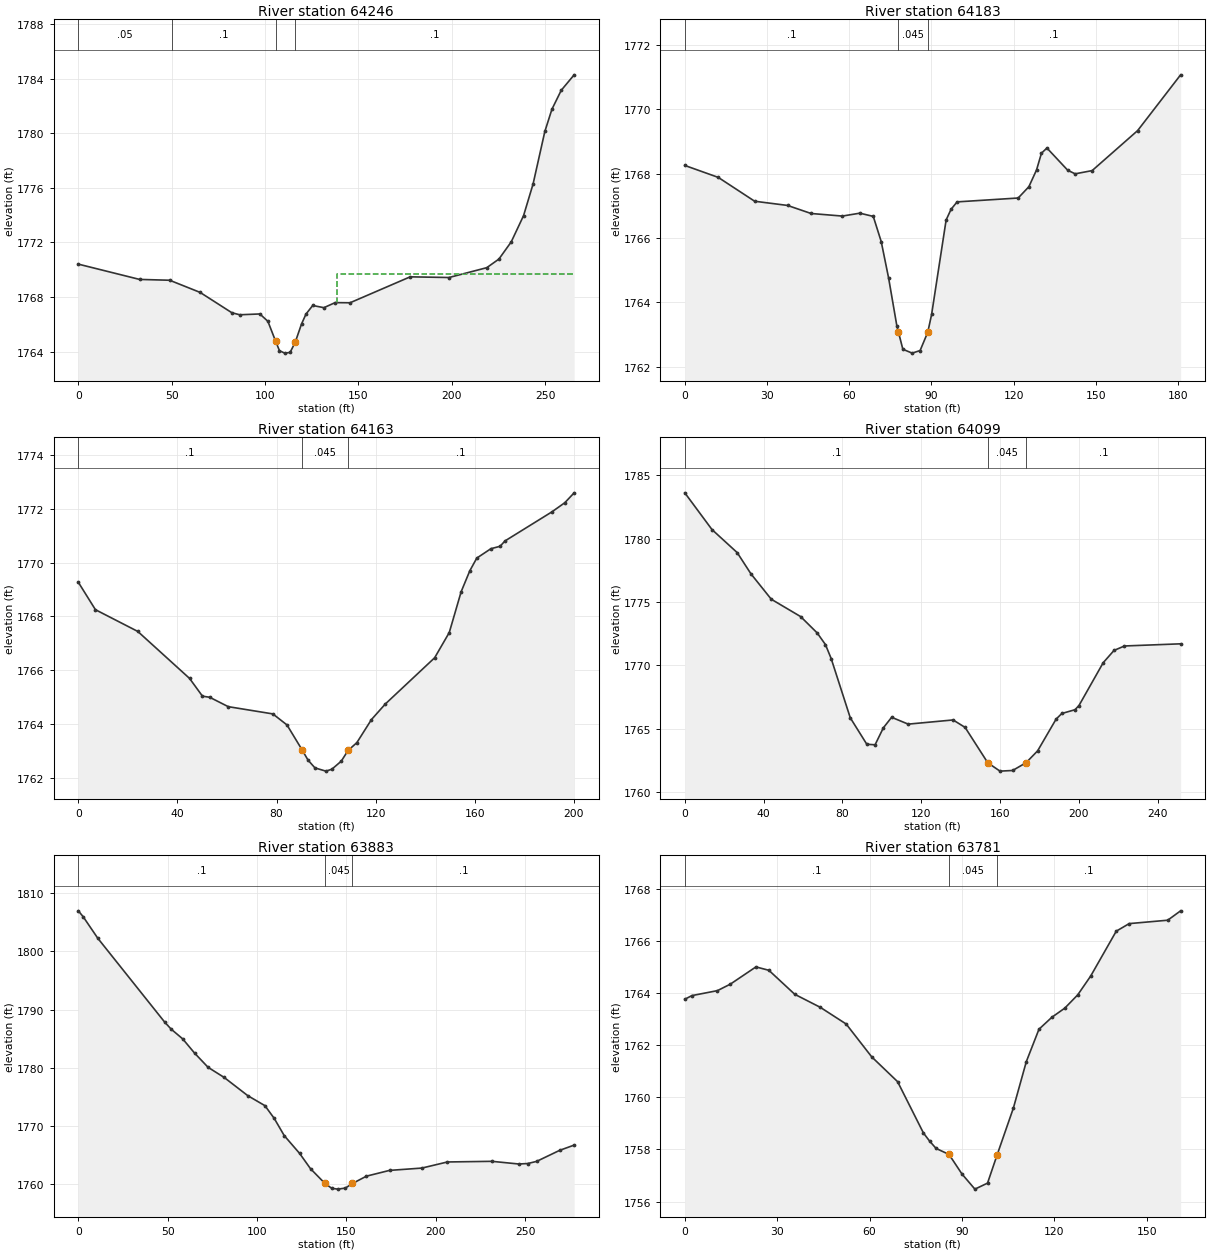
Type RM Length L Ch R = 1 ,64246   ,63.1,62.8,62.7
XS GIS Cut Line= 3
2209287.77203017699341.4864696952209423.20190632699462.728454057
2209489.62703604699513.675883656
#Sta/Elev= 30
       0 1770.41    32.8 1769.29    48.9 1769.23    65.2 1768.34    82.2 1766.85
    86.4  1766.7    97.2 1766.76   101.5 1766.22  105.651764.758   107.7 1764.07
   110.5 1763.89   113.4 1763.94   116.2 1764.71   119.5 1766.02   121.9 1766.75
   125.5 1767.38   131.5 1767.22   137.5 1767.59   145.5 1767.58   177.7 1769.48
   198.5 1769.43   218.7 1770.15   225.2 1770.78   231.8 1772.04   238.4 1773.96
   243.5 1776.28   249.8 1780.13   253.6 1781.76   258.6 1783.15   265.5 1784.28
#Mann= 4 ,-1,0
       0     .05       0      50      .1       0  105.65    .045       0
   116.2      .1       0
#XS Ineff= 2 , 0
                          138.38          1769.7
Permanent Ineff=
       F       F
Bank Sta=105.65,116.2
XS Rating Curve= 0 ,0
Exp/Cntr(USF)=0,0
Exp/Cntr=0.3,0.1

Type RM Length L Ch R = 1 ,64183   ,19.8,20.2,21.5
XS GIS Cut Line= 3
2209288.99405416699400.9781184992209301.37904512699438.133091378
2209409.30539491699530.135881364
#Sta/Elev= 30
       0 1768.25    12.2 1767.88    25.5 1767.14    37.5 1767.01    46.1 1766.76
    57.5 1766.68    63.9 1766.77    68.8 1766.67    71.7 1765.89    74.4 1764.76
    77.4 1763.28   77.971763.091    79.6 1762.55      83 1762.43    85.9 1762.51
    88.7 1763.08    90.1 1763.63    95.4 1766.56    97.2 1766.89    99.4 1767.12
   121.7 1767.24   125.6 1767.59   128.4 1768.11   130.2 1768.63   132.2 1768.79
   139.8  1768.1   142.5 1767.99   148.7 1768.09   165.3 1769.33     181 1771.06
#Mann= 3 ,-1,0
       0      .1       0   77.97    .045       0    88.7      .1       0
Bank Sta=77.97,88.7
XS Rating Curve= 0 ,0
Exp/Cntr(USF)=0,0
Exp/Cntr=0.3,0.1

Type RM Length L Ch R = 1 ,64163   ,66.3,64.7,62.8
XS GIS Cut Line= 3
2209264.22407224699410.709182824 2209276.6090632699443.440944646
2209403.11289943699549.598010015
#Sta/Elev= 30
       0 1769.27     6.9 1768.25      24 1767.44    44.9 1765.69    50.1 1765.03
      53 1764.99    60.5 1764.64    78.5 1764.37    84.2 1763.96    90.31763.032
    92.7 1762.65    95.5 1762.36    99.9 1762.24   102.3 1762.31   106.1 1762.61
  108.861763.009   112.4  1763.3   118.3 1764.16   123.9 1764.74   143.8 1766.46
   149.7  1767.4   154.5 1768.92     158  1769.7   160.8 1770.17   166.5 1770.52
   170.2 1770.61   172.2 1770.81   191.1 1771.89   196.3 1772.23   200.1  1772.6
#Mann= 3 ,-1,0
       0      .1       0    90.3    .045       0  108.86      .1       0
Bank Sta=90.3,108.86
XS Rating Curve= 0 ,0
Exp/Cntr(USF)=0,0
Exp/Cntr=0.3,0.1

Type RM Length L Ch R = 1 ,64099   ,232.8,215.7,192
XS GIS Cut Line= 3
 2209148.1216369699483.8499704612209263.55948372699520.609508272
2209373.19319298699591.548967208
#Sta/Elev= 30
       0 1783.61    13.8 1780.71    26.6 1778.89    33.6 1777.21    43.9 1775.21
    58.8 1773.84    67.2 1772.55    71.4 1771.63    74.3 1770.53      84 1765.85
    92.4 1763.76    96.6 1763.72   100.8 1765.06     105 1765.89   113.4 1765.35
   136.2 1765.68   142.3 1765.09   153.8  1762.3     160 1761.64   166.4 1761.69
  173.231762.302   179.1 1763.24   188.5 1765.75   191.4 1766.19   198.1 1766.49
   200.1 1766.82   212.4  1770.2   217.9 1771.17   223.2 1771.52   251.7 1771.69
#Mann= 3 ,-1,0
       0      .1       0   153.8    .045       0  173.23      .1       0
Bank Sta=153.8,173.23
XS Rating Curve= 0 ,0
Exp/Cntr(USF)=0,0
Exp/Cntr=0.3,0.1

Type RM Length L Ch R = 1 ,63883   ,105.8,101.4,99.6
XS GIS Cut Line= 4
2209081.58960701699789.0168719782209177.24750643699765.904896277
2209230.53345041699698.4949671512209305.00537211699642.641025875
#Sta/Elev= 30
       0 1806.99     2.7 1805.98    10.9 1802.27    48.4 1787.82      52 1786.63
    58.4 1784.97      65 1782.54    72.6 1780.08    81.6 1778.34    94.8 1775.21
   104.4 1773.49   109.6  1771.3   115.2 1768.34   123.8 1765.28   129.9 1762.65
     138 1760.11   141.8 1759.28   145.2 1759.14   149.4 1759.32  153.35 1760.11
   161.2 1761.37   174.1 1762.36   192.2 1762.76   206.5 1763.81   231.4 1763.92
   246.4 1763.46   251.4 1763.54   256.4 1763.91   269.3 1765.81   277.4 1766.71
#Mann= 3 ,-1,0
       0      .1       0     138    .045       0  153.35      .1       0
Bank Sta=138,153.35
XS Rating Curve= 0 ,0
Exp/Cntr(USF)=0,0
Exp/Cntr=0.3,0.1

Type RM Length L Ch R = 1 ,63781   ,34.6,34.8,35.2
XS GIS Cut Line= 2
2209271.29833378699795.3386856032209317.73143418699641.206588462
#Sta/Elev= 30
       0 1763.76     2.3  1763.9    10.6 1764.09    14.8 1764.34    23.1    1765
    27.3 1764.87    35.7 1763.95      44 1763.45    52.4 1762.81    60.7 1761.55
    69.1  1760.6    77.5 1758.63    79.5 1758.32    81.6 1758.04    85.8 1757.81
      90 1757.06    94.2 1756.48    98.3 1756.71  101.411757.791   106.7 1759.59
   110.9 1761.37     115 1762.61   119.2 1763.07   123.4 1763.42   127.6 1763.93
   131.8 1764.65   140.1 1766.37   144.3 1766.66   156.8 1766.79     161 1767.15
#Mann= 3 ,-1,0
       0      .1       0    85.8    .045       0  101.41      .1       0
Bank Sta=85.8,101.41
XS Rating Curve= 0 ,0
Exp/Cntr(USF)=0,0
Exp/Cntr=0.3,0.1

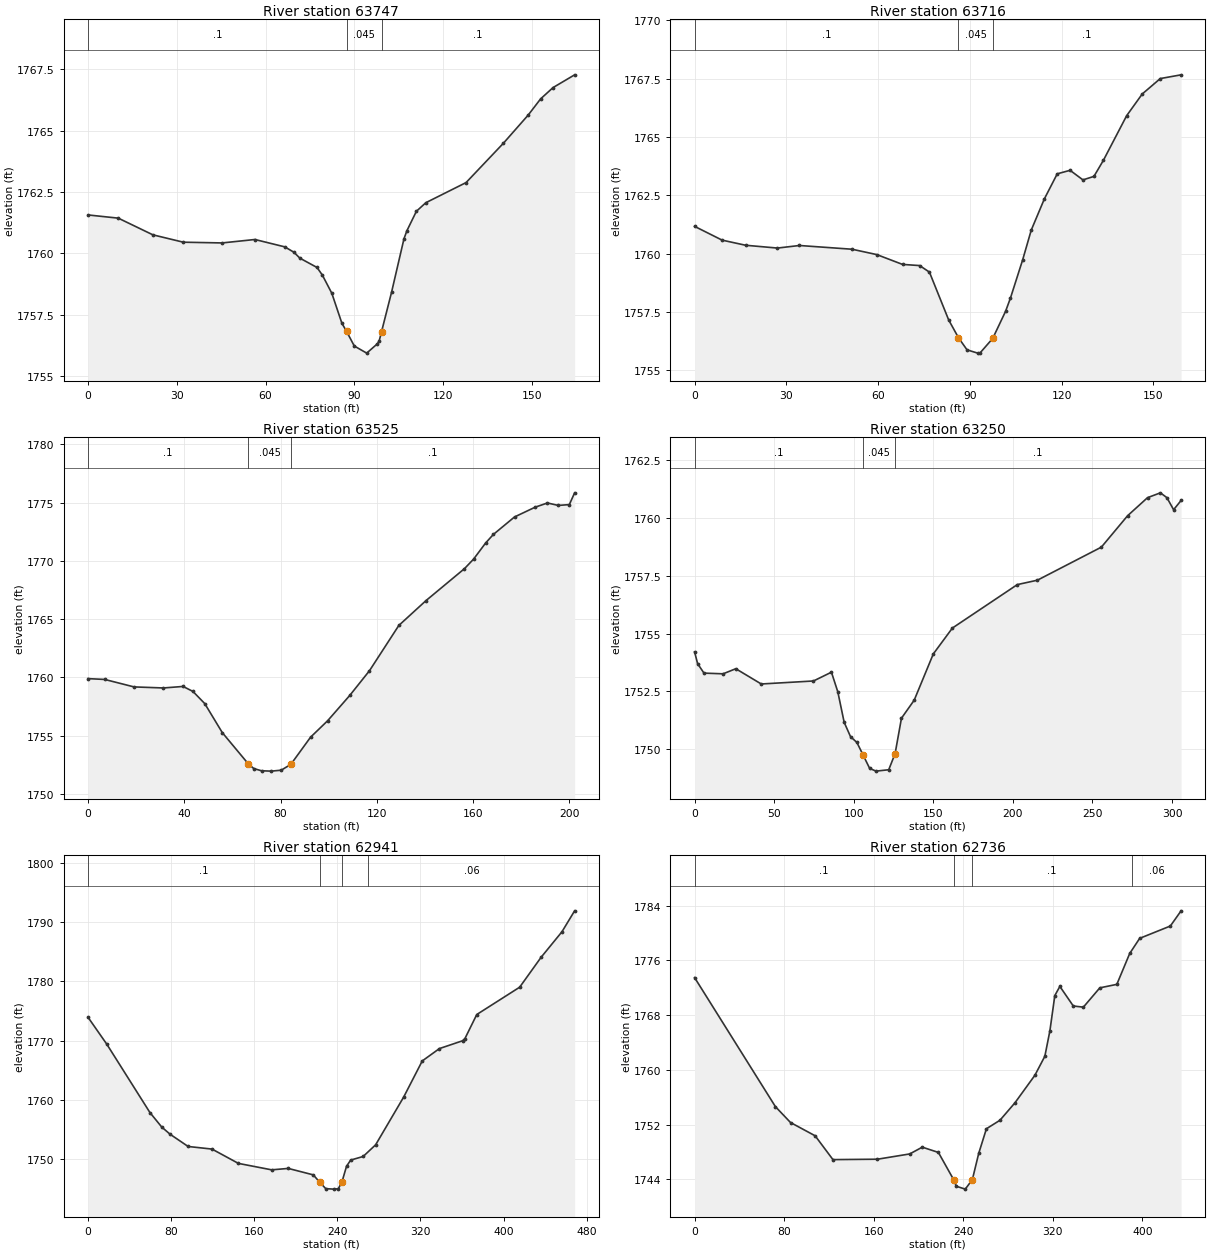
Type RM Length L Ch R = 1 ,63747   ,30.9,31,31.1
XS GIS Cut Line= 2
 2209302.3657418699806.9169743922209352.51349023699650.205260568
#Sta/Elev= 30
       0 1761.57    10.2 1761.44    21.9 1760.76    32.2 1760.46    45.3 1760.43
    56.4 1760.57    66.5 1760.27    69.6 1760.05    71.6 1759.81    77.4 1759.43
    79.2 1759.12    82.4 1758.38    85.8 1757.16    87.41756.823      90 1756.23
    94.2 1755.94    97.8 1756.32    98.4 1756.43   99.221756.816   102.6 1758.42
   106.8  1760.6   107.8 1760.93     111 1761.72   114.2 1762.07   127.8 1762.89
   140.4 1764.49   148.8 1765.64     153  1766.3   157.2 1766.76   164.5 1767.28
#Mann= 3 ,-1,0
       0      .1       0    87.4    .045       0   99.22      .1       0
Bank Sta=87.4,99.22
XS Rating Curve= 0 ,0
Exp/Cntr(USF)=0,0
Exp/Cntr=0.3,0.1

Type RM Length L Ch R = 1 ,63716   ,174.9,190.5,208.5
XS GIS Cut Line= 2
2209331.61859505699813.7078153242209381.76634347699662.742197674
#Sta/Elev= 30
       0 1761.17       9 1760.58    16.7 1760.36    27.1 1760.24    34.3 1760.35
    51.5 1760.19    59.6 1759.96      68 1759.54    73.6 1759.49    76.8 1759.21
    83.1 1757.16    86.3  1756.4    89.1 1755.88    92.6 1755.74    93.3 1755.74
    97.5 1756.37   101.7 1757.53   103.3  1758.1   107.3 1759.74   110.1 1761.01
   114.4 1762.35   118.6 1763.42   122.8 1763.57     127 1763.16   130.6 1763.31
   133.7    1764   141.3 1765.91   146.4 1766.84   152.3  1767.5   159.1 1767.66
#Mann= 3 ,-1,0
       0      .1       0    86.3    .045       0    97.5      .1       0
Bank Sta=86.3,97.5
XS Rating Curve= 0 ,0
Exp/Cntr(USF)=0,0
Exp/Cntr=0.3,0.1

Type RM Length L Ch R = 1 ,63525   ,277,275.3,272.7
XS GIS Cut Line= 3
2209341.42700879699866.9383399252209485.91856999699895.443477849
2209534.08242372699868.904211506
#Sta/Elev= 30
       0  1759.9     6.9 1759.83    19.1 1759.19    31.3  1759.1    39.5 1759.23
    43.6  1758.8    48.5 1757.76    55.8 1755.27   66.611752.594    68.9 1752.19
    72.1    1752    76.2 1751.97    80.3 1752.05    84.3 1752.55    92.5 1754.88
    99.6 1756.29   108.8 1758.46     117 1760.58   129.2 1764.46   140.5 1766.59
   156.5 1769.33   160.3 1770.15   165.3 1771.53   168.5 1772.26   177.3 1773.76
   185.9  1774.6     191 1774.96   195.5 1774.75   200.1 1774.82   202.3 1775.83
#Mann= 3 ,-1,0
       0      .1       0   66.61    .045       0    84.3      .1       0
Bank Sta=66.61,84.3
XS Rating Curve= 0 ,0
Exp/Cntr(USF)=0,0
Exp/Cntr=0.3,0.1

Type RM Length L Ch R = 1 ,63250   ,305,309.3,303.7
XS GIS Cut Line= 3
2209326.24611158700131.8941430052209528.29402407700137.354897396
2209628.77190487700112.235427195
#Sta/Elev= 30
       0 1754.21     1.9  1753.7     5.9 1753.29    17.9 1753.26    25.9 1753.48
    41.9 1752.82    74.7 1752.95      86 1753.33      90 1752.48      94 1751.16
      98 1750.54     102 1750.29  105.751749.765     110 1749.17     114 1749.05
     122 1749.11     126 1749.81     130 1751.34     138 1752.12     150 1754.12
     162 1755.24   202.8 1757.12   215.4 1757.31   255.6 1758.74   272.1  1760.1
   284.6 1760.88   292.7 1761.09   296.8 1760.88     301 1760.36   305.7 1760.76
#Mann= 3 ,-1,0
       0      .1       0  105.75    .045       0     126      .1       0
Bank Sta=105.75,126
XS Rating Curve= 0 ,0
Exp/Cntr(USF)=0,0
Exp/Cntr=0.3,0.1

Type RM Length L Ch R = 1 ,62941   ,178.4,204.8,220.9
XS GIS Cut Line= 4
2209236.55466932700301.9737609322209349.12673684700366.337266628
2209507.19585628700370.8956756662209654.07617853700475.958080477
#Sta/Elev= 30
       0 1773.92      18 1769.39    59.5 1757.84    70.9 1755.38      79 1754.16
    96.3  1752.1   119.3 1751.66   144.7 1749.24   176.7 1748.15   192.7 1748.39
   216.8  1747.3  223.07 1746.04   228.8 1744.97   236.5 1744.89   240.8 1744.95
   244.3 1746.05   248.8 1748.76   252.8  1749.8   264.8 1750.41   276.8 1752.38
   303.8 1760.45   321.7 1766.56   338.2 1768.65   360.5 1769.97   362.8 1770.35
   374.2 1774.41   415.5 1779.03   436.1 1784.08   456.2  1788.4   468.4 1791.94
#Mann= 4 ,-1,0
       0      .1       0  223.07    .045       0   244.3      .1       0
  269.67     .06       0
Bank Sta=223.07,244.3
XS Rating Curve= 0 ,0
Exp/Cntr(USF)=0,0
Exp/Cntr=0.3,0.1

Type RM Length L Ch R = 1 ,62736   ,220.4,216.8,207.8
XS GIS Cut Line= 5
2209203.84792304 700361.544888762209291.91367407700406.458421785
2209367.95341265700494.7078311052209369.38194516700540.079629776
 2209525.2879143700616.935566747
#Sta/Elev= 30
       0 1773.48    72.2 1754.63    85.7 1752.31   107.7 1750.37   123.6 1746.89
   163.4 1746.95   192.2 1747.72   203.4 1748.71   217.8 1747.94  231.37 1743.98
   233.8    1743   241.8 1742.58  248.14 1743.97   253.8 1747.79   260.7  1751.4
   272.8 1752.64   286.2 1755.19     304 1759.21   312.9 1761.99   317.4  1765.7
   321.8 1770.85   326.3 1772.19   338.3 1769.33   347.3 1769.16     362 1771.98
   377.2 1772.49   388.7    1777   397.6 1779.21     425 1781.01   434.6 1783.23
#Mann= 4 ,-1,0
       0      .1       0  231.37    .045       0  248.14      .1       0
  390.74     .06       0
Bank Sta=231.37,248.14
XS Rating Curve= 0 ,0
Exp/Cntr(USF)=0,0
Exp/Cntr=0.3,0.1

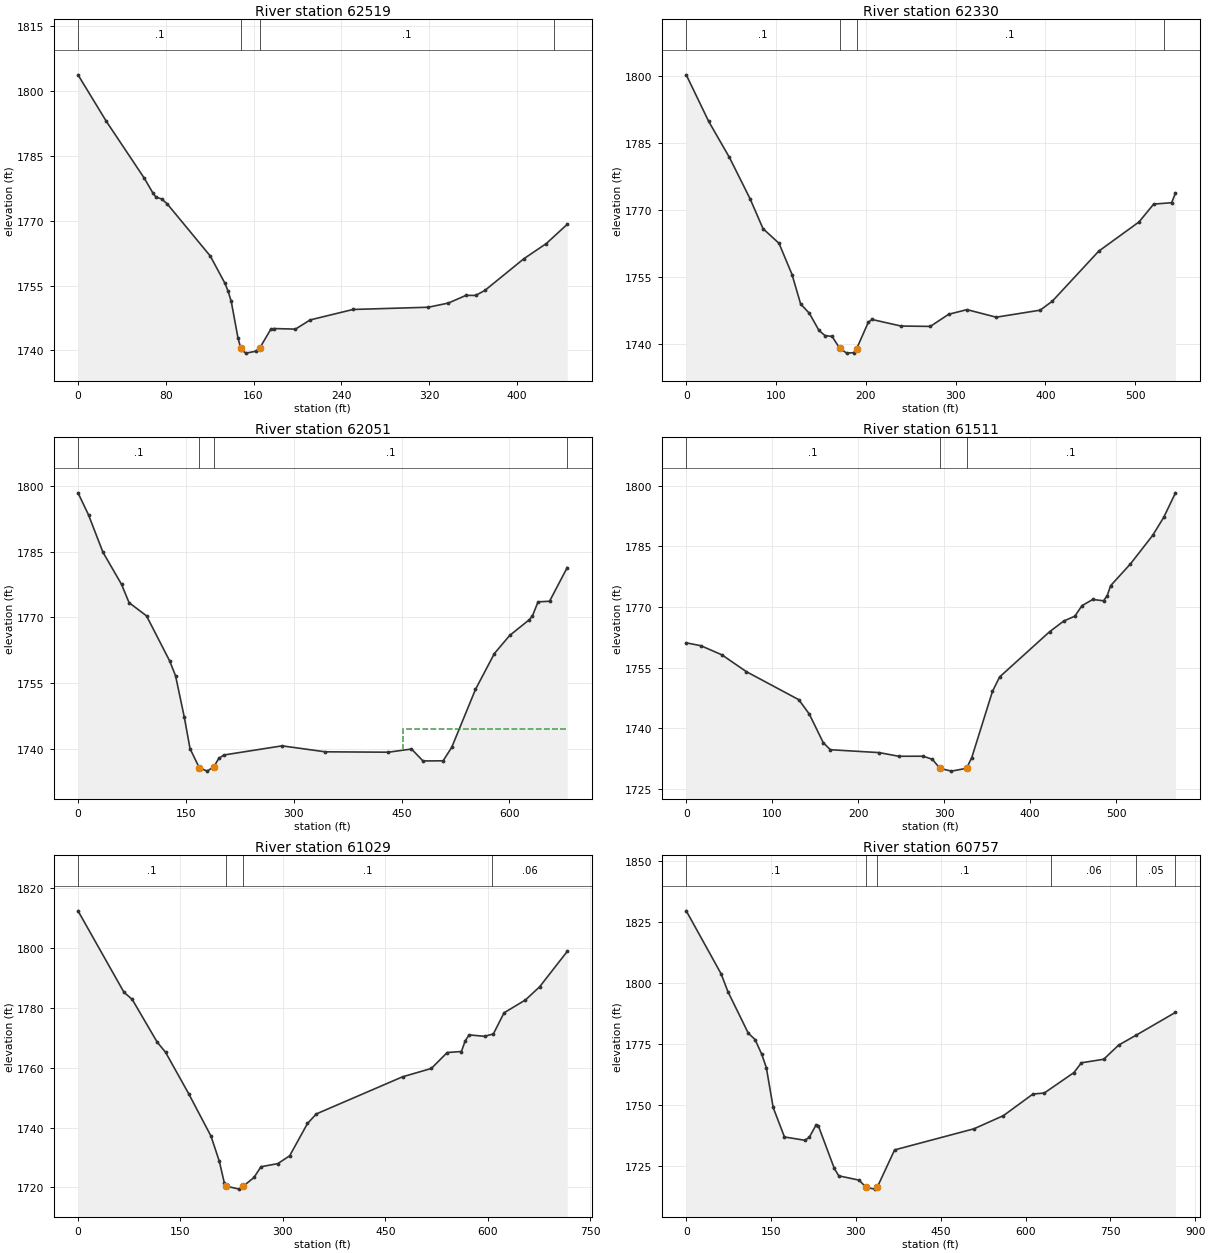
Type RM Length L Ch R = 1 ,62519   ,200.6,188.8,172.4
XS GIS Cut Line= 4
2209050.08417126700419.0068566662209144.95655259700499.765991191
2209185.72815449700578.9569871822209402.13127225700663.636468044
#Sta/Elev= 30
       0 1803.72    25.7 1793.02    60.5  1779.8    68.3 1776.39    71.1 1775.44
    76.3 1775.03    81.5 1773.84   120.6 1761.83     134 1755.51   136.9 1753.66
   139.7 1751.34   145.8 1742.95   148.2 1740.67   148.8 1740.12   153.2 1739.39
   162.2 1739.83  165.83 1740.63   175.7 1744.89   178.5 1745.07   198.2 1744.94
   211.7 1747.07   250.7 1749.48   319.4    1750   337.7 1750.97   353.7 1752.74
   362.5 1752.73   370.9 1753.88   406.4  1761.2   426.8  1764.7     446 1769.17
#Mann= 4 ,-1,0
       0      .1       0   148.2    .045       0  165.83      .1       0
  433.66     .06       0
Bank Sta=148.2,165.83
XS Rating Curve= 0 ,0
Exp/Cntr(USF)=0,0
Exp/Cntr=0.3,0.1

Type RM Length L Ch R = 1 ,62330   ,280,279.3,275.9
XS GIS Cut Line= 4
2208931.13300779700551.5217201282209008.78658529 700666.75903233
2209090.88086167700675.9185413692209408.00963767700738.355837641
#Sta/Elev= 30
       0 1800.21      25 1789.79    48.1 1781.72    71.1 1772.48    85.5 1765.79
   103.3 1762.52   117.8 1755.54   127.4 1748.94   137.1 1746.86   147.8 1743.03
   154.4 1741.89   162.5 1741.67   170.71739.097   178.6 1737.95   186.6 1738.06
   189.61738.872   202.7 1744.84   206.8 1745.48   239.2 1744.01   271.8 1743.93
   292.2 1746.64   312.6 1747.68   345.2 1745.99   394.1 1747.56   407.7 1749.58
   459.3 1760.76   504.2  1767.3   520.5 1771.29   540.5  1771.6   544.8 1773.76
#Mann= 4 ,-1,0
       0      .1       0   170.7    .045       0   189.6      .1       0
  531.56     .06       0
Bank Sta=170.7,189.6
XS Rating Curve= 0 ,0
Exp/Cntr(USF)=0,0
Exp/Cntr=0.3,0.1

Type RM Length L Ch R = 1 ,62051   ,537.6,540.4,561.8
XS GIS Cut Line= 3
2208713.88182199700899.3738764732208856.42995123700878.837281583
2209392.79748837700872.797106615
#Sta/Elev= 30
       0 1798.44    14.6 1793.42    34.6 1784.91    60.5 1777.56      71 1773.38
    95.3 1770.36   127.6 1760.03   135.7 1756.67   147.8 1747.26   155.8 1740.05
   168.71735.678   179.8 1734.92   189.11735.975   195.8 1737.82   202.8  1738.6
   283.8 1740.69   343.8 1739.33   431.8 1739.24   463.8 1739.97   479.8 1737.24
   507.8 1737.28   519.8 1740.37   552.8 1753.57     579 1761.74   600.3 1765.88
   627.8  1769.5     632 1770.34   639.8 1773.56   655.8 1773.69   680.4 1781.39
#Mann= 4 ,-1,0
       0      .1       0   168.7    .045       0   189.1      .1       0
  680.42     .06       0
#XS Ineff= 2 , 0
                          452.01         1744.59
Permanent Ineff=
       F       F
Bank Sta=168.7,189.1
XS Rating Curve= 0 ,0
Exp/Cntr(USF)=0,0
Exp/Cntr=0.3,0.1

Type RM Length L Ch R = 1 ,61511   ,491.3,481.3,457.2
XS GIS Cut Line= 4
2208907.38028361701239.3535342662209177.97685849701190.573220282
2209240.07514446701219.5053762432209456.49986419701156.561362549
#Sta/Elev= 30
       0 1761.12    17.1  1760.4    41.5 1758.15    69.9 1753.99   130.9 1747.05
   143.1 1743.49   159.3 1736.43   167.5 1734.68   224.4 1733.96   247.1 1733.06
   275.6 1733.07   286.2  1732.3     295 1730.07   308.3 1729.38   325.9 1730.07
     332 1732.72   356.1 1749.13   364.4 1752.68   422.4 1763.85     439 1766.52
   451.9 1767.72   460.2 1770.33   472.7 1771.85   485.2 1771.52   489.4 1772.74
   493.5 1775.27   516.5 1780.64   542.3 1787.69   555.2 1792.16   568.9 1798.23
#Mann= 3 ,-1,0
       0      .1       0     295    .045       0   325.9      .1       0
Bank Sta=295,325.9
XS Rating Curve= 0 ,0
Exp/Cntr(USF)=0,0
Exp/Cntr=0.3,0.1

Type RM Length L Ch R = 1 ,61029   ,270,272.5,272.5
XS GIS Cut Line= 4
2208941.94370148701700.2247840522209080.83252868701676.339444343
2209398.41908259701540.9891859932209575.34752487701394.138578895
#Sta/Elev= 30
       0  1812.5    67.2 1785.28    79.4 1782.84   115.9 1768.57   128.1 1765.19
     162 1751.31   194.7 1737.09   206.9 1728.65   214.1 1721.51     217 1720.39
   235.9 1719.38  242.18 1720.42   257.6 1723.28   267.8 1726.87   292.4 1727.91
   309.8 1730.53   335.9 1741.35   348.9 1744.55     475 1756.96   517.2 1759.76
   540.4 1765.09   561.2 1765.43   566.8 1769.03   572.5 1770.99   595.2 1770.51
     608 1771.33   623.6 1778.38   654.9 1782.68   675.6 1787.06   716.1 1798.93
#Mann= 4 ,-1,0
       0      .1       0     217    .045       0  242.18      .1       0
  606.15     .06       0
Bank Sta=217,242.18
XS Rating Curve= 0 ,0
Exp/Cntr(USF)=0,0
Exp/Cntr=0.3,0.1

Type RM Length L Ch R = 1 ,60757   ,118.7,123.4,129.7
XS GIS Cut Line= 5
2208946.48803936701889.6512142652209257.48608212701892.414806735
2209310.01181709701875.1122116862209578.85688125701895.044551935
2209787.84871599701800.661142698
#Sta/Elev= 30
       0 1829.47    61.7 1803.65    73.7 1796.37   109.7 1779.36   121.7 1776.74
   133.7 1770.62   141.7 1765.19   153.7 1748.92   173.7 1736.84   209.7 1735.48
   217.7 1736.72   229.7  1741.8   233.7 1741.37   261.7 1724.03   269.7 1720.92
   305.7 1719.15   318.1 1716.18   334.1 1715.47  337.64 1716.18   368.5 1731.54
   508.9 1740.19     561 1745.59   613.2 1754.43   633.2 1754.84   685.6 1763.21
   698.8 1767.22   738.3 1768.67   764.6 1774.46   795.9 1778.56   865.2 1787.88
#Mann= 6 ,-1,0
       0      .1       0   318.1    .045       0  337.64      .1       0
   645.9     .06       0   795.9     .05       0  865.21      .1       0
Bank Sta=318.1,337.64
XS Rating Curve= 0 ,0
Exp/Cntr(USF)=0,0
Exp/Cntr=0.3,0.1

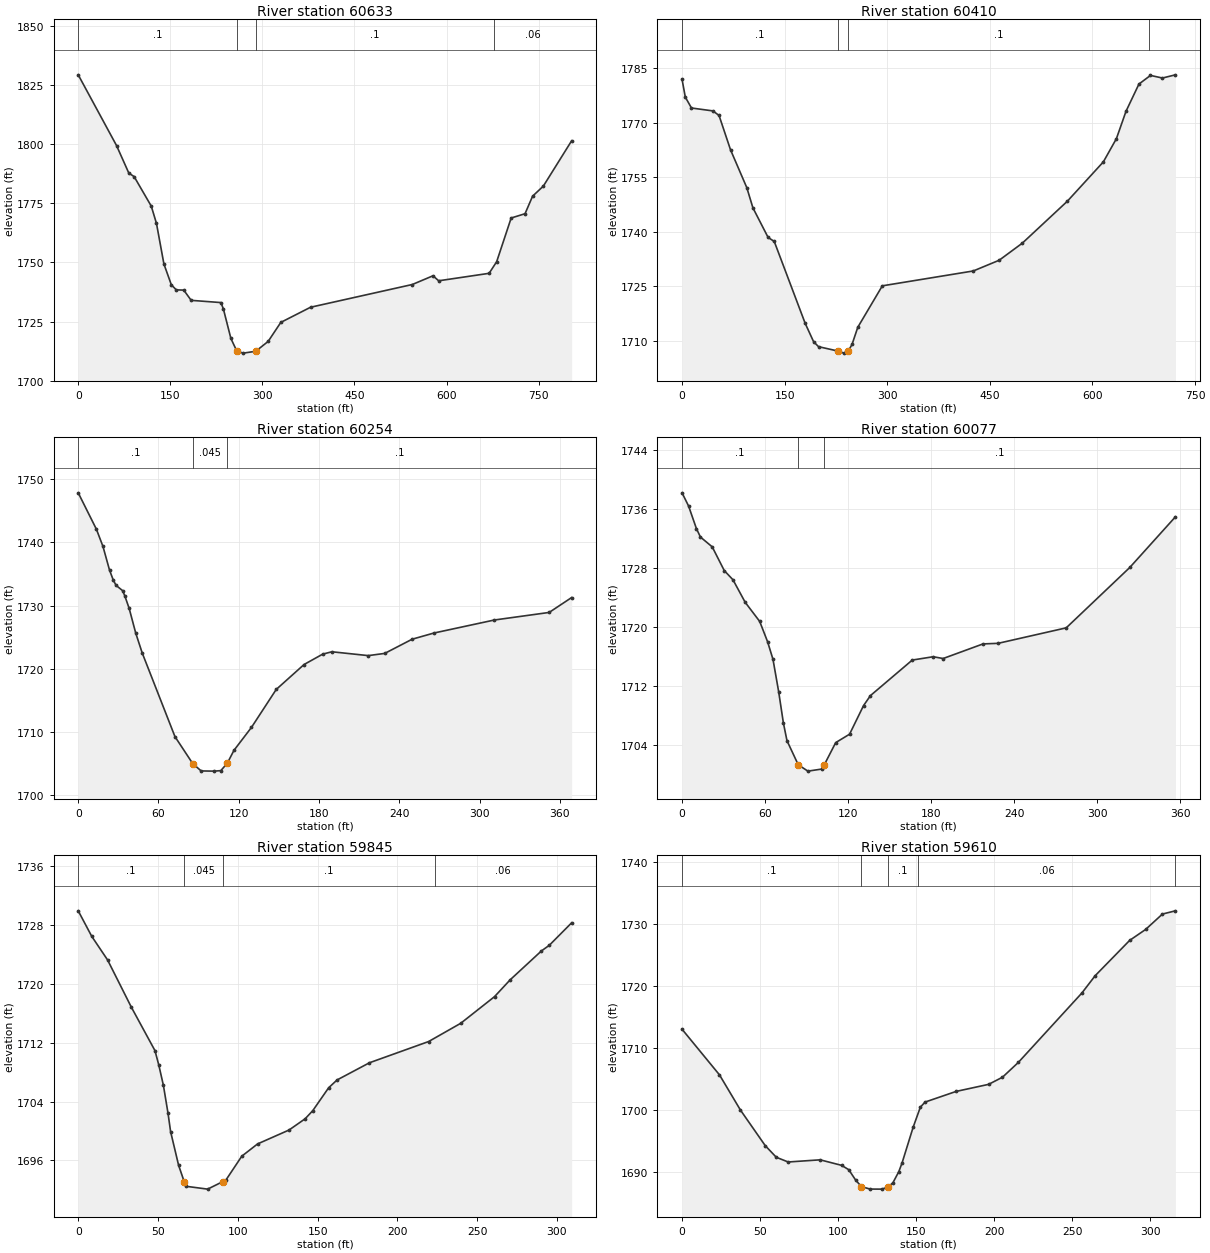
Type RM Length L Ch R = 1 ,60633   ,223.2,223.2,222.2
XS GIS Cut Line= 6
2208947.39162926701987.0821912582209040.42670407 702008.65554194
2209196.83349652701988.4305256752209368.07196756702018.093882863
2209599.98548739702146.1856525382209702.45890313702190.680688319
#Sta/Elev= 30
       0 1829.34    62.4 1799.44    82.4  1787.8    91.1 1786.29     119 1773.81
   127.5 1766.47   139.6 1749.34   151.7 1740.53   159.8  1738.4   171.9  1738.3
     184 1733.97   232.4 1733.03   236.4  1730.4   248.7 1717.84  258.48 1712.44
   268.8 1711.65   289.1 1712.43   309.4 1716.61     330 1724.65   378.4 1731.05
   544.2 1740.67   577.9 1744.36   587.1 1742.24   669.3  1745.4   681.6 1750.32
   705.2 1768.79   727.8 1770.61   740.1 1778.02   757.6 1782.28   803.7 1801.45
#Mann= 4 ,-1,0
       0      .1       0  258.48    .045       0   289.1      .1       0
     677     .06       0
Bank Sta=258.48,289.1
XS Rating Curve= 0 ,0
Exp/Cntr(USF)=0,0
Exp/Cntr=0.3,0.1

Type RM Length L Ch R = 1 ,60410   ,152.3,156.3,162.8
XS GIS Cut Line= 6
2208955.85664958702134.2474661252209083.94841925702198.967518171
2209291.59191957702224.5858721062209472.26873153702287.957589734
2209570.69714402 702352.677641782209625.97885514702374.250992462
#Sta/Elev= 30
       0 1781.89     4.8 1776.98    13.8 1773.99    45.2 1773.19    54.1 1771.93
    70.9 1762.48    94.7 1752.06   103.6 1746.52   125.8 1738.38   134.8 1737.27
     180 1714.74   192.3 1709.69   199.5 1708.32   228.4 1707.09   236.4 1706.54
  242.881707.105   248.5 1708.93   256.9 1713.65   292.8 1725.06   425.8 1729.15
   463.6  1732.1   497.5 1736.81   563.2 1748.33   615.9 1759.17     635 1765.57
     649 1773.09   667.9 1780.58   684.8 1782.96   702.2 1782.24   721.3 1783.12
#Mann= 4 ,-1,0
       0      .1       0   228.4    .045       0  242.88      .1       0
     682     .06       0
Bank Sta=228.4,242.88
XS Rating Curve= 0 ,0
Exp/Cntr(USF)=0,0
Exp/Cntr=0.3,0.1

Type RM Length L Ch R = 1 ,60254   ,176.4,177.2,177.7
XS GIS Cut Line= 3
2208993.08486473702271.8178300182209160.18394911702389.770124877
2209320.73012822702424.718952983
#Sta/Elev= 30
       0 1747.86    13.6 1742.09    18.5 1739.37    23.4 1735.62    26.2 1734.04
    28.3  1733.2    33.2 1732.36    34.8 1731.55    38.1 1729.54      43 1725.63
    47.8 1722.51    72.3 1709.24    85.6 1704.96    91.9  1703.8   101.7 1703.77
   106.6 1703.85   111.5 1705.05   116.4 1707.06   129.5  1710.7     148 1716.71
   168.8 1720.66   182.7  1722.3   189.6 1722.68   216.8 1722.07   229.1 1722.42
   249.6 1724.67   265.9 1725.65     311 1727.71     352 1728.91   368.8 1731.27
#Mann= 3 ,-1,0
       0      .1       0    85.6    .045       0   111.5      .1       0
Bank Sta=85.6,111.5
XS Rating Curve= 0 ,0
Exp/Cntr(USF)=0,0
Exp/Cntr=0.3,0.1

Type RM Length L Ch R = 1 ,60077   ,224.4,231.5,233.1
XS GIS Cut Line= 3
2208895.88343656702414.8895950782209060.79821918702540.486946085
2209170.01330701702642.056977769
#Sta/Elev= 30
       0  1738.2     4.7 1736.42    10.4 1733.34    13.3  1732.2    21.8 1730.87
    30.5 1727.65    36.8  1726.4    45.6 1723.35    56.1 1720.75    61.8 1717.99
    65.7  1715.6    69.8 1711.21    73.2 1706.98    75.8 1704.57   83.94  1701.3
    90.9 1700.44   100.9 1700.72   102.8 1701.32     111 1704.31     121 1705.45
   131.1 1709.33   136.1 1710.69   166.3 1715.51   181.4 1715.96   188.6 1715.72
   217.4  1717.7   228.3 1717.78   277.5 1719.88   323.4 1728.07   356.4 1734.95
#Mann= 3 ,-1,0
       0      .1       0   83.94    .045       0   102.8      .1       0
Bank Sta=83.94,102.8
XS Rating Curve= 0 ,0
Exp/Cntr(USF)=0,0
Exp/Cntr=0.3,0.1

Type RM Length L Ch R = 1 ,59845   ,237.1,234.6,224.7
XS GIS Cut Line= 3
2208760.45672764 702550.316303992208856.56600494702682.466560266
2208975.61045067702766.562177897
#Sta/Elev= 30
       0 1729.96     8.5 1726.48    18.4 1723.28    33.3 1716.85    48.1 1710.94
    50.5 1708.98    53.4  1706.2    56.3 1702.39    57.9 1699.92    62.9 1695.35
   66.42 1693.11    67.8 1692.48    81.1  1692.1    90.6 1693.12    92.6 1693.35
   102.5 1696.58   112.4 1698.25   132.1 1700.14   142.2 1701.67     147 1702.78
   156.9 1705.88   162.2 1706.95   182.5 1709.29   219.6 1712.18   239.7 1714.66
   260.9 1718.29   270.7 1720.58   290.3 1724.51   295.2 1725.27   309.2 1728.33
#Mann= 4 ,-1,0
       0      .1       0   66.42    .045       0    90.6      .1       0
   223.4     .06       0
Bank Sta=66.42,90.6
XS Rating Curve= 0 ,0
Exp/Cntr(USF)=0,0
Exp/Cntr=0.3,0.1

Type RM Length L Ch R = 1 ,59610   ,237.9,247,250.3
XS GIS Cut Line= 4
2208600.37891235702721.0296384082208653.89430539702782.190087594
2208743.45067741702832.4290279962208847.20501085 702914.34034387
#Sta/Elev= 30
       0 1713.02      24 1705.65    37.4 1699.98    53.3 1694.23    60.4 1692.35
      68 1691.59    88.5 1691.94   102.2 1691.05   106.8 1690.35   111.4 1688.61
  114.981687.621   120.4 1687.22   128.3 1687.21   132.1  1687.6   135.1 1688.23
   138.9 1690.04     141 1691.46   148.1 1697.22   152.7 1700.44   155.7 1701.26
   175.6 1702.98   196.4 1704.12   205.3 1705.27   215.5 1707.67   256.2 1718.87
   264.7 1721.66   286.8 1727.36     297 1729.12   307.8 1731.61   316.1 1732.13
#Mann= 5 ,-1,0
       0      .1       0  114.98    .045       0   132.1      .1       0
  151.27     .06       0  316.14      .1       0
Bank Sta=114.98,132.1
XS Rating Curve= 0 ,0
Exp/Cntr(USF)=0,0
Exp/Cntr=0.3,0.1