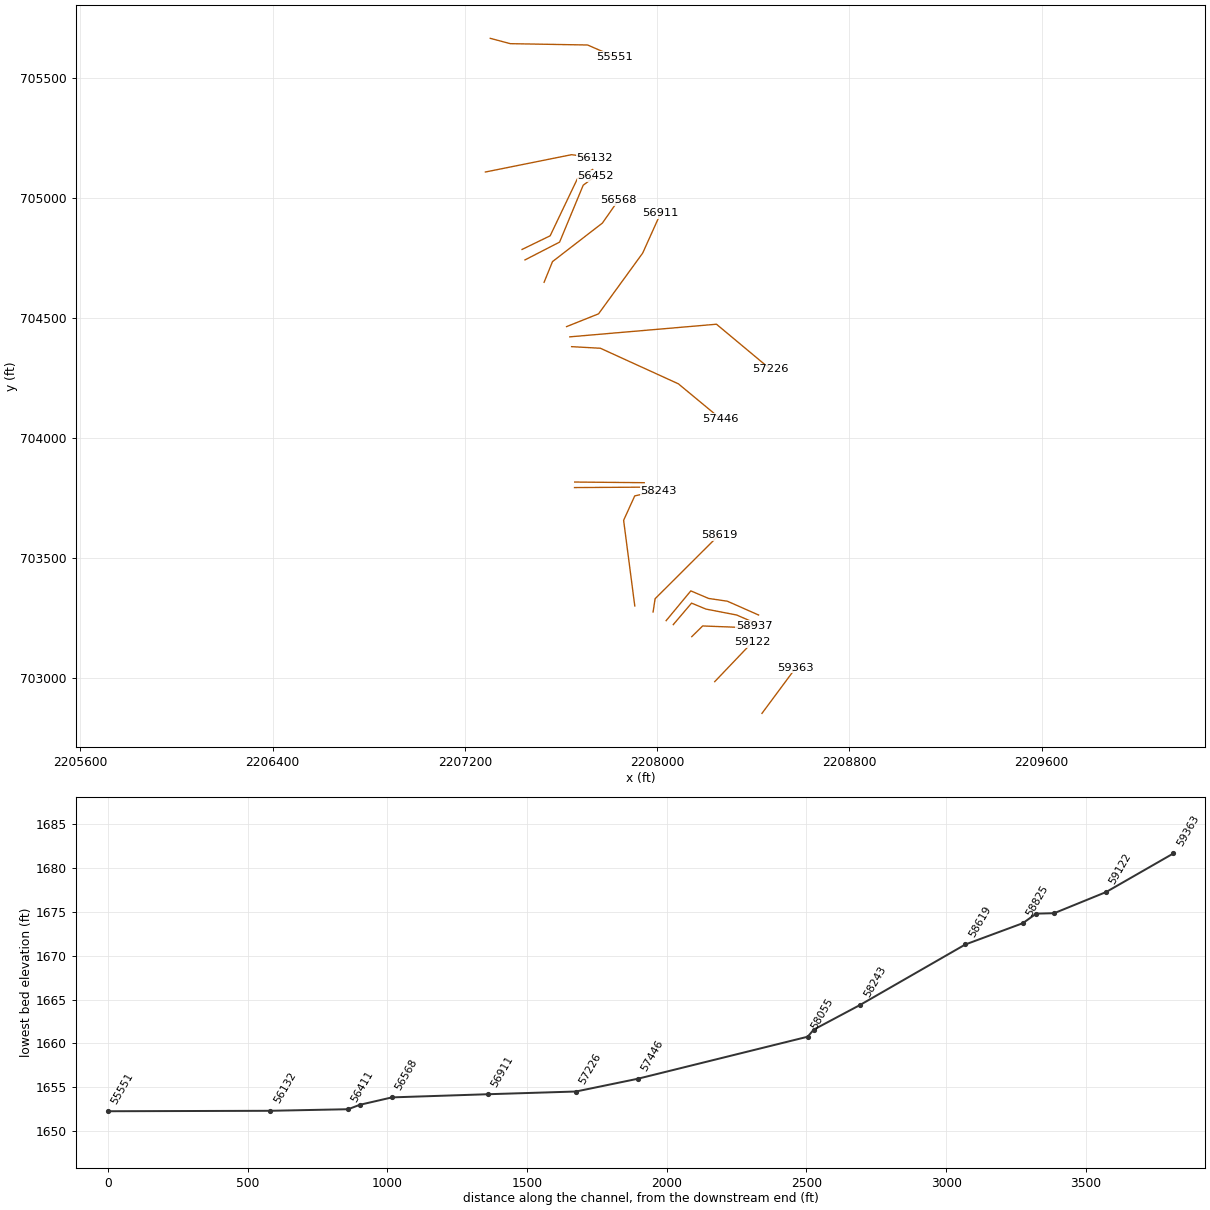
HEC-RAS study SANDRN1.prj: SANDRN1

--- SANDRN1.g01 (geometry) --- (continued)

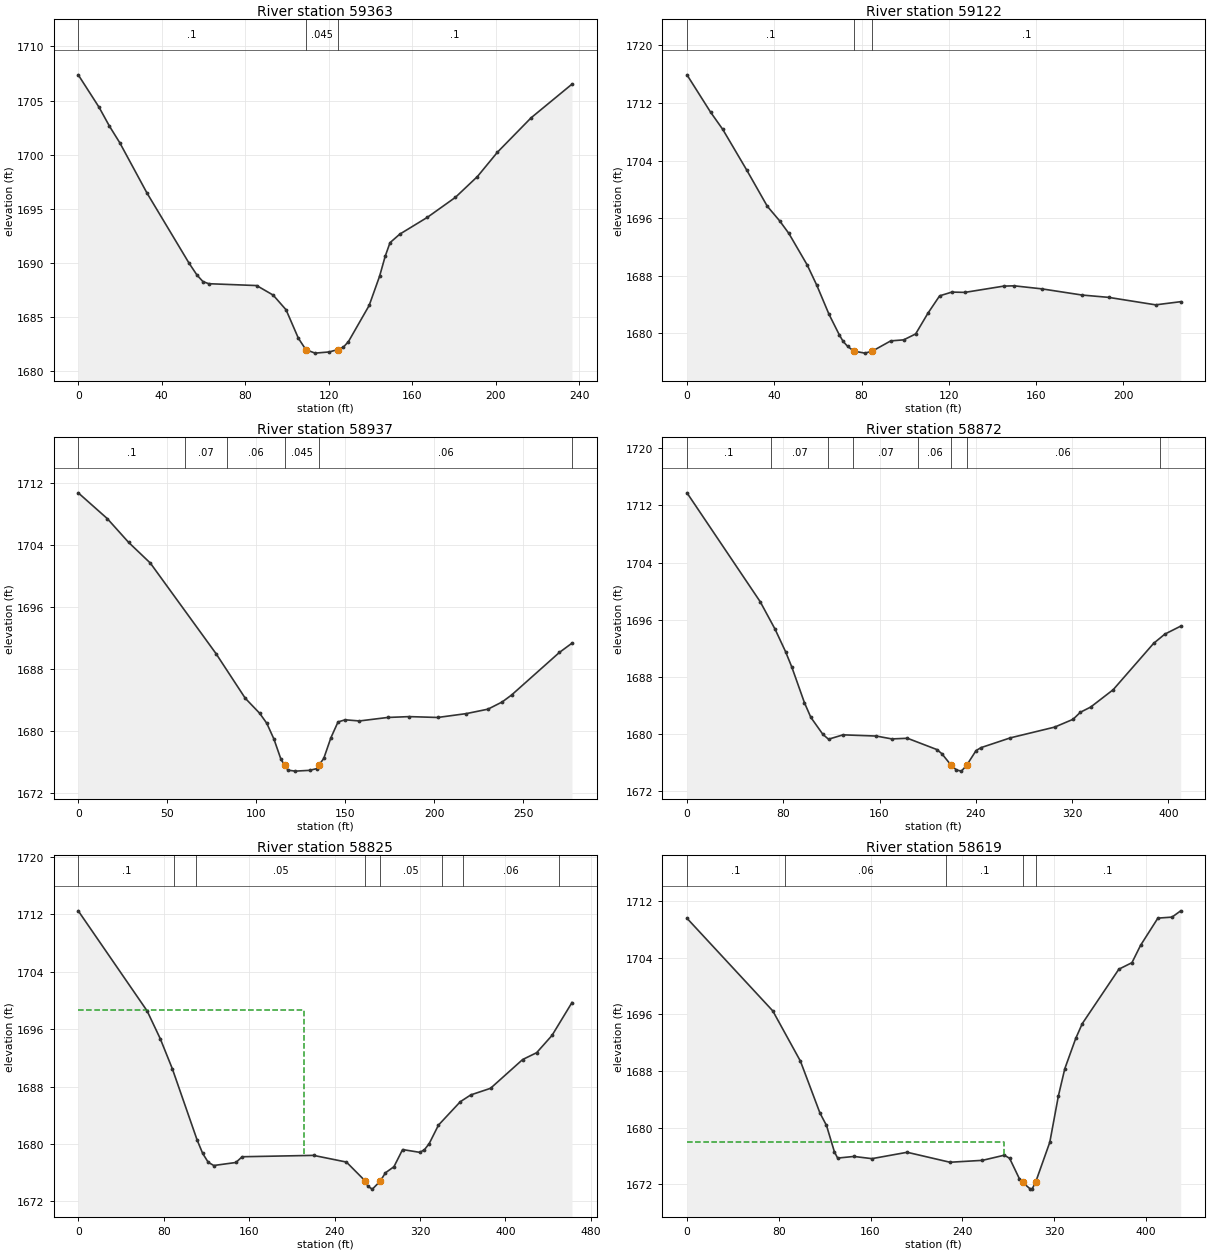
Type RM Length L Ch R = 1 ,59363   ,240.3,241.1,239.3
XS GIS Cut Line= 2
2208436.55628061702853.1798946842208577.44374391703043.214147512
#Sta/Elev= 30
       0 1707.38      10 1704.38    14.9 1702.66    19.9 1701.11    32.9 1696.48
    53.1 1689.99    56.9 1688.89    59.8 1688.28    62.6 1688.09    85.5 1687.92
    93.4 1687.04    99.6 1685.68   105.5 1683.05   109.11681.996   113.5 1681.68
   120.3 1681.79   124.41682.011     127 1682.22   129.5 1682.75   139.4 1686.08
   144.4 1688.78   147.1 1690.63   149.4 1691.88   154.1 1692.67   167.3 1694.22
   180.7 1696.06   191.3 1697.99   200.9 1700.24     217 1703.41   236.6 1706.52
#Mann= 3 ,-1,0
       0      .1       0   109.1    .045       0   124.4      .1       0
Bank Sta=109.1,124.4
XS Rating Curve= 0 ,0
Exp/Cntr(USF)=0,0
Exp/Cntr=0.3,0.1

Type RM Length L Ch R = 1 ,59122   ,192.6,185.7,173.5
XS GIS Cut Line= 2
2208239.96912251702985.3301509612208396.14669811703149.152782709
#Sta/Elev= 30
       0 1715.89    10.8 1710.72    16.4 1708.32    27.4 1702.67    36.8 1697.66
    42.5 1695.62    46.7 1693.88    55.1 1689.51    59.5 1686.69    65.1 1682.66
    69.9 1679.76    71.6 1678.89    73.6 1678.22    76.4 1677.56    81.5 1677.27
    84.9 1677.54    93.4 1678.97    99.3 1679.11   104.8 1679.93   110.4 1682.79
   115.8 1685.22   121.4 1685.74   127.4  1685.7   145.2 1686.57     150 1686.61
   162.6 1686.19   181.1 1685.33   193.2 1685.01   214.8 1683.97   226.3 1684.41
#Mann= 3 ,-1,0
       0      .1       0    76.4    .045       0    84.9      .1       0
Bank Sta=76.4,84.9
XS Rating Curve= 0 ,0
Exp/Cntr(USF)=0,0
Exp/Cntr=0.3,0.1

Type RM Length L Ch R = 1 ,58937   ,66.2,64.3,63.5
XS GIS Cut Line= 4
2208144.54178423703172.7961017832208189.68507627703217.222833641
2208340.87927663703211.4903521112208403.22001327703217.939393832
#Sta/Elev= 30
       0 1710.75    16.3 1707.43    28.3 1704.36    40.5 1701.69    77.4 1690.01
    93.8 1684.26   101.9 1682.32   105.9 1681.03   109.9    1679   113.9 1676.36
   115.9 1675.67   117.9 1674.98   121.9 1674.86   129.9 1674.96   133.9 1675.18
   135.2 1675.64   137.9  1676.5   141.9 1679.16   145.9  1681.2   149.9 1681.48
   157.9 1681.33   173.8 1681.78   185.9 1681.89   201.9 1681.78     218 1682.28
   230.1 1682.85   238.1 1683.78   243.4 1684.68   270.2 1690.16   277.3 1691.36
#Mann= 6 ,-1,0
       0      .1       0      60     .07       0   83.34     .06       0
   115.9    .045       0   135.2     .06       0  277.31     .07       0
Bank Sta=115.9,135.2
XS Rating Curve= 0 ,0
Exp/Cntr(USF)=0,0
Exp/Cntr=0.3,0.1

Type RM Length L Ch R = 1 ,58872   ,47.2,47.8,48.1
XS GIS Cut Line= 5
2208067.33108224 703222.856886922208143.56630724703312.375554145
2208203.12366169703287.6126967992208331.39678234 703262.84271488
2208420.74564569703223.918457578
#Sta/Elev= 30
       0 1713.77    60.8 1698.54    73.2 1694.68    81.9 1691.54    87.1 1689.38
    97.6 1684.39   102.9 1682.34   112.9 1679.96   117.6 1679.28   129.7 1679.89
   157.3 1679.72   170.2 1679.32   183.2 1679.41   207.6 1677.83   211.7 1677.26
   219.5 1675.63   223.9 1674.97     228 1674.81  232.291675.616   240.2 1677.69
   244.3  1678.1   268.7 1679.47   305.4 1680.97   320.7 1682.06   326.9 1683.06
   335.4 1683.78   354.1 1686.21   387.7  1692.7     397 1693.99   410.2 1695.11
#Mann= 8 ,-1,0
       0      .1       0      70     .07       0  117.58     .05       0
  137.58     .07       0  192.08     .06       0   219.5    .045       0
  232.29     .06       0  392.72     .07       0
Bank Sta=219.5,232.29
XS Rating Curve= 0 ,0
Exp/Cntr(USF)=0,0
Exp/Cntr=0.3,0.1

Type RM Length L Ch R = 1 ,58825   ,193.9,205.8,215.7
XS GIS Cut Line= 5
2208037.78403237703239.4881604942208140.38159528703363.330945524
2208214.62401044 703331.844807372208292.47252504703320.344458621
2208422.51493012 703262.84271488
#Sta/Elev= 30
       0 1712.48    64.5 1698.54    76.8 1694.67    88.1 1690.49   111.3 1680.57
   116.5  1678.7   121.7 1677.46   126.9 1677.01   147.6 1677.43   153.5 1678.23
   220.3 1678.42   251.1 1677.49   268.6 1674.87   271.3 1674.09   275.4 1673.72
   282.8 1674.84   287.6 1675.99   295.6 1676.84   303.7 1679.23   319.9 1678.84
   324.2 1679.22   328.6 1680.06   337.3 1682.64   357.7 1685.89   367.5 1686.84
     386 1687.76   416.1 1691.77   429.2 1692.72   443.6 1695.13   462.3 1699.71
#Mann= 8 ,-1,0
       0      .1       0      90     .06       0     110     .05       0
   268.6    .045       0   282.8     .05       0  340.16      .1       0
  360.16     .06       0  450.16     .07       0
#XS Ineff= 2 , 0
          211.36  1698.7
Permanent Ineff=
       F       F
Bank Sta=268.6,282.8
XS Rating Curve= 0 ,0
Exp/Cntr(USF)=0,0
Exp/Cntr=0.3,0.1

Type RM Length L Ch R = 1 ,58619   ,368.1,375.5,377.8
XS GIS Cut Line= 3
2207983.39423872703275.5589230112207991.78748791 703330.64570372
2208256.94275919 703595.22770086
#Sta/Elev= 30
       0 1709.59    74.8 1696.49    98.9 1689.38   115.9 1682.05   121.6 1680.29
   128.5 1676.56   131.3 1675.68   145.5 1675.91   161.2  1675.6   191.9  1676.5
   229.2 1675.09   257.5 1675.36   276.6 1676.09   281.2 1675.64   289.7 1672.76
   292.5 1672.25   299.3 1671.29     301 1671.37   303.9  1672.3   316.2 1677.92
   323.7 1684.48   329.3 1688.33   338.8  1692.6   344.5 1694.69   376.4 1702.39
   387.8 1703.31   395.3 1705.76   410.4 1709.61   422.7 1709.75   430.3 1710.64
#Mann= 5 ,-1,0
       0      .1       0   85.72     .06       0  225.72      .1       0
   292.5    .045       0   303.9      .1       0
#XS Ineff= 2 , 0
          276.68  1677.9
Permanent Ineff=
       F       F
Bank Sta=292.5,303.9
XS Rating Curve= 0 ,0
Exp/Cntr(USF)=0,0
Exp/Cntr=0.3,0.1

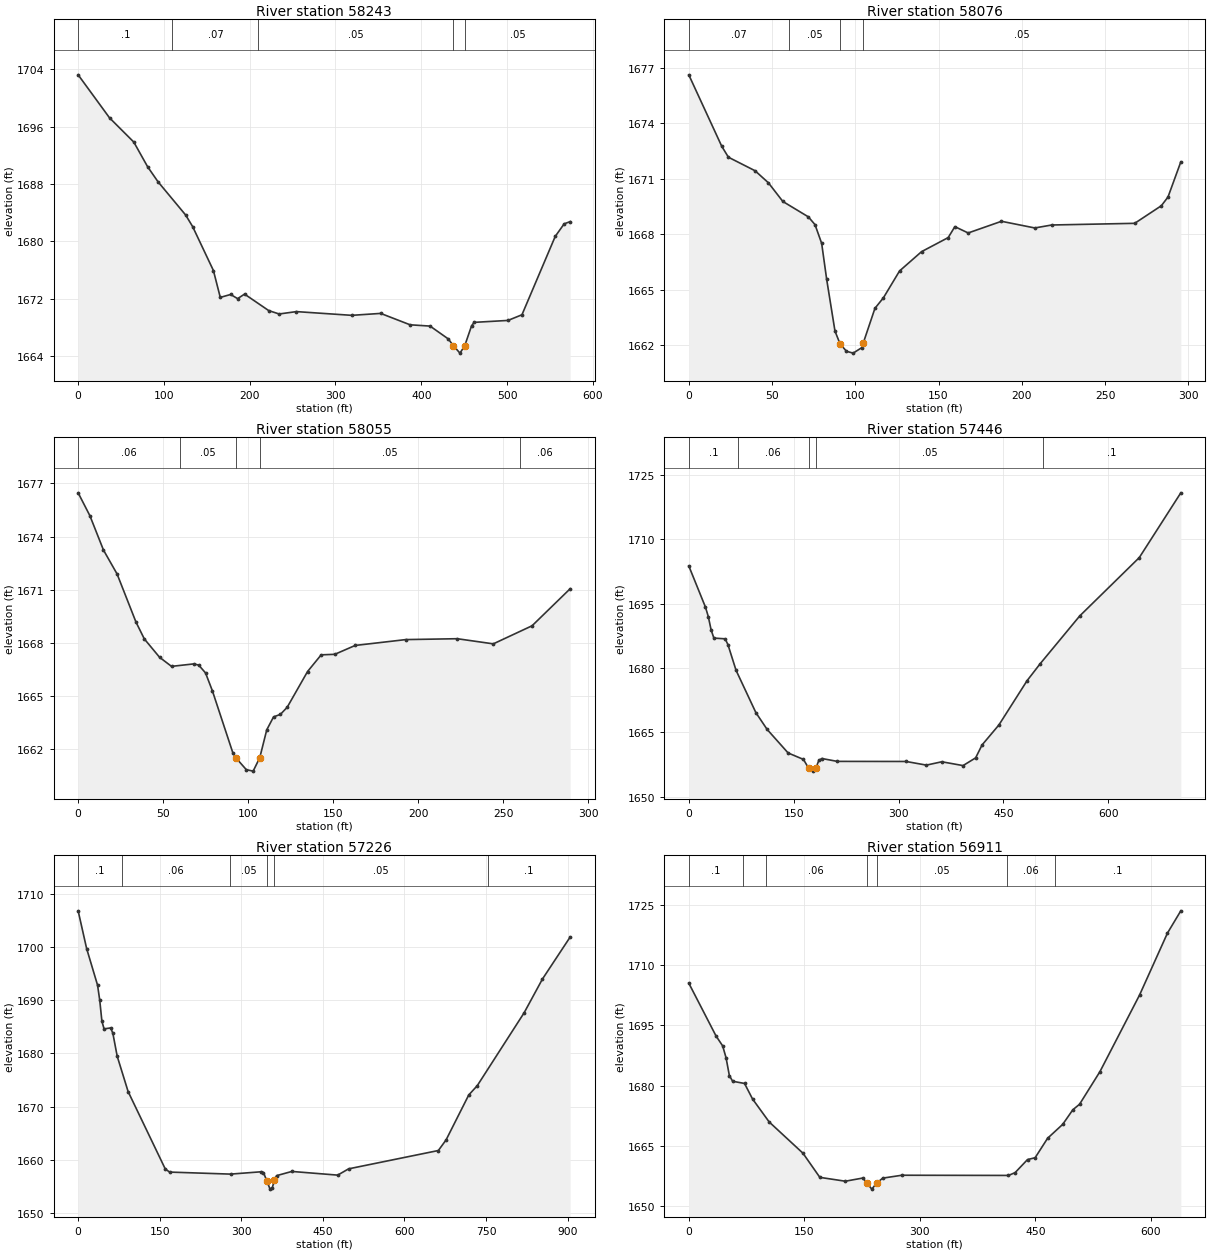
Type RM Length L Ch R = 1 ,58243   ,181.9,166.8,154.7
XS GIS Cut Line= 4
2207907.13956183703300.845788645 2207860.7340503703657.150517159
2207906.91054937 703758.95044241 2208007.0090855703780.900765896
#Sta/Elev= 30
       0 1703.22    36.6 1697.22    64.9 1693.84      81  1690.4    93.1 1688.31
   125.4 1683.66   133.5 1682.05   157.7 1675.93   165.7 1672.18   177.8 1672.59
   185.9 1672.01     194 1672.64   222.2 1670.34   234.3 1669.87   254.5  1670.2
     319 1669.68   352.7 1669.95     387 1668.36   410.3 1668.18   431.4  1666.4
   437.51665.447   445.1 1664.41   450.61665.415   458.6  1668.2   461.6  1668.7
   501.1 1668.97   517.4 1669.76   556.2 1680.69   566.6 1682.44   573.6 1682.75
#Mann= 5 ,-1,0
       0      .1       0     110     .07       0     210     .05       0
   437.5    .045       0   450.6     .05       0
Bank Sta=437.5,450.6
XS Rating Curve= 0 ,0
Exp/Cntr(USF)=0,0
Exp/Cntr=0.3,0.1

Type RM Length L Ch R = 1 ,58076   ,21.9,21.6,21.5
XS GIS Cut Line= 2
2207656.41477504703793.6280417242207951.88527365703795.397326146
#Sta/Elev= 30
       0 1676.61    19.8 1672.75    23.8 1672.16    39.8 1671.43    47.8 1670.78
    56.5 1669.77    71.8 1668.94    75.8 1668.52    79.8 1667.51    82.8 1665.57
    87.8 1662.77    90.8 1662.09    94.7 1661.68    98.7 1661.58   103.8 1661.87
   104.8 1662.13   111.8    1664   116.9 1664.57   126.6 1666.02   139.8 1667.06
   155.8 1667.82   159.8 1668.41   167.8 1668.07   187.8  1668.7   207.8 1668.34
     218  1668.5   267.8 1668.59   283.8 1669.54   287.8 1670.01   295.5 1671.91
#Mann= 4 ,-1,0
       0     .07       0      60     .05       0    90.8    .045       0
   104.8     .05       0
Bank Sta=90.8,104.8
XS Rating Curve= 0 ,0
Exp/Cntr(USF)=0,0
Exp/Cntr=0.3,0.1

Type RM Length L Ch R = 1 ,58055   ,609.5,608.6,600.6
XS GIS Cut Line= 2
2207657.29941725 703816.628739222207946.57742038703813.974812586
#Sta/Elev= 30
       0 1676.47     6.9 1675.18    14.9 1673.24    22.9 1671.89      34 1669.18
    38.9 1668.23    47.9 1667.19    54.9 1666.68    68.1 1666.82    70.9 1666.75
    74.9 1666.31    78.9 1665.31    90.9 1661.82      931661.493    98.9 1660.85
   102.9 1660.77   106.81661.531   110.9  1663.1   114.9 1663.83   118.9 1663.97
   122.9 1664.37   134.9 1666.39   142.9 1667.33   150.9 1667.36   162.9 1667.86
   192.6 1668.19   222.9 1668.24   244.1 1667.95   266.9 1668.97   289.3 1671.06
#Mann= 5 ,-1,0
       0     .06       0      60     .05       0      93    .045       0
   106.8     .05       0     260     .06       0
Bank Sta=93,106.8
XS Rating Curve= 0 ,0
Exp/Cntr(USF)=0,0
Exp/Cntr=0.3,0.1

Type RM Length L Ch R = 1 ,57446   ,213.5,220.5,227.6
XS GIS Cut Line= 4
2207644.28865802704380.5123467192207764.14060626 704373.85390515
2208088.73963274704225.7035802452208263.52372392704080.882476124
#Sta/Elev= 30
       0 1703.79    23.9 1694.16    27.9 1691.99    31.9  1688.9    35.9 1686.97
      52  1686.8      56 1685.45    67.6 1679.47      96 1669.59   112.1 1665.68
   142.1  1660.2     164  1658.7  171.511656.629   177.2 1655.97   181.6 1656.61
     186 1658.46   190.4 1658.91   212.4 1658.24   310.8 1658.22   339.9 1657.37
   361.9 1658.15   392.3 1657.26   410.3 1659.06   419.5 1662.07   443.6 1666.73
   483.9 1677.05   502.7 1681.01   559.2 1692.13   644.4 1705.73   703.8 1720.82
#Mann= 5 ,-1,0
       0      .1       0      70     .06       0  171.51    .045       0
   181.6     .05       0  506.85      .1       0
Bank Sta=171.51,181.6
XS Rating Curve= 0 ,0
Exp/Cntr(USF)=0,0
Exp/Cntr=0.3,0.1

Type RM Length L Ch R = 1 ,57226   ,299.8,314.8,316.2
XS GIS Cut Line= 3
2207636.61057345704421.3848915592208247.22213387704473.943861317
2208471.37068136704286.895763061
#Sta/Elev= 30
       0 1706.78    15.6  1699.7    35.7 1692.82    39.7    1690    43.7 1686.04
    47.7 1684.61    59.8 1684.79    63.8 1683.81    71.8 1679.48    91.9 1672.84
   160.2 1658.31   168.2 1657.72   280.3 1657.34   336.8 1657.78   340.8 1657.64
   346.8 1656.11   352.9 1654.52   356.9 1654.73   360.9 1656.18   364.9 1657.05
     393 1657.84   477.3 1657.15   497.4 1658.33   662.4 1661.77   676.6 1663.76
   718.3  1672.2   733.9 1673.94   820.1 1687.63   853.8 1693.97   904.8 1701.86
#Mann= 6 ,-1,0
       0      .1       0      80     .06       0     280     .05       0
   346.8    .045       0   360.9     .05       0  752.87      .1       0
Bank Sta=346.8,360.9
XS Rating Curve= 0 ,0
Exp/Cntr(USF)=0,0
Exp/Cntr=0.3,0.1

Type RM Length L Ch R = 1 ,56911   ,341.6,343.4,335.1
XS GIS Cut Line= 4
2207623.27789397704463.9695703262207756.36561792704517.204659907
2207940.02667698704770.0713354192208015.22124101704937.096428981
#Sta/Elev= 30
       0 1705.51    35.4 1692.35      44 1689.88    48.4 1686.93    52.7 1682.49
      57 1681.07    72.4 1680.53    82.8 1676.66   104.4 1670.94   148.3 1663.15
   170.2 1657.14   203.3 1656.18   226.2 1656.98   231.21655.731   237.7 1654.21
  243.98 1655.72   251.9 1656.95   276.8 1657.67   415.2 1657.62   423.8 1658.32
   439.9 1661.57   449.8 1662.03     466 1666.88   485.6 1670.34   498.8 1673.98
   507.5 1675.35     534 1683.48   585.4 1702.54   621.7 1717.99     639 1723.52
#Mann= 7 ,-1,0
       0      .1       0      70     .05       0     100     .06       0
   231.2    .045       0  243.98     .05       0  413.34     .06       0
  475.87      .1       0
Bank Sta=231.2,243.98
XS Rating Curve= 0 ,0
Exp/Cntr(USF)=0,0
Exp/Cntr=0.3,0.1

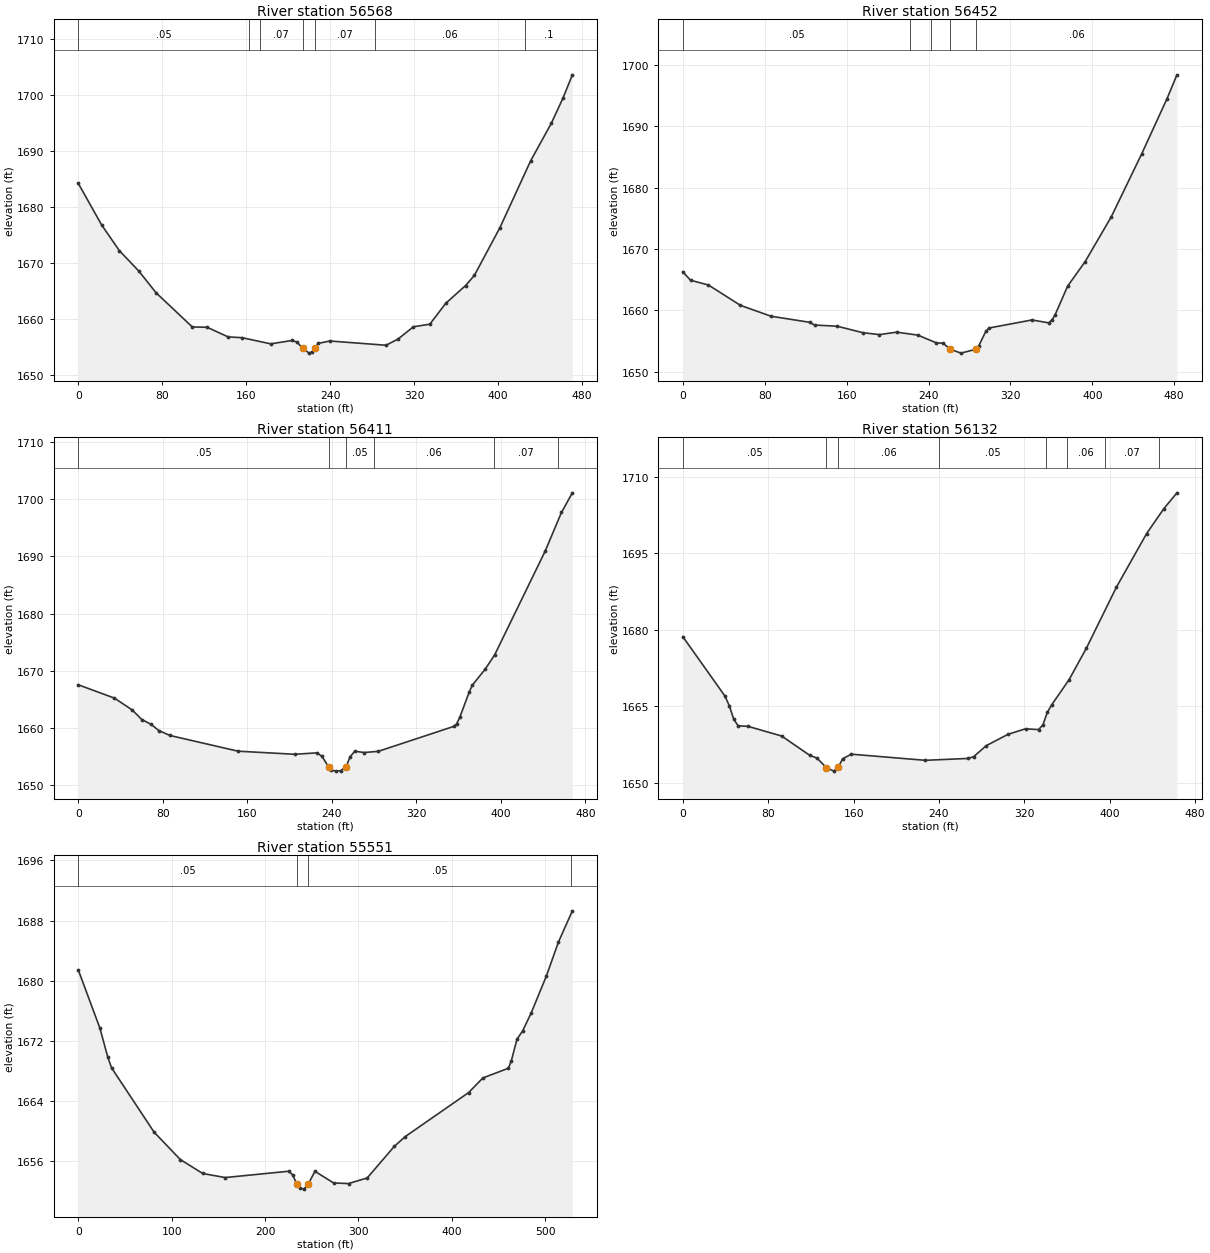
Type RM Length L Ch R = 1 ,56568   ,98.8,115.6,122.5
XS GIS Cut Line= 4
 2207529.7155798704648.5218126242207564.77227466704734.815215355
2207772.41577498704895.2670110592207838.48416145704989.650420296
#Sta/Elev= 30
       0 1684.24    22.3 1676.78    39.2 1672.18    57.7 1668.54    74.1 1664.66
   108.7 1658.53   122.7 1658.48   142.9 1656.75   155.9 1656.62   183.4 1655.51
   203.6 1656.11   208.2 1655.84   213.7 1654.78   219.9 1653.85   222.7 1654.06
   225.6 1654.83   228.9  1655.6   239.8 1656.02   293.3 1655.26   304.7 1656.37
   319.4 1658.57     335 1659.03   350.2 1662.77   369.1 1665.95   377.4 1667.75
   401.8 1676.31   431.1 1688.28   450.7 1694.96     462 1699.55   470.8 1703.65
#Mann= 7 ,-1,0
       0     .05       0  163.14     .06       0  173.14     .07       0
   213.7    .045       0   225.6     .07       0  283.14     .06       0
  425.56      .1       0
Bank Sta=213.7,225.6
XS Rating Curve= 0 ,0
Exp/Cntr(USF)=0,0
Exp/Cntr=0.3,0.1

Type RM Length L Ch R = 1 ,56452   ,45.9,41.2,40.6
XS GIS Cut Line= 4
2207450.11444053704741.7359646492207594.27835646704816.002224372
2207692.57193551705052.9989649582207743.90302678705091.224245698
#Sta/Elev= 30
       0 1666.26     7.5 1664.89      25 1664.11    56.3 1660.79    86.1 1659.02
   123.8 1658.03   128.8 1657.58   150.8 1657.39   175.6 1656.34   192.1 1656.02
   208.9 1656.42   229.8 1655.93   247.2  1654.7   254.4  1654.6   261.1 1653.64
   271.7    1653   286.21653.625     289 1654.16   296.1 1656.59   299.2  1657.1
     341 1658.41   357.4 1657.94   360.4 1658.37   363.5 1659.18   375.9 1663.92
     393 1667.92   418.6 1675.25   448.2 1685.48   472.9 1694.46   482.7 1698.39
#Mann= 5 ,-1,0
       0     .05       0  222.17     .07       0  242.17     .06       0
   261.1    .045       0   286.2     .06       0
Bank Sta=261.1,286.2
XS Rating Curve= 0 ,0
Exp/Cntr(USF)=0,0
Exp/Cntr=0.3,0.1

Type RM Length L Ch R = 1 ,56411   ,289.9,278.9,268.2
XS GIS Cut Line= 4
2207438.10078087 704785.421999782207554.96092484704842.213845451
2207668.54461618705080.3027369152207731.88936712705118.528017655
#Sta/Elev= 30
       0 1667.57    34.3 1665.24    51.2 1663.16    60.1 1661.51      69 1660.66
    76.2 1659.59    86.8 1658.72   151.3 1655.98   205.1 1655.44   226.1 1655.69
   230.7 1655.07  236.971653.242   239.6 1652.67     244  1652.5   248.4 1652.57
   253.5 1653.26   257.3 1654.99   261.7 1655.97   270.6 1655.75   283.9 1655.95
   355.7 1660.32   358.1 1660.74   361.1 1661.86   370.1 1666.33   373.1 1667.53
   385.1 1670.27   394.1 1672.77   441.9 1690.87   457.4 1697.65   467.7 1701.07
#Mann= 6 ,-1,0
       0     .05       0  236.97    .045       0   253.5     .05       0
  279.93     .06       0  393.72     .07       0  453.72     .06       0
Bank Sta=236.97,253.5
XS Rating Curve= 0 ,0
Exp/Cntr(USF)=0,0
Exp/Cntr=0.3,0.1

Type RM Length L Ch R = 1 ,56132   ,579.3,581.3,576.9
XS GIS Cut Line= 3
2207285.40489609 705107.928789962207644.22091397705180.061906955
2207740.39840329705167.114937238
#Sta/Elev= 30
       0 1678.67    39.5 1667.02    43.6 1665.11    47.7  1662.5    51.8 1661.21
    61.2 1661.09    92.6  1659.2   118.9 1655.42   125.7 1654.88   134.51653.009
   141.5 1652.32   145.6 1653.04   149.7 1654.74   157.9 1655.64   227.2 1654.44
   267.5 1654.81   272.6 1655.17   284.3 1657.31   304.7 1659.53   321.1 1660.62
   333.3 1660.46   337.4 1661.38   341.5 1663.81   345.5 1665.28   361.9 1670.23
   378.1  1676.4   406.3 1688.38   434.6 1698.88   450.7 1703.75     463 1706.86
#Mann= 8 ,-1,0
       0     .05       0   134.5    .045       0   145.6     .06       0
     240     .05       0     340     .07       0     360     .06       0
  395.99     .07       0  445.99     .06       0
Bank Sta=134.5,145.6
XS Rating Curve= 0 ,0
Exp/Cntr(USF)=0,0
Exp/Cntr=0.3,0.1

Type RM Length L Ch R = 1 ,55551   ,251,259.9,264.7
XS GIS Cut Line= 4
2207305.75013422705664.6484877942207388.98065383705642.453682565
2207710.80532965705636.904981258 2207821.7793558705588.816236594
#Sta/Elev= 30
       0 1681.44    23.2 1673.68    31.5 1669.88    35.6 1668.42    81.2 1659.85
   109.3  1656.2   133.3 1654.35   157.3 1653.81   225.4 1654.65   229.4 1654.18
     2341652.955   237.4 1652.39   241.4 1652.27  246.311652.947   253.4 1654.64
   273.4 1653.09   289.4 1653.01   309.4 1653.76   338.3 1657.95   350.1 1659.26
     418 1665.12   433.2 1667.06   460.5 1668.35   463.6 1669.31   469.7 1672.21
   475.8 1673.32   484.9  1675.7   501.1 1680.59   514.1 1685.14     529 1689.29
#Mann= 4 ,-1,0
       0     .05       0     234    .045       0  246.31     .05       0
  528.01     .07       0
Bank Sta=234,246.31
XS Rating Curve= 0 ,0
Exp/Cntr(USF)=0,0
Exp/Cntr=0.3,0.1