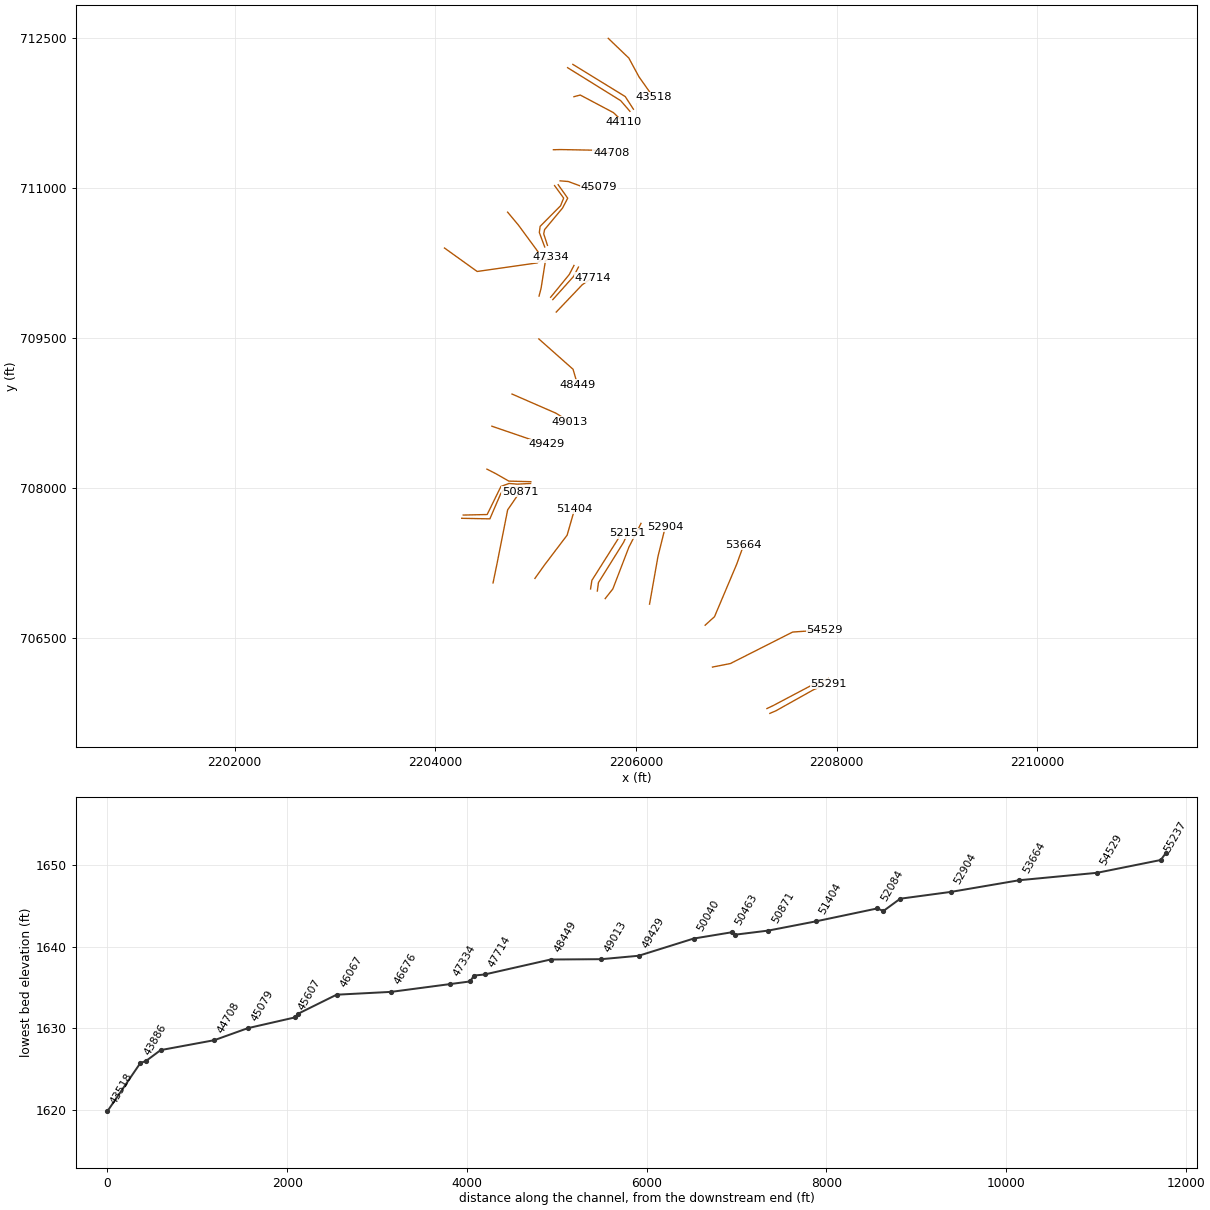
HEC-RAS study SANDRN1.prj: SANDRN1

--- SANDRN1.g01 (geometry) --- (continued)

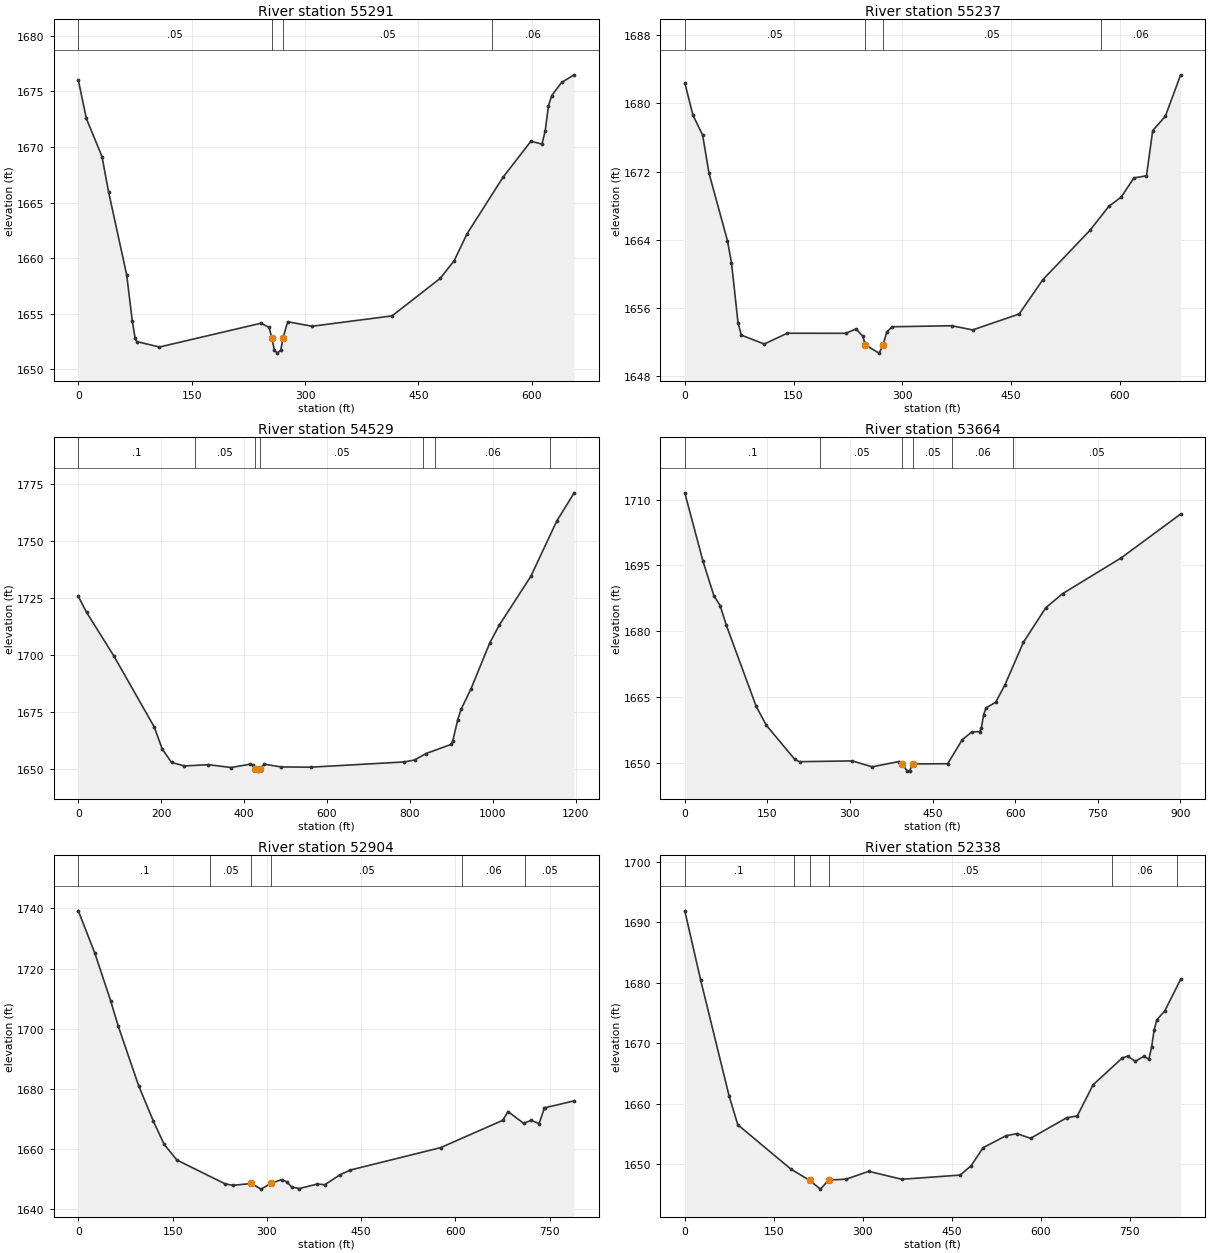
Type RM Length L Ch R = 1 ,55291   ,55.3,53.9,53.6
XS GIS Cut Line= 4
2207335.43859831705751.9755270572207396.59904749705778.187148136
2207772.29894962705988.9722676442207919.73931819706047.948415071
#Sta/Elev= 30
       0 1676.01    10.6 1672.57    31.3 1669.14      40 1665.97      64 1658.49
    71.4 1654.35    75.2 1652.79    77.2  1652.5   107.3 1652.01   241.8 1654.15
   252.5 1653.77   256.1  1652.8   259.4 1651.74   263.3 1651.46   267.9 1651.73
   270.81652.822     277 1654.28   309.4 1653.88   415.1 1654.81   478.8 1658.18
   497.4 1659.78   514.4  1662.2     562 1667.28   598.9 1670.52   613.5 1670.26
   617.8 1671.46   622.1 1673.71   626.4 1674.62   639.4  1675.8   656.1 1676.49
#Mann= 4 ,-1,0
       0     .05       0   256.1    .045       0   270.8     .05       0
  547.33     .06       0
Bank Sta=256.1,270.8
XS Rating Curve= 0 ,0
Exp/Cntr(USF)=0,0
Exp/Cntr=0.3,0.1

Type RM Length L Ch R = 1 ,55237   ,694.7,707.9,703.9
XS GIS Cut Line= 4
2207305.95052459705800.030165702 2207366.0188229705828.426088537
2207735.16581976706023.9210957492207919.73931819706100.371657229
#Sta/Elev= 30
       0 1682.43    11.3 1678.62    24.6 1676.28    33.4  1671.8    58.8 1663.88
    64.4 1661.28    73.4 1654.24    77.9 1652.77   109.6 1651.72   141.3 1652.99
   221.9 1652.98   236.4 1653.49   245.4 1652.64   249.1 1651.61     268 1650.65
  273.38 1651.59   278.7 1653.15   286.1 1653.75   368.1 1653.87   397.1 1653.38
   461.2 1655.25   493.9 1659.29   558.9 1665.09   584.8  1667.9     602 1669.01
   619.5 1671.25   636.8  1671.5   645.4 1676.82   662.8 1678.49   683.9 1683.37
#Mann= 4 ,-1,0
       0     .05       0   249.1    .045       0  273.38     .05       0
  574.16     .06       0
Bank Sta=249.1,273.38
XS Rating Curve= 0 ,0
Exp/Cntr(USF)=0,0
Exp/Cntr=0.3,0.1

Type RM Length L Ch R = 1 ,54529   ,835.8,865.2,861.9
XS GIS Cut Line= 4
2206763.63573183706214.4286805392206941.74904379706249.385498776
2207562.64872008706563.9968629012207880.58930499706585.636797999
#Sta/Elev= 30
       0 1725.63    19.8 1718.62    86.2 1699.35   183.2  1668.4   202.2 1658.84
   224.8 1652.88     256 1651.35   313.8 1651.91   368.1 1650.66   414.7 1652.11
   421.9  1651.6   426.4 1650.15   433.2 1649.08  437.871650.206   448.8 1652.12
   489.2 1650.92   560.9 1650.81   785.1 1653.09   811.1 1653.94   838.9 1656.79
   899.1 1660.76   903.2 1662.18   915.2  1671.5   923.2 1676.09   947.3  1685.1
   992.7 1705.24  1015.2 1712.92  1091.6 1734.33  1154.1 1758.53  1196.2 1770.92
#Mann= 7 ,-1,0
       0      .1       0  281.51     .05       0   426.4    .045       0
  437.87     .05       0  831.51     .08       0  861.51     .06       0
 1137.57      .1       0
Bank Sta=426.4,437.87
XS Rating Curve= 0 ,0
Exp/Cntr(USF)=0,0
Exp/Cntr=0.3,0.1

Type RM Length L Ch R = 1 ,53664   ,749.7,759,757.2
XS GIS Cut Line= 4
2206690.28385648706632.3170221762206783.50203844706717.212152178
 2207004.8952206 707241.564425722207074.80885708707434.659231215
#Sta/Elev= 30
       0 1711.54    33.1 1695.94    52.9 1688.11    64.2 1685.87    75.6 1681.33
   129.6 1662.95   147.9 1658.65   199.8 1650.84   208.5 1650.32   304.1  1650.5
   340.3 1649.15   389.1 1650.36   395.3  1649.8   403.9 1648.17   408.3 1648.26
  414.06 1649.81   477.5 1649.86   503.8  1655.3   521.2 1657.08   535.7 1657.18
   538.5 1657.89   542.9 1661.06   547.2 1662.57   564.6 1663.84   581.5  1667.8
     615 1677.51   655.8 1685.39   686.2 1688.58   792.7 1696.73   900.6 1706.71
#Mann= 6 ,-1,0
       0      .1       0  246.08     .05       0   395.3    .045       0
  414.06     .05       0  486.08     .06       0  596.08     .05       0
Bank Sta=395.3,414.06
XS Rating Curve= 0 ,0
Exp/Cntr(USF)=0,0
Exp/Cntr=0.3,0.1

Type RM Length L Ch R = 1 ,52904   ,551.4,566.4,532.1
XS GIS Cut Line= 3
2206136.11533557706842.6944278112206219.49259487707316.336913827
2206293.53107241707615.391897899
#Sta/Elev= 30
       0 1739.18    26.4 1725.03    51.3 1709.38    63.4 1700.96    95.9 1681.14
   119.6 1669.22   136.6  1661.6   156.9  1656.4   233.6 1648.49   246.2    1648
     275 1648.61   290.9 1646.74  306.59 1648.67   323.4 1649.91   331.5 1649.17
   339.6 1647.45   351.8 1646.93   380.2 1648.43   392.4 1648.22   416.6 1651.53
     433 1653.09   576.6 1660.53   675.5 1669.61   683.7 1672.52   708.4 1668.62
   720.8 1669.58   733.2  1668.5   741.4 1673.56   743.1  1673.8     789 1676.06
#Mann= 6 ,-1,0
       0      .1       0     210     .05       0     275    .045       0
  306.59     .05       0  610.93     .06       0  710.93     .05       0
Bank Sta=275,306.59
XS Rating Curve= 0 ,0
Exp/Cntr(USF)=0,0
Exp/Cntr=0.3,0.1

Type RM Length L Ch R = 1 ,52338   ,183.1,187.3,178
XS GIS Cut Line= 5
2205693.93120334706897.8723091182205770.38176482706994.952387191
2205930.56389364707412.3967229032206003.37395219707554.376337084
2206050.70049025707649.029413205
#Sta/Elev= 30
       0 1691.87    26.7 1680.46    74.7  1661.3    89.4 1656.53   179.3 1649.18
   210.3 1647.36   228.8  1645.9   242.5 1647.39   272.2 1647.55   310.2 1648.84
   365.9 1647.53   464.4 1648.22   482.8 1649.76     503 1652.74   541.5 1654.72
   560.2 1655.07     583 1654.29   643.8 1657.68   661.9    1658   688.4 1663.13
   737.9 1667.58   746.8 1667.86   759.8 1667.01   773.6 1667.82   782.6 1667.39
   787.1 1669.33   791.5 1672.23     796 1673.87   809.4 1675.35   836.1 1680.55
#Mann= 6 ,-1,0
       0      .1       0  183.57     .05       0   210.3    .045       0
   242.5     .05       0  720.69     .06       0  830.25     .05       0
Bank Sta=210.3,242.5
XS Rating Curve= 0 ,0
Exp/Cntr(USF)=0,0
Exp/Cntr=0.3,0.1

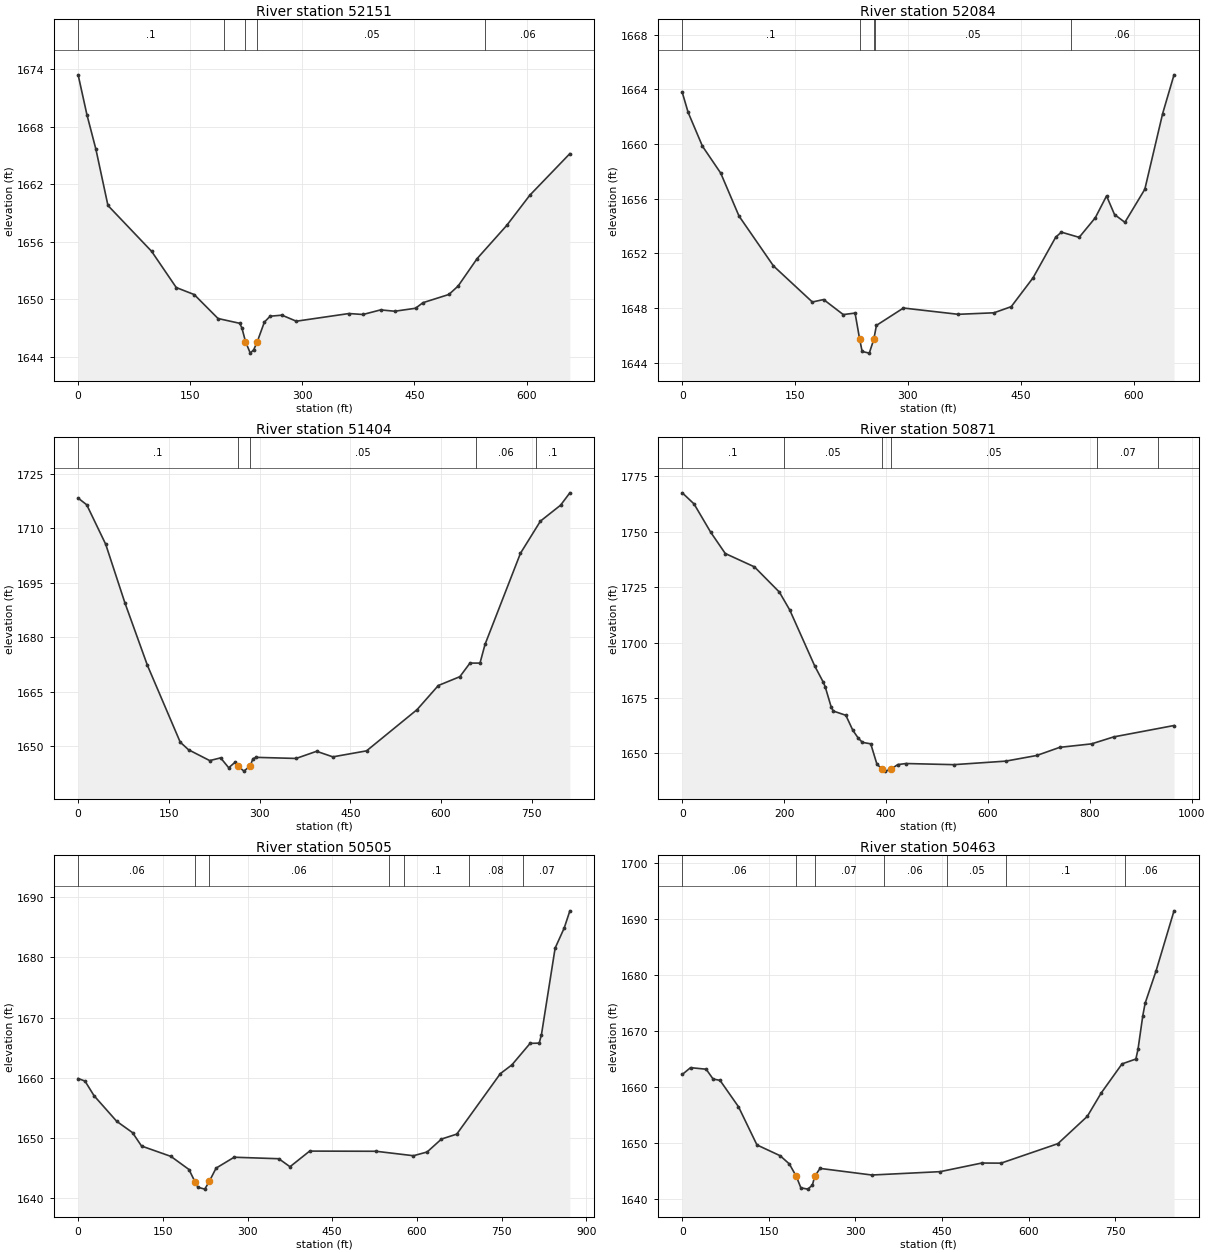
Type RM Length L Ch R = 1 ,52151   ,66.7,66.5,66.4
XS GIS Cut Line= 4
2205615.68828227706973.5964476482205626.60979105707057.692065276
2205877.80449306707460.6957393612205918.21407555 707550.25211138
#Sta/Elev= 30
       0 1673.42    11.7 1669.28    23.8 1665.65    39.9 1659.79    98.3 1655.01
   131.3 1651.23   155.3  1650.5   187.2    1648   216.2  1647.5   219.1 1647.02
   223.9  1645.6   230.3 1644.39     235 1644.75   239.7 1645.59   249.2 1647.63
   256.9 1648.24   272.7 1648.35   291.9 1647.72   362.3 1648.52   381.1 1648.42
   404.7  1648.9   423.6 1648.76   451.4 1649.07   461.3 1649.65   496.1 1650.51
   508.4 1651.39   533.9 1654.26   573.4 1657.71   604.3 1660.86   657.9  1665.2
#Mann= 5 ,-1,0
       0      .1       0   194.8     .05       0   223.9    .045       0
   239.7     .05       0   544.8     .06       0
Bank Sta=223.9,239.7
XS Rating Curve= 0 ,0
Exp/Cntr(USF)=0,0
Exp/Cntr=0.3,0.1

Type RM Length L Ch R = 1 ,52084   ,656.8,680.5,662.7
XS GIS Cut Line= 4
2205548.18384924706994.6281037572205561.28965978707079.815872262
2205816.85296529707485.0038481042205859.44684955707562.546560462
#Sta/Elev= 30
       0 1663.78     7.8 1662.32    26.8 1659.85    51.1 1657.88    75.4 1654.74
   121.2 1651.09   172.9 1648.45   187.9 1648.63     214 1647.53   229.7 1647.64
  235.671645.771   239.1 1644.83   248.6 1644.71   254.6 1645.72   258.1 1646.74
     294 1648.01   366.8 1647.55   414.3 1647.66   437.3 1648.11   466.3 1650.22
   496.5  1653.2     504 1653.56   527.6 1653.18     549 1654.61     564 1656.21
   574.6 1654.85   588.4 1654.28   614.9  1656.7   638.6 1662.24   653.7 1665.07
#Mann= 5 ,-1,0
       0      .1       0  235.67    .045       0   254.6      .1       0
  256.19     .05       0  516.19     .06       0
Bank Sta=235.67,254.6
XS Rating Curve= 0 ,0
Exp/Cntr(USF)=0,0
Exp/Cntr=0.3,0.1

Type RM Length L Ch R = 1 ,51404   ,526.1,532.9,537.5
XS GIS Cut Line= 4
2204993.77040717707099.7558215932205085.84874668707229.229657362
2205314.58751695707531.4121680792205390.29787575707796.074135175
#Sta/Elev= 30
       0 1718.29    14.2 1716.45    45.6 1705.58    77.3 1689.48   114.6 1672.24
   168.8 1651.11   182.6 1649.01   217.6 1646.03   235.6 1646.78     249 1644.06
   259.1 1645.52   264.2 1644.52   274.2 1643.13   284.2 1644.53   289.2 1646.56
   294.3 1646.92   360.4 1646.62   394.3 1648.59   421.2 1647.06   476.9 1648.71
   560.5 1660.07   595.6  1666.7   631.2 1669.13   647.9 1672.87   664.5 1672.87
   672.8 1678.01   731.4  1703.1   764.4 1711.95   797.7 1716.33   813.1 1719.74
#Mann= 5 ,-1,0
       0      .1       0   264.2    .045       0   284.2     .05       0
  657.87     .06       0  757.87      .1       0
Bank Sta=264.2,284.2
XS Rating Curve= 0 ,0
Exp/Cntr(USF)=0,0
Exp/Cntr=0.3,0.1

Type RM Length L Ch R = 1 ,50871   ,381.3,365.7,339.1
XS GIS Cut Line= 4
2204576.04716094 707054.526536212204617.30619412707254.754197234
2204721.66727804 707783.840622732204846.84265032707966.749677234
#Sta/Elev= 30
       0 1767.57    23.1 1762.56    55.8 1749.79    84.4 1740.19   141.6 1734.17
   190.6 1722.78     211  1714.7     260 1689.45   276.2 1682.39   280.5 1680.12
   292.5  1670.8   296.6 1669.09   321.1 1667.19   334.9 1660.39   345.5 1656.88
   353.7 1654.96     370 1654.31   382.2 1645.08   392.31642.938   398.5 1641.99
   409.9 1642.91     423 1644.94   439.3 1645.42   533.1 1644.91     635  1646.5
   695.9 1649.05     741 1652.72   803.5 1654.29   847.1 1657.44   965.4 1662.57
#Mann= 6 ,-1,0
       0      .1       0     200     .05       0   392.3    .045       0
   409.9     .05       0  813.72     .07       0  933.72     .08       0
Bank Sta=392.3,409.9
XS Rating Curve= 0 ,0
Exp/Cntr(USF)=0,0
Exp/Cntr=0.3,0.1

Type RM Length L Ch R = 1 ,50505   ,41.2,42.3,44
XS GIS Cut Line= 6
2204263.93621866707699.6228115632204544.38977753707694.229473893
2204653.60486536707947.7163444082204691.35822905707996.256383443
2204745.29160575708007.0430587842204942.14843073708009.739727619
#Sta/Elev= 30
       0 1659.87    12.2 1659.44    28.2 1657.01    68.3 1652.76    96.3 1650.88
   112.3 1648.65   164.3 1646.93   196.3 1644.75   206.7 1642.75   212.3 1641.79
   224.3 1641.49   232.3 1642.78   244.3 1644.98   276.3 1646.79   355.4 1646.54
   375.2 1645.21     410 1647.81   527.6 1647.78   593.8 1647.04     618 1647.66
   643.4 1649.81   670.5 1650.63   747.7 1660.68   768.2 1662.14   800.4 1665.71
   816.5 1665.75   820.5 1667.17   844.7 1681.54   860.8 1684.88   870.8 1687.73
#Mann= 7 ,-1,0
       0     .06       0   206.7    .045       0   232.3     .06       0
  550.51     .05       0  576.52      .1       0  693.01     .08       0
  787.74     .07       0
Bank Sta=206.7,232.3
XS Rating Curve= 0 ,0
Exp/Cntr(USF)=0,0
Exp/Cntr=0.3,0.1

Type RM Length L Ch R = 1 ,50463   ,430.3,423,407
XS GIS Cut Line= 6
2204278.76789725707731.9828375872204517.42308917707737.376175257
2204654.95319977708017.8297341252204735.85326483708047.493091313
2204818.10166431708040.7514192242204950.23843723708047.493091313
#Sta/Elev= 30
       0 1662.25    14.3 1663.47    41.4 1663.19    53.4 1661.44    65.4  1661.2
    97.4 1656.49   129.4 1649.67   169.5 1647.75   185.5 1646.28   197.5 1644.08
   205.5 1642.01   217.5 1641.78   225.4 1642.49   229.5 1644.06   229.5 1644.07
   238.7 1645.48   328.5  1644.3   446.9  1644.9     519 1646.44   552.4 1646.42
   650.9  1649.9   701.8 1654.77   725.9 1658.94     762 1664.14     786 1665.01
   789.7 1666.75     798 1672.75     802 1674.96   821.1 1680.78   852.1 1691.47
#Mann= 7 ,-1,0
       0     .06       0   197.5    .045       0   229.5     .07       0
  348.72     .06       0  458.72     .05       0  561.12      .1       0
  767.66     .06       0
Bank Sta=197.5,229.5
XS Rating Curve= 0 ,0
Exp/Cntr(USF)=0,0
Exp/Cntr=0.3,0.1

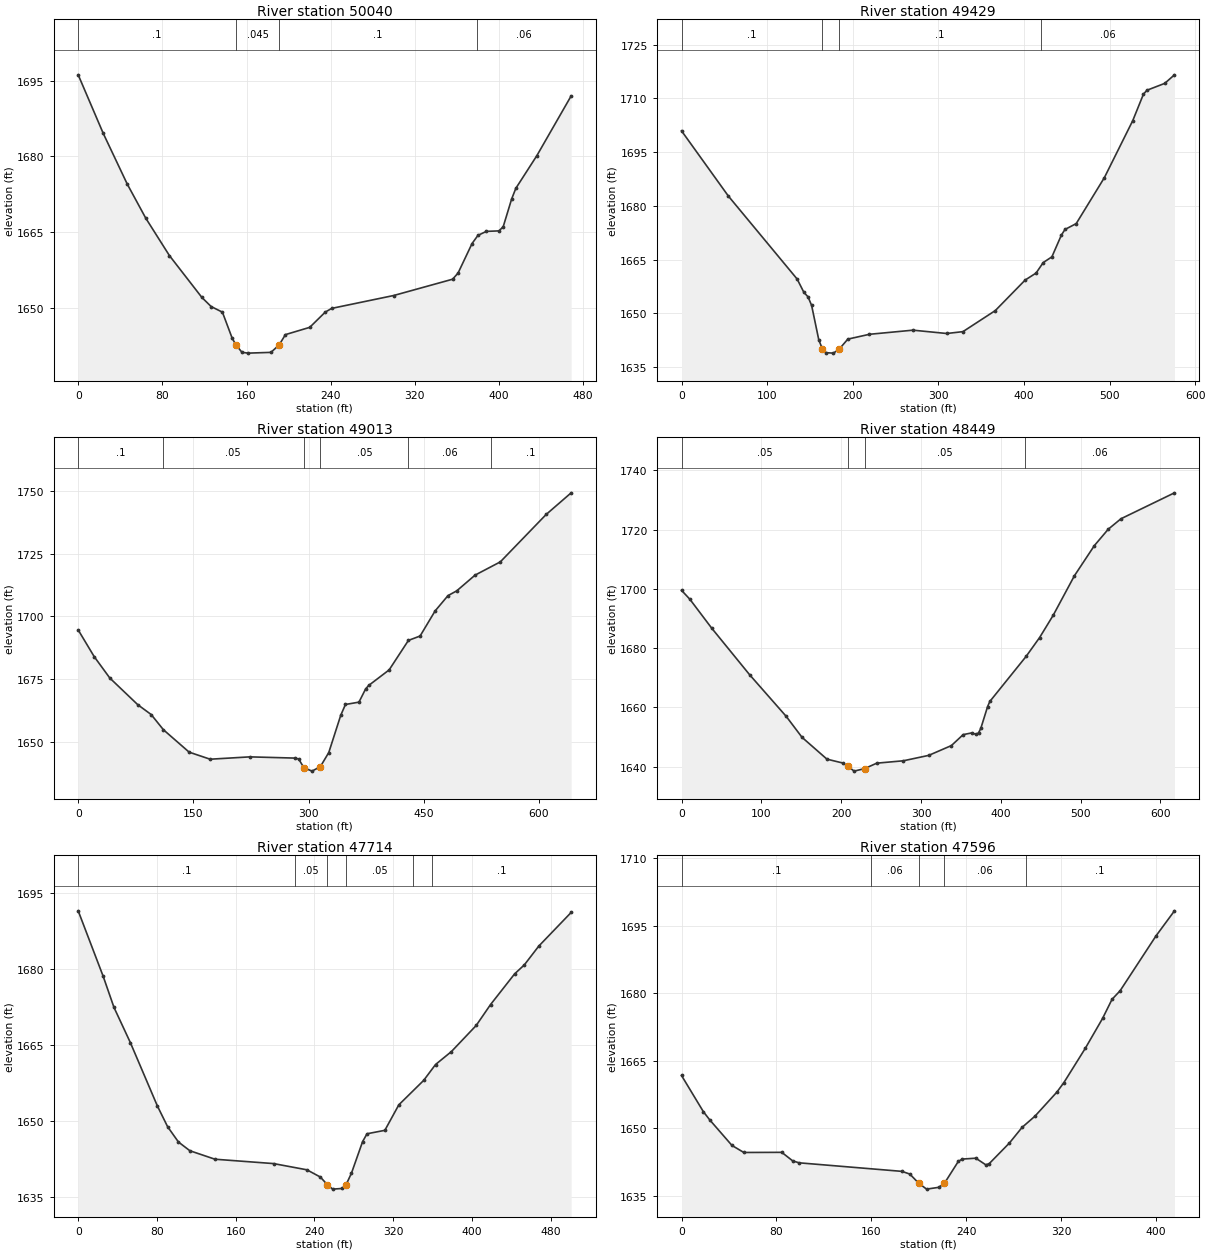
Type RM Length L Ch R = 1 ,50040   ,600.2,611,612.1
XS GIS Cut Line= 4
2204514.95195717708190.5939388152204602.02032533 708146.17561351
2204733.48880458708070.9255846892204952.77023403708065.195905344
#Sta/Elev= 30
       0 1696.17    23.8 1684.57    46.6 1674.53    64.2 1667.77    86.7 1660.35
   117.6 1652.04   126.4 1650.24   137.1 1649.13   146.3 1644.01   149.81642.679
   155.7 1641.17   161.6 1641.01   183.2 1641.16     1911642.627     197 1644.68
   220.1 1646.12   234.9 1649.15     241 1649.88   299.9 1652.43   355.9 1655.66
   361.1 1656.88   374.4 1662.73     380 1664.35     388 1665.14     400 1665.24
     404 1666.06     412 1671.54     416 1673.67     436 1680.15   468.6 1691.99
#Mann= 4 ,-1,0
       0      .1       0   149.8    .045       0     191      .1       0
  379.23     .06       0
Bank Sta=149.8,191
XS Rating Curve= 0 ,0
Exp/Cntr(USF)=0,0
Exp/Cntr=0.3,0.1

Type RM Length L Ch R = 1 ,49429   ,416.4,416.3,415.3
XS GIS Cut Line= 3
2204564.39206972708619.0650059732205002.12295063 708469.04456322
2205111.04190221708438.218444846
#Sta/Elev= 30
       0 1700.97    54.8 1682.73   135.1 1659.58     143 1655.85   147.8 1654.62
     152 1652.22   160.4 1642.58   164.7    1640   168.9 1639.02   177.4  1638.9
     184 1639.95   194.3 1642.81   219.6 1644.16   270.4 1645.31   309.9 1644.38
   328.8  1644.9   366.6 1650.78   401.5 1659.31   414.2 1661.25   422.6 1664.19
   432.7 1665.78   443.8 1671.86     448 1673.43   461.1 1675.06     494 1687.89
   527.2 1703.83   539.7 1711.23   543.8  1712.3   564.5 1714.21   575.9  1716.6
#Mann= 4 ,-1,0
       0      .1       0   164.7    .045       0     184      .1       0
     420     .06       0
Bank Sta=164.7,184
XS Rating Curve= 0 ,0
Exp/Cntr(USF)=0,0
Exp/Cntr=0.3,0.1

Type RM Length L Ch R = 1 ,49013   ,566.8,563.4,557
XS GIS Cut Line= 3
2204765.10224366708940.3030540132205202.83312457708749.181120095
2205342.57819454708662.867988648
#Sta/Elev= 30
       0 1694.62    20.8 1684.03    41.2 1675.49    77.6 1664.89      95 1660.99
     111 1654.93   144.5 1646.02   171.8 1643.22   223.5 1644.15   282.7 1643.66
   287.1  1643.3   293.91639.832   304.5 1638.48   315.41640.292   326.3 1645.88
   341.9  1660.7     348 1664.98   365.6 1665.91   374.3 1671.18   378.4 1672.58
   404.9 1678.73     430 1690.46   445.2  1692.2   464.7 1702.15   481.5 1708.26
   492.9 1710.16   516.8 1716.42   549.7 1721.69   609.4 1740.55   641.9 1749.14
#Mann= 6 ,-1,0
       0      .1       0     110     .05       0   293.9    .045       0
   315.4     .05       0     430     .06       0  537.64      .1       0
Bank Sta=293.9,315.4
XS Rating Curve= 0 ,0
Exp/Cntr(USF)=0,0
Exp/Cntr=0.3,0.1

Type RM Length L Ch R = 1 ,48449   ,712.7,735.5,755.6
XS GIS Cut Line= 3
2205032.34646377709490.5897524552205373.59159417709187.630661077
2205418.53607475709032.821894604
#Sta/Elev= 30
       0 1699.48    10.5 1696.45    37.7 1686.74    85.4 1670.95   131.2 1656.91
     151 1649.84   182.2 1642.48   202.1 1641.17   208.81640.034   216.2 1638.44
   229.41639.292   244.6 1641.13   277.9 1641.93   309.7 1643.76   338.1 1647.07
   352.8 1650.76   363.5 1651.34   369.2 1650.84   372.1 1651.38   374.9 1652.85
   383.4 1660.21   386.2 1661.95   431.6 1677.14   448.6 1683.54   465.6 1691.05
   492.2  1704.4   517.2 1714.58   534.6 1720.11   550.5 1723.63   617.5 1732.38
#Mann= 4 ,-1,0
       0     .05       0   208.8    .045       0   229.4     .05       0
     430     .06       0
Bank Sta=208.8,229.4
XS Rating Curve= 0 ,0
Exp/Cntr(USF)=0,0
Exp/Cntr=0.3,0.1

Type RM Length L Ch R = 1 ,47714   ,117.2,117.9,118.5
XS GIS Cut Line= 3
2205205.98843134709758.7991031842205465.16826941710031.462285424
2205567.04242541710103.373454367
#Sta/Elev= 30
       0  1691.5    25.4 1678.58    36.4 1672.43      53 1665.51    80.5 1652.99
    90.9  1648.9   101.9 1645.89   113.5 1644.17     139  1642.5   198.5 1641.64
   232.4 1640.41   246.1 1638.98   253.31637.443   258.6  1636.6   268.2 1636.73
     272 1637.38   277.7 1639.76     289 1645.98   293.5 1647.52   311.6  1648.2
   325.8 1653.23     351 1658.04   363.1 1661.18   379.2 1663.73   404.4 1668.88
     419 1673.01   443.5 1679.07   453.3 1680.83     468 1684.54   500.9 1691.18
#Mann= 6 ,-1,0
       0      .1       0     220     .05       0   253.3    .045       0
     272     .05       0     340     .06       0     360      .1       0
Bank Sta=253.3,272
XS Rating Curve= 0 ,0
Exp/Cntr(USF)=0,0
Exp/Cntr=0.3,0.1

Type RM Length L Ch R = 1 ,47596   ,40.7,41.7,42.4
XS GIS Cut Line= 3
2205171.82302432709883.3660630062205378.23954031710113.809898324
2205427.38632984710207.734873857
#Sta/Elev= 30
       0 1661.74    18.5 1653.66    23.9 1651.83    42.5 1646.19    52.5 1644.62
    84.5 1644.65    93.7 1642.75    99.1 1642.32   185.7 1640.42   192.4 1639.82
   199.8 1637.81   206.5 1636.47   216.8 1636.87  221.571637.772   233.3 1642.65
   236.6 1643.15     248 1643.35   256.5 1641.86   259.3 1642.14   276.3 1646.72
     287  1650.2   297.8 1652.68   316.3 1658.04   322.2 1660.15   340.3  1667.8
   354.8 1674.42   362.8 1678.68   369.6 1680.58   399.8 1692.76   415.4 1698.35
#Mann= 5 ,-1,0
       0      .1       0     160     .06       0   199.8    .045       0
  221.57     .06       0     290      .1       0
Bank Sta=199.8,221.57
XS Rating Curve= 0 ,0
Exp/Cntr(USF)=0,0
Exp/Cntr=0.3,0.1

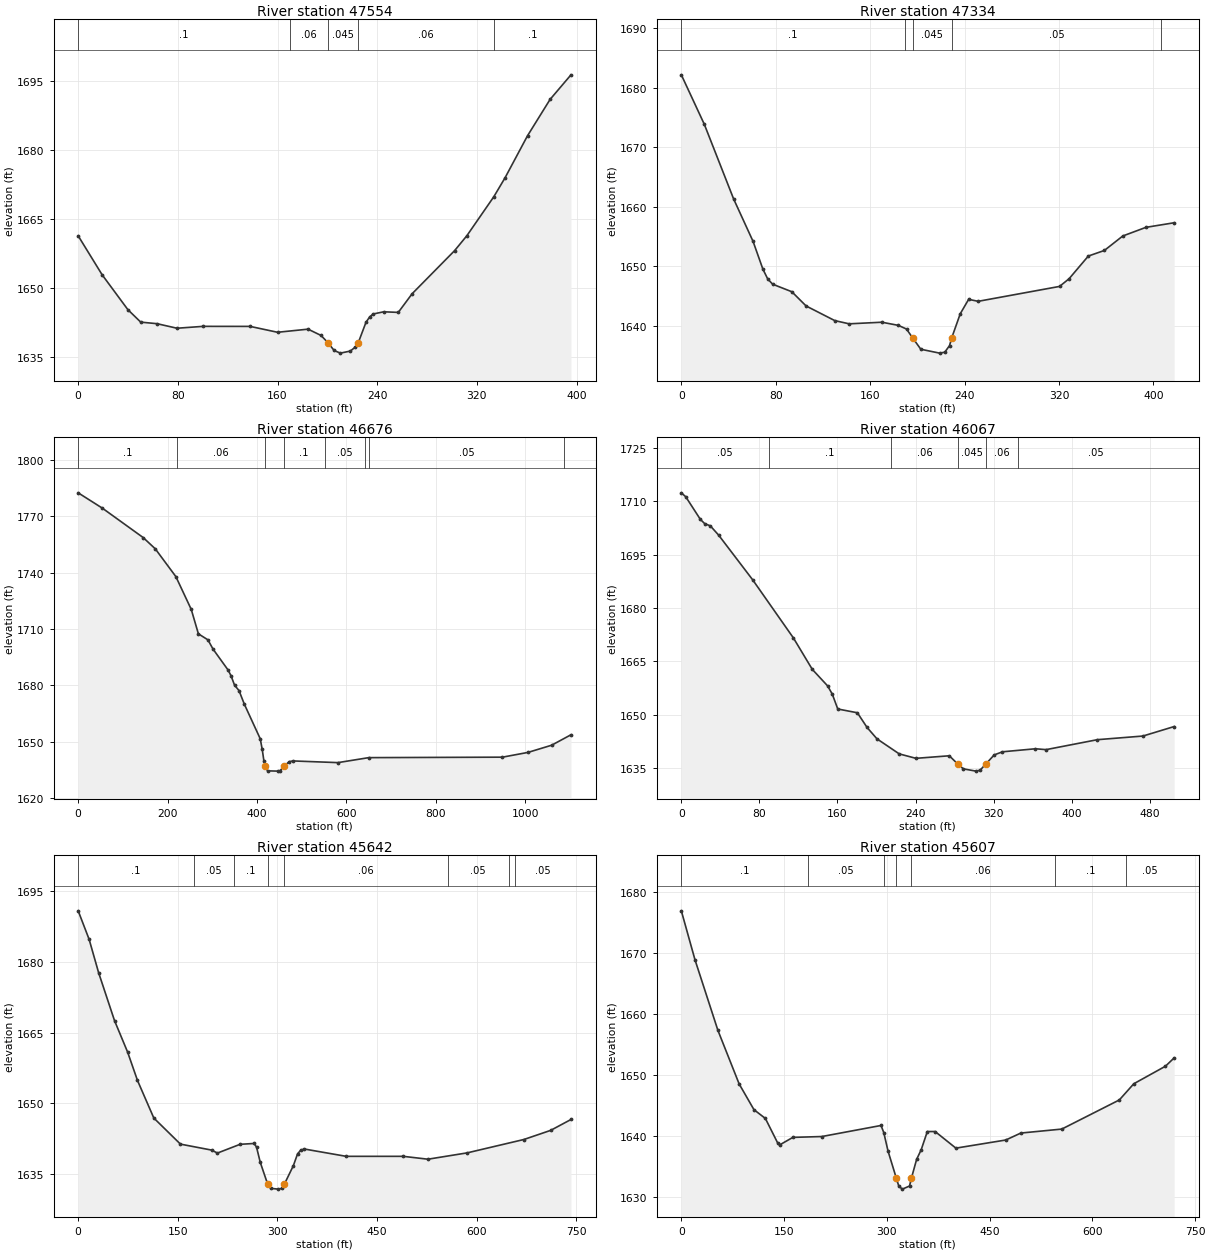
Type RM Length L Ch R = 1 ,47554   ,209.7,219.8,228.6
XS GIS Cut Line= 3
2205149.98000675 709906.301231452205335.64565606710133.468614133
2205382.60814383710224.117137031
#Sta/Elev= 30
       0 1661.29    19.2 1652.82    39.9 1645.21    50.2  1642.5    63.3 1642.16
    79.3 1641.17   100.3 1641.58     138 1641.57     160 1640.29   184.5 1640.97
   194.9  1639.6  200.581637.985   205.4 1636.33   210.4 1635.75   218.4  1636.2
   222.5 1637.09   224.7 1637.96     231 1642.48   233.9 1643.62   236.7 1644.27
   245.2 1644.75   256.9 1644.62     268 1648.68   302.1 1658.07   311.9  1661.3
   333.6 1669.82   342.6 1673.94   360.6 1683.08   378.7 1690.99   395.5 1696.35
#Mann= 5 ,-1,0
       0      .1       0     170     .06       0  200.58    .045       0
   224.7     .06       0  333.39      .1       0
Bank Sta=200.58,224.7
XS Rating Curve= 0 ,0
Exp/Cntr(USF)=0,0
Exp/Cntr=0.3,0.1

Type RM Length L Ch R = 1 ,47334   ,696.4,658.1,632.1
XS GIS Cut Line= 4
 2205034.5357987709918.3673081632205054.76081496709995.222369971
2205097.90751633710268.9342567582205147.79588978710303.990951617
#Sta/Elev= 30
       0 1682.16    19.5 1673.84    44.3 1661.32    60.8 1654.18    69.1 1649.53
    73.2 1647.88    77.4    1647    93.6 1645.74   105.7 1643.35     130 1640.89
   142.2 1640.35   169.9 1640.62   183.9 1640.09   190.8 1639.47  195.861638.016
   202.9 1636.08   218.8 1635.43   223.2 1635.59   227.2 1636.69   229.1 1638.01
   236.3 1642.04   243.4 1644.46   251.5 1644.13   320.4 1646.63   328.5 1647.92
   344.8 1651.73   358.4 1652.67     374  1655.1   393.6 1656.55   417.5 1657.32
#Mann= 5 ,-1,0
       0      .1       0  189.47     .05       0  195.86    .045       0
   229.1     .05       0  406.56     .06       0
Bank Sta=195.86,229.1
XS Rating Curve= 0 ,0
Exp/Cntr(USF)=0,0
Exp/Cntr=0.3,0.1

Type RM Length L Ch R = 1 ,46676   ,639.3,608.6,584.7
XS GIS Cut Line= 4
2204092.12860042710398.1047235882204417.87574633710163.958225028
2205017.01426161710249.7492747392205093.91941506710307.032831348
#Sta/Elev= 30
       0 1782.38    54.2 1774.21   145.5 1758.58   172.5 1752.61   218.5 1737.85
   252.9 1720.42   268.9 1707.43   290.2 1704.25   301.6 1699.34     335  1688.3
   341.8 1685.22   349.8 1680.14   359.7 1677.29   371.7 1670.02   407.2 1651.67
   411.6 1646.13   415.6 1639.61  418.23 1636.97   423.7 1634.61   447.9 1634.47
     452 1634.73   459.4 1636.99   472.2 1639.49   480.3 1639.89     581 1638.99
     650 1641.64     949 1641.89  1006.1 1644.42    1059 1648.24  1102.3  1653.8
#Mann= 8 ,-1,0
       0      .1       0     220     .06       0  418.23    .045       0
   459.4      .1       0  551.17     .05       0  641.17      .1       0
  651.17     .05       0 1086.42     .06       0
Bank Sta=418.23,459.4
XS Rating Curve= 0 ,0
Exp/Cntr(USF)=0,0
Exp/Cntr=0.3,0.1

Type RM Length L Ch R = 1 ,46067   ,442.9,425.3,396.8
XS GIS Cut Line= 3
2204721.30830663 710756.164294262204827.24694183710629.474792376
2205028.20270344710355.344921919
#Sta/Elev= 30
       0 1712.42     4.5 1711.32    19.5 1704.95      24 1703.74    29.7 1703.13
    38.2 1700.53    73.1 1687.95   114.9 1671.57   134.2 1662.75   149.9  1658.1
   154.7 1655.78   160.3  1651.6   180.4 1650.54   190.3 1646.42   200.5  1643.2
   223.3 1638.97   240.4 1637.72   274.6 1638.44   283.4 1636.09   289.1 1634.75
     302 1634.12   306.2 1634.39     312 1636.11   320.6 1638.68   329.1 1639.56
   362.9 1640.41   373.8 1640.17   426.4 1642.97     473 1643.99     505 1646.66
#Mann= 6 ,-1,0
       0     .05       0      90      .1       0  215.15     .06       0
   283.4    .045       0     312     .06       0  345.15     .05       0
Bank Sta=283.4,312
XS Rating Curve= 0 ,0
Exp/Cntr(USF)=0,0
Exp/Cntr=0.3,0.1

Type RM Length L Ch R = 1 ,45642   ,33.5,35.4,37.3
XS GIS Cut Line= 6
2205189.29743837711021.3872781772205279.94596127710896.882078053
2205249.36573668710820.4315165732205045.13352244710614.015000578
2205037.48846629710552.8545513942205091.00385932 710408.69063546
#Sta/Elev= 30
       0 1690.86    16.5  1684.8    30.8 1677.72    54.7 1667.57    74.5 1660.86
    89.3 1654.87   113.9 1646.89     154 1641.35   201.1 1640.08   209.7 1639.45
   243.8 1641.31     265 1641.49   268.6 1640.72   274.2  1637.5   285.3 1632.88
     290 1631.96   301.5  1631.8   307.5 1631.98   310.7  1632.9   324.1 1636.79
   330.4 1639.28   335.2 1640.08   340.7 1640.31   403.6 1638.76   489.5 1638.76
   526.8 1638.15   585.7 1639.49   671.2 1642.33   711.6 1644.27   742.2 1646.58
#Mann= 8 ,-1,0
       0      .1       0  174.01     .05       0  234.01      .1       0
   285.3    .045       0   310.7     .06       0  556.79     .05       0
  648.42      .1       0  658.42     .05       0
Bank Sta=285.3,310.7
XS Rating Curve= 0 ,0
Exp/Cntr(USF)=0,0
Exp/Cntr=0.3,0.1

Type RM Length L Ch R = 1 ,45607   ,498.7,528.2,558.5
XS GIS Cut Line= 6
2205225.33841735711030.1244852032205320.35554376710895.789927175
2205269.02445249710797.4963481292205089.91170845710582.342625108
2205081.17450142710539.7487408542205118.30763128710425.072898635
#Sta/Elev= 30
       0  1676.9    19.9  1668.9    53.4 1657.33    84.4 1648.56     106 1644.35
   122.7 1642.91   140.5 1638.93   143.4 1638.57   162.8 1639.81   205.1 1639.95
   291.5 1641.76   295.5 1640.61   301.8 1637.55  313.851633.134   317.5 1631.82
   322.7 1631.34   333.1 1631.85   335.9 1633.14   343.5 1636.22   350.1 1637.77
   359.1 1640.77   370.5 1640.77   400.8 1638.05   473.6 1639.38   495.6 1640.52
   555.4 1641.17   639.4 1645.94   660.5 1648.59   706.7 1651.46   719.4 1652.82
#Mann= 7 ,-1,0
       0      .1       0  184.54     .05       0  295.43     .06       0
  313.85    .045       0   335.9     .06       0  545.43      .1       0
  648.86     .05       0
Bank Sta=313.85,335.9
XS Rating Curve= 0 ,0
Exp/Cntr(USF)=0,0
Exp/Cntr=0.3,0.1

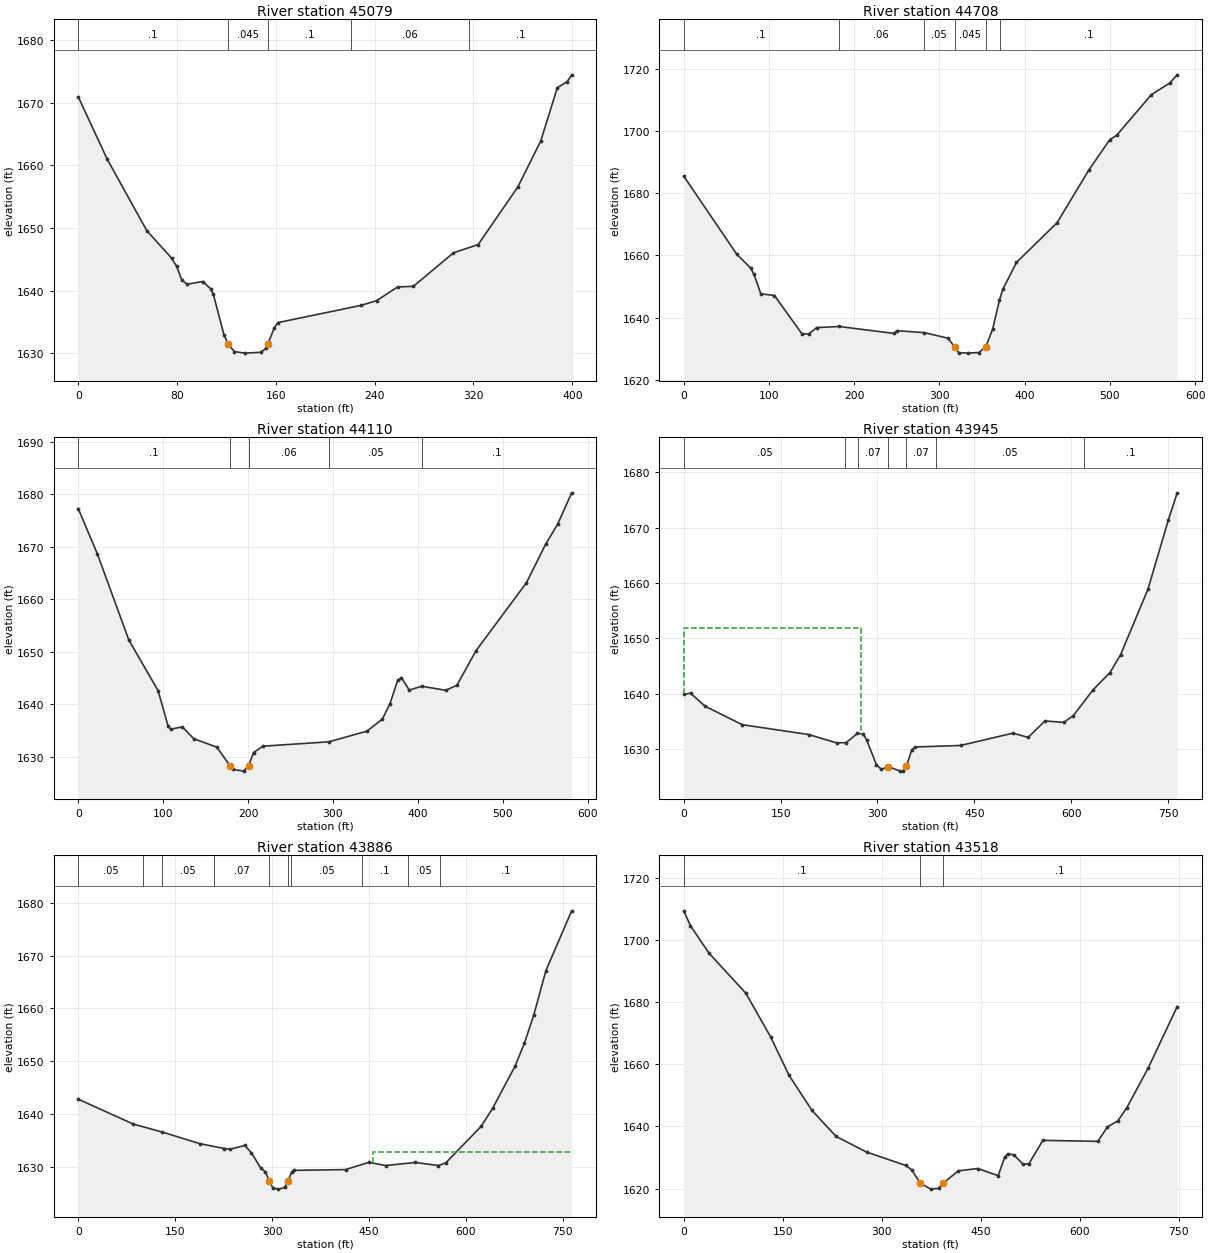
Type RM Length L Ch R = 1 ,45079   ,365.7,371.1,380.6
XS GIS Cut Line= 4
2205244.74982521711068.8959553592205325.64989027711062.154283271
2205509.02337108710994.7375623872205631.72180309711002.827568893
#Sta/Elev= 30
       0 1670.96    23.5 1660.98    55.6 1649.55    75.7 1645.17    79.7 1643.85
    83.9 1641.68    88.1 1641.02   100.9 1641.45   107.2  1640.3   109.4 1639.41
     118 1632.94   121.3 1631.48   126.5 1630.25     135 1630.01   147.8 1630.14
   152.1 1630.78   153.6  1631.5   158.7 1634.04   161.8 1634.89   228.8 1637.63
   241.6 1638.39   258.6 1640.58   271.4 1640.68   303.8 1646.03   323.8 1647.35
   355.9 1656.54   374.5  1663.9   387.9  1672.4     396 1673.39   399.5 1674.46
#Mann= 5 ,-1,0
       0      .1       0   121.3    .045       0   153.6      .1       0
  221.18     .06       0  316.55      .1       0
Bank Sta=121.3,153.6
XS Rating Curve= 0 ,0
Exp/Cntr(USF)=0,0
Exp/Cntr=0.3,0.1

Type RM Length L Ch R = 1 ,44708   ,604.2,597.8,588
XS GIS Cut Line= 4
2205177.84446298711379.5370842962205249.42270984711381.201694688
2205605.64933377711374.5432531192205753.79965868 711344.58026606
#Sta/Elev= 30
       0 1685.48    62.3 1660.32    78.4 1655.94    82.4 1653.94    90.4 1647.63
   106.4 1647.08   138.4 1634.85   146.4 1634.64   155.9 1636.75   182.4 1637.11
   246.4 1634.89   250.4 1635.76   282.4 1635.13   310.4 1633.32   317.8 1630.44
   322.4 1628.71   333.5 1628.54   346.4 1628.74   354.4 1630.58   362.4 1636.19
   370.4 1645.55   374.4 1649.07   390.4 1657.71     438 1670.48   475.1 1687.34
   499.8 1697.18     508 1698.64   548.8 1711.72   570.4 1715.46     579 1718.08
#Mann= 6 ,-1,0
       0      .1       0   181.6     .06       0   281.6     .05       0
   317.8    .045       0   354.4     .05       0   371.6      .1       0
Bank Sta=317.8,354.4
XS Rating Curve= 0 ,0
Exp/Cntr(USF)=0,0
Exp/Cntr=0.3,0.1

Type RM Length L Ch R = 1 ,44110   ,167,164.6,163
XS GIS Cut Line= 4
2205382.43220951  711908.94585612205445.31749099711925.591960021
2205776.39000233711749.8830852912205878.11619296711651.856028862
#Sta/Elev= 30
       0 1677.29    22.5 1668.69    59.7 1652.24    94.1 1642.63   105.9 1635.86
     109  1635.3   122.6 1635.74   136.2 1633.47   163.4 1631.88  178.511628.388
   182.8 1627.64   194.7 1627.32   200.6 1628.33   206.5 1630.86   217.7 1632.07
   295.3  1632.9     340 1634.93   358.1  1637.2   367.2 1640.16   376.2 1644.59
   380.7 1645.12   389.8 1642.75   404.7 1643.47   432.8  1642.7   445.9 1643.64
   468.5 1650.24   527.9 1663.18   550.5 1670.51   564.7 1674.33   581.1 1680.28
#Mann= 5 ,-1,0
       0      .1       0  178.51    .045       0   200.6     .06       0
  295.05     .05       0  405.05      .1       0
Bank Sta=178.51,200.6
XS Rating Curve= 0 ,0
Exp/Cntr(USF)=0,0
Exp/Cntr=0.3,0.1

Type RM Length L Ch R = 1 ,43945   ,58,59.1,59.1
XS GIS Cut Line= 3
2205319.26339289712198.7259249662205847.86441798711869.988510603
2205940.69724263711762.957724531
#Sta/Elev= 30
       0 1639.84    10.5 1640.06    33.2  1637.7    90.6 1634.37   193.5 1632.59
   236.6 1631.08   251.6 1631.13     269 1632.79   277.7 1632.69   283.2 1631.64
   298.3 1627.15   305.9  1626.3   316.7 1626.78   335.5 1625.97   340.2    1626
   344.9 1626.84   353.2 1629.86   358.9 1630.34   428.7 1630.61   509.8 1632.84
   533.4 1632.07   559.4 1635.05   588.4 1634.78     603 1635.97   634.1  1640.7
   660.1 1643.79   676.5 1647.02   718.9 1658.86   750.6 1671.44   764.2 1676.31
#Mann= 7 ,-1,0
       0     .05       0     250      .1       0     270     .07       0
   316.7    .045       0   344.9     .07       0     390     .05       0
     620      .1       0
#XS Ineff= 2 , 0
          274.34 1651.78
Permanent Ineff=
       F       F
Bank Sta=316.7,344.9
XS Rating Curve= 0 ,0
Exp/Cntr(USF)=0,0
Exp/Cntr=0.3,0.1

Type RM Length L Ch R = 1 ,43886   ,379.1,368.1,360.3
XS GIS Cut Line= 3
2205371.68663504712231.4904513152205893.73475486711910.398093099
2205975.64607073711783.708591219
#Sta/Elev= 30
       0 1642.81    85.1  1638.1     130 1636.58   188.4 1634.37     226 1633.46
   235.4 1633.34   257.9 1634.03   268.2 1632.64   282.3 1629.79   289.9 1629.04
   295.7 1627.26   301.5 1625.98   309.8 1625.76   319.9 1626.07   324.6 1627.31
   330.6    1629   333.5 1629.32   413.8 1629.46   449.8 1630.83     476 1630.23
   521.8 1630.82   557.4 1630.23   568.8 1630.72   623.9 1637.69   641.6 1641.11
   676.3 1649.09   690.6 1653.41   705.2 1658.76   723.9 1667.15   763.8 1678.51
#Mann= 10 ,-1,0
       0     .05       0     100      .1       0     130     .05       0
     210     .07       0   295.7    .045       0   324.6     .07       0
     330     .05       0     440      .1       0     510     .05       0
     560      .1       0
#XS Ineff= 2 , 0
                          456.14         1632.88
Permanent Ineff=
       F       F
Bank Sta=295.7,324.6
XS Rating Curve= 0 ,0
Exp/Cntr(USF)=0,0
Exp/Cntr=0.3,0.1

Type RM Length L Ch R = 1 ,43518   ,891.1,883.4,861.5
XS GIS Cut Line= 4
2205724.39015539712491.7039818312205929.65406965 712294.64831428
2206030.69528636 712107.38708656  2206174.928079711902.838722799
#Sta/Elev= 30
       0  1709.4    10.1 1704.63    38.3 1695.76      94  1682.9   131.8 1668.74
   159.6 1656.41   194.2 1645.18   230.8 1636.79   276.9 1631.76   336.2 1627.45
   345.3 1626.04   358.3 1621.77   374.1 1619.82   386.2 1620.08   392.91621.723
   416.2 1625.71   445.3 1626.45   476.4 1624.15   486.2 1630.08   490.7 1631.19
     500 1630.87   514.3  1627.8   522.9 1627.99   544.1 1635.52   627.3  1635.2
     642 1639.83   657.8 1641.83   671.3 1646.02   703.8 1658.86   747.6 1678.57
#Mann= 3 ,-1,0
       0      .1       0   358.3    .045       0   392.9      .1       0
Bank Sta=358.3,392.9
XS Rating Curve= 0 ,0
Exp/Cntr(USF)=0,0
Exp/Cntr=0.3,0.1