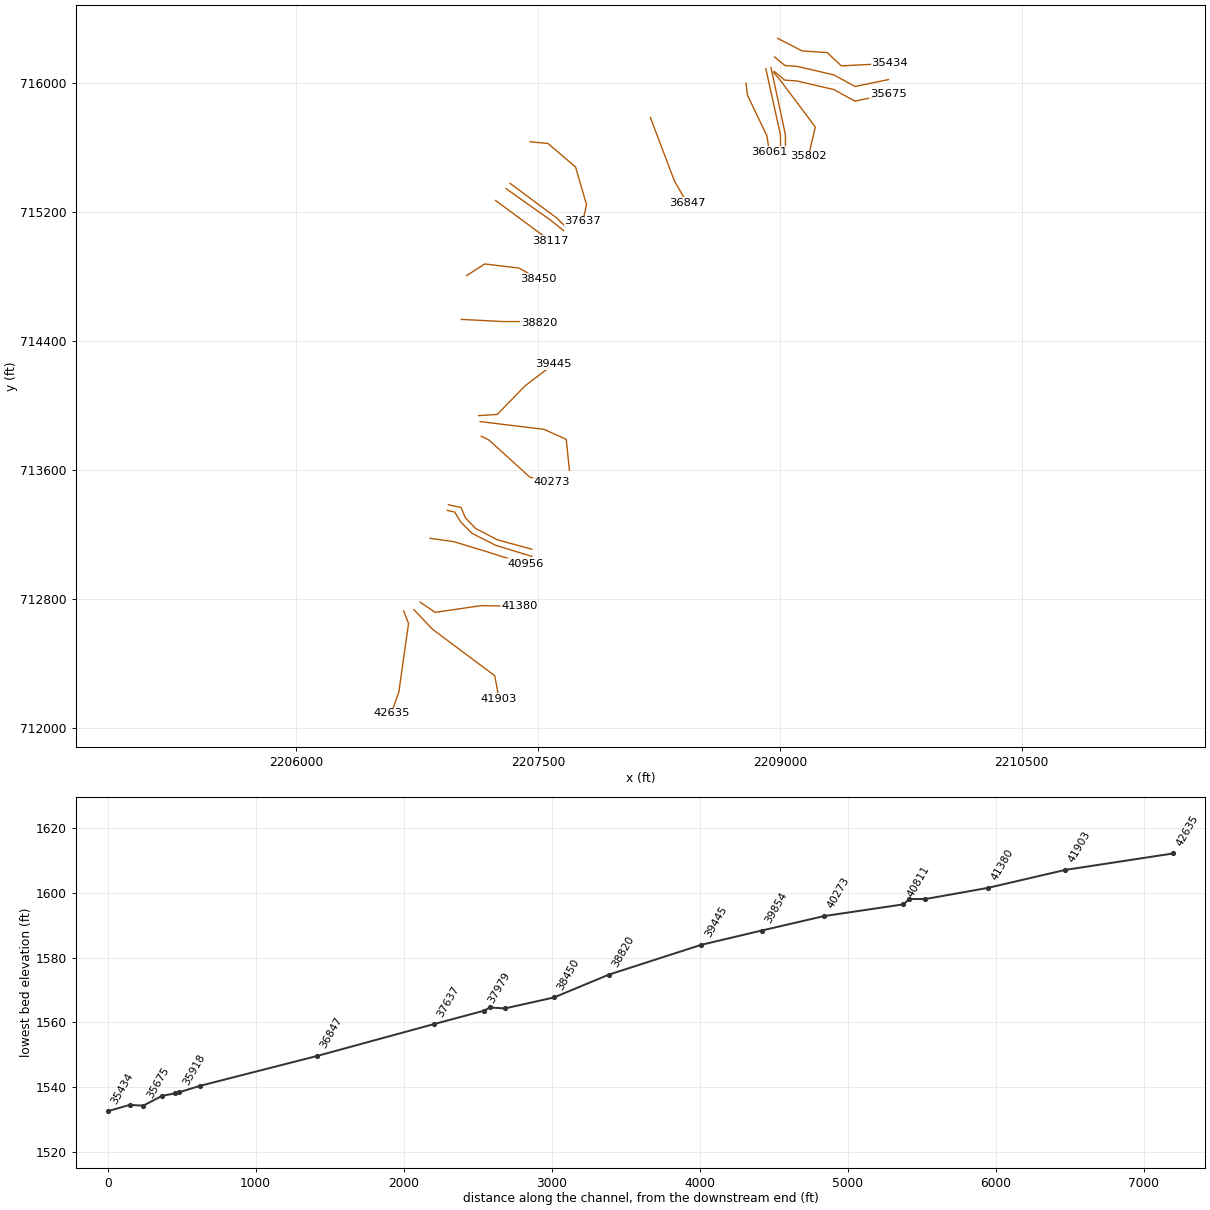
HEC-RAS study SANDRN1.prj: SANDRN1

--- SANDRN1.g01 (geometry) --- (continued)

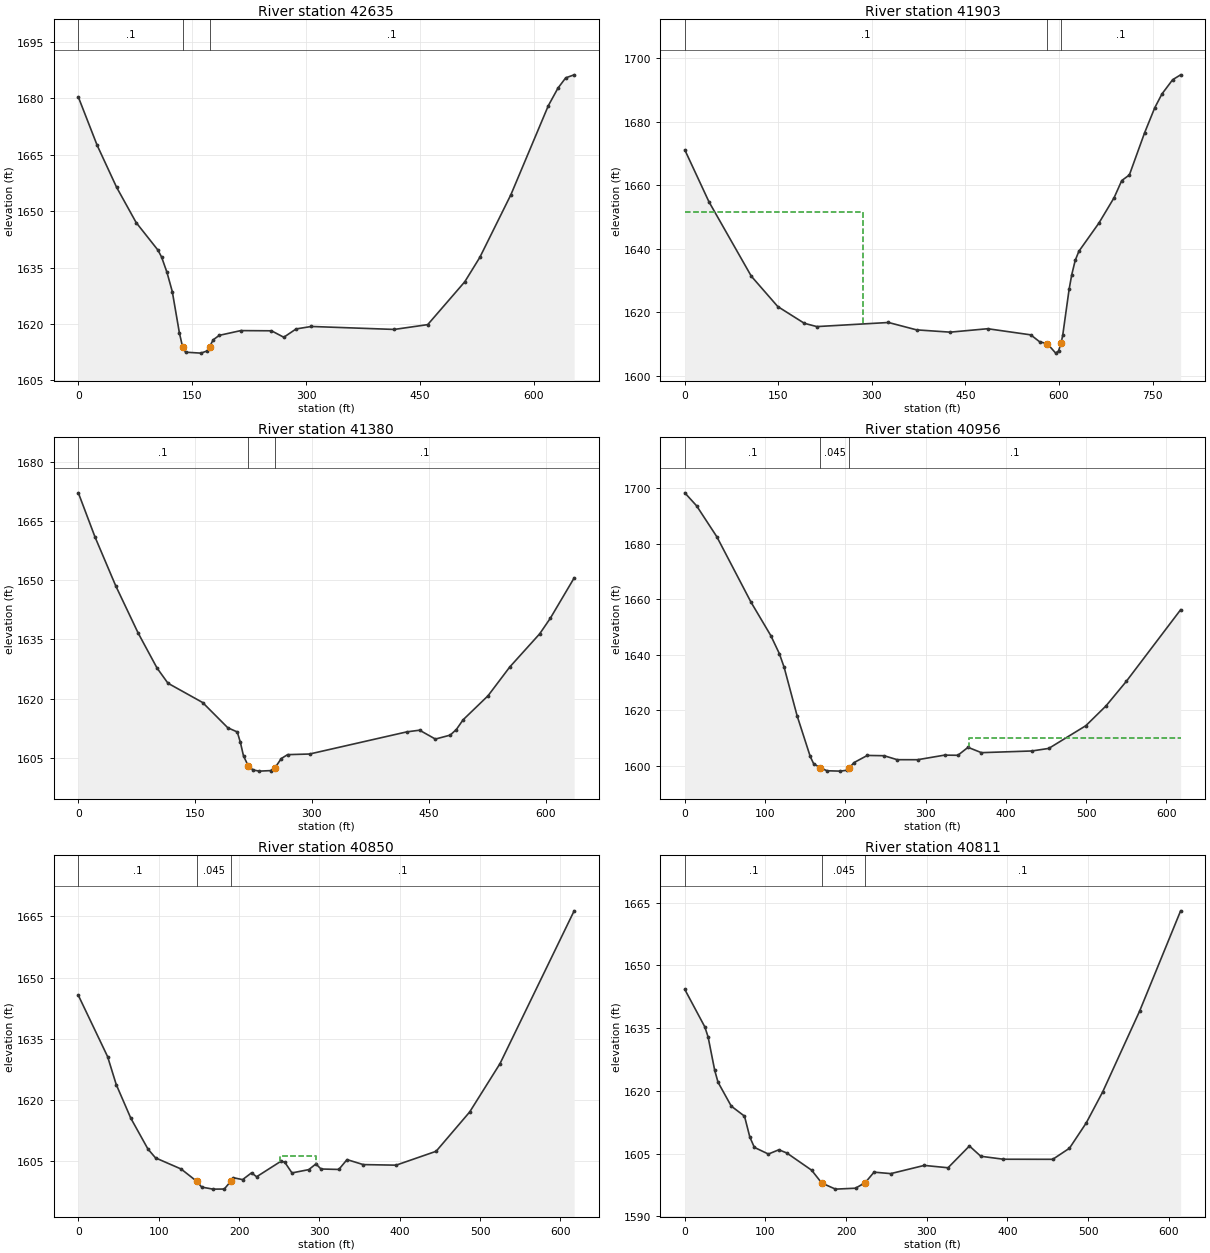
Type RM Length L Ch R = 1 ,42635   ,708.8,731.6,737.9
XS GIS Cut Line= 4
2206666.56619933712724.2480336672206696.52918639712646.344267312
2206636.60321227712222.3680004232206590.16058233712089.032708009
#Sta/Elev= 30
       0 1680.37    24.7 1667.57    50.4 1656.36    76.1 1646.99   104.8 1639.66
   109.6 1637.82   116.7 1633.74   123.7 1628.63   133.1 1617.59   137.2 1613.97
   141.2 1612.51   161.4 1612.26   169.5 1612.84   172.81613.987   177.6 1615.81
   185.6 1616.99   213.9 1618.25   254.3  1618.2   270.5 1616.48   286.7 1618.69
   306.8 1619.35   415.9 1618.56     460 1619.84   508.8 1631.24   528.6 1637.73
   569.5 1654.39   618.8 1678.07   631.5 1682.75   641.7 1685.47   652.8 1686.27
#Mann= 3 ,-1,0
       0      .1       0   137.2    .045       0   172.8      .1       0
Bank Sta=137.2,172.8
XS Rating Curve= 0 ,0
Exp/Cntr(USF)=0,0
Exp/Cntr=0.3,0.1

Type RM Length L Ch R = 1 ,41903   ,504.9,522.7,523.9
XS GIS Cut Line= 4
2206729.48847215712733.2369297852206846.34412169712610.388682841
 2207231.3685054712322.7440070712207258.33519375 712180.41981854
#Sta/Elev= 30
       0 1671.11    38.7 1654.78   106.6 1631.37   149.1  1621.8   191.7 1616.53
   211.7  1615.5   326.6 1616.79   371.6 1614.47   425.5 1613.75   485.7 1614.83
   554.7  1612.9     569 1610.71   581.3 1610.11   594.7 1607.15   599.3 1607.86
   603.3 1610.26     606 1612.82   616.2 1627.22   620.4  1631.8     626 1636.35
   631.8 1639.18     664 1648.08   688.4 1656.08   700.6 1661.45   712.8 1663.21
   737.2 1676.46   753.5 1684.35   765.1 1688.71   782.2 1693.18     795 1694.72
#Mann= 3 ,-1,0
       0      .1       0   581.3    .045       0   603.3      .1       0
#XS Ineff= 2 , 0
          285.26 1651.63
Permanent Ineff=
       F       F
Bank Sta=581.3,603.3
XS Rating Curve= 0 ,0
Exp/Cntr(USF)=0,0
Exp/Cntr=0.3,0.1

Type RM Length L Ch R = 1 ,41380   ,433.3,424.4,413.3
XS GIS Cut Line= 4
2206768.51939822712779.2941242712206861.73758018712716.038929367
2207146.38595724712757.6541891722207382.76063293712754.324968388
#Sta/Elev= 30
       0 1672.16    21.4 1660.97    47.9 1648.63    76.9 1636.57   101.1 1627.72
   115.1 1623.88   159.6 1618.99   191.9 1612.59   204.1 1611.52   208.1 1608.88
   212.1 1605.44     2181603.016   224.3 1601.89   232.4 1601.59   246.8 1601.72
   252.71602.491   260.6 1604.78   268.7 1605.77     297 1605.93   421.9 1611.55
   438.2 1611.97   458.5 1609.72   477.5 1610.72   485.4 1612.14   494.1 1614.61
   526.1  1620.7   554.1 1628.02   592.4  1636.4   606.1 1640.36   636.7 1650.58
#Mann= 3 ,-1,0
       0      .1       0     218    .045       0   252.7      .1       0
Bank Sta=218,252.7
XS Rating Curve= 0 ,0
Exp/Cntr(USF)=0,0
Exp/Cntr=0.3,0.1

Type RM Length L Ch R = 1 ,40956   ,119.5,105.7,94.8
XS GIS Cut Line= 4
2206829.61516877713175.6331061662206976.46405826713155.022415044
2207171.48266368713095.6897648012207424.83739745713015.809442681
#Sta/Elev= 30
       0 1698.35    14.7 1693.68    39.9 1682.54    82.4 1659.02   107.2 1646.92
   117.8 1640.45   123.8  1635.5   139.9  1618.1   156.3  1603.4   160.5 1600.83
   168.9 1599.28   177.3 1598.26     194 1598.13   202.3 1598.47   205.2 1599.36
   210.7 1601.18   227.4 1603.78   248.3 1603.68   264.6 1602.25   290.1 1602.24
   323.6 1603.89   340.3 1603.84   352.9  1606.7   369.6 1604.78   432.5 1605.39
   453.5 1606.31   499.7 1614.49   524.8 1621.61     550 1630.41   617.8 1656.25
#Mann= 3 ,-1,0
       0      .1       0   168.9    .045       0   205.2      .1       0
#XS Ineff= 2 , 0
                          354.44         1610.02
Permanent Ineff=
       F       F
Bank Sta=168.9,205.2
XS Rating Curve= 0 ,0
Exp/Cntr(USF)=0,0
Exp/Cntr=0.3,0.1

Type RM Length L Ch R = 1 ,40850   ,38.9,39.3,38
XS GIS Cut Line= 6
2206936.56621406713348.7308273782206982.76419621713338.901469473
2207021.09869204713275.9935788842207090.88713316713206.205137762
2207236.36163015713132.4849534782207460.47099037713063.679448146
#Sta/Elev= 30
       0 1645.65    36.4 1630.65    47.2 1623.78    65.3 1615.56    86.7 1607.98
    96.1 1605.83   127.9 1603.11   147.5 1600.08   153.5 1598.68   167.5 1598.18
   181.6  1598.2   190.1 1600.18   193.1 1600.97   204.4 1600.51   215.6 1602.17
   221.9 1601.21   252.4 1605.04   256.9 1604.78   265.9 1602.15   286.8 1602.96
   295.7 1604.35     302 1603.11   324.2    1603   334.4 1605.41   354.6 1604.19
   395.5 1604.05   445.3 1607.45   487.1 1617.09   524.8 1628.92   617.1 1666.35
#Mann= 3 ,-1,0
       0      .1       0   147.5    .045       0   190.1      .1       0
#XS Ineff= 1 ,-1
  250.82  295.99 1606.31
Permanent Ineff=
       F
Bank Sta=147.5,190.1
XS Rating Curve= 0 ,0
Exp/Cntr(USF)=0,0
Exp/Cntr=0.3,0.1

Type RM Length L Ch R = 1 ,40811   ,528.6,537.7,536.5
XS GIS Cut Line= 6
2206943.96955457713384.0865773842207022.60441781713366.393733156
2207049.14368415713302.5029067762207113.03451053713236.646208815
2207246.71377803713166.8577676932207460.99378035713107.881620265
#Sta/Elev= 30
       0 1644.27    24.8 1635.32    28.9 1632.89    37.1  1624.9    41.2 1622.07
    57.6 1616.36      74 1613.96    80.6 1608.97    86.2  1606.5   103.6  1604.9
   116.6 1605.92   126.4 1605.16   157.2 1601.04   169.8 1597.96   186.8 1596.51
   211.6 1596.73   223.6 1598.06   234.6 1600.57   255.3 1600.22   296.8 1602.18
   326.3 1601.62   352.8 1606.83   366.9 1604.37   394.9 1603.66   456.1 1603.64
   476.8 1606.29   497.6 1612.34     518 1619.77   563.8  1639.1   614.6 1663.07
#Mann= 3 ,-1,0
       0      .1       0   169.8    .045       0   223.6      .1       0
Bank Sta=169.8,223.6
XS Rating Curve= 0 ,0
Exp/Cntr(USF)=0,0
Exp/Cntr=0.3,0.1

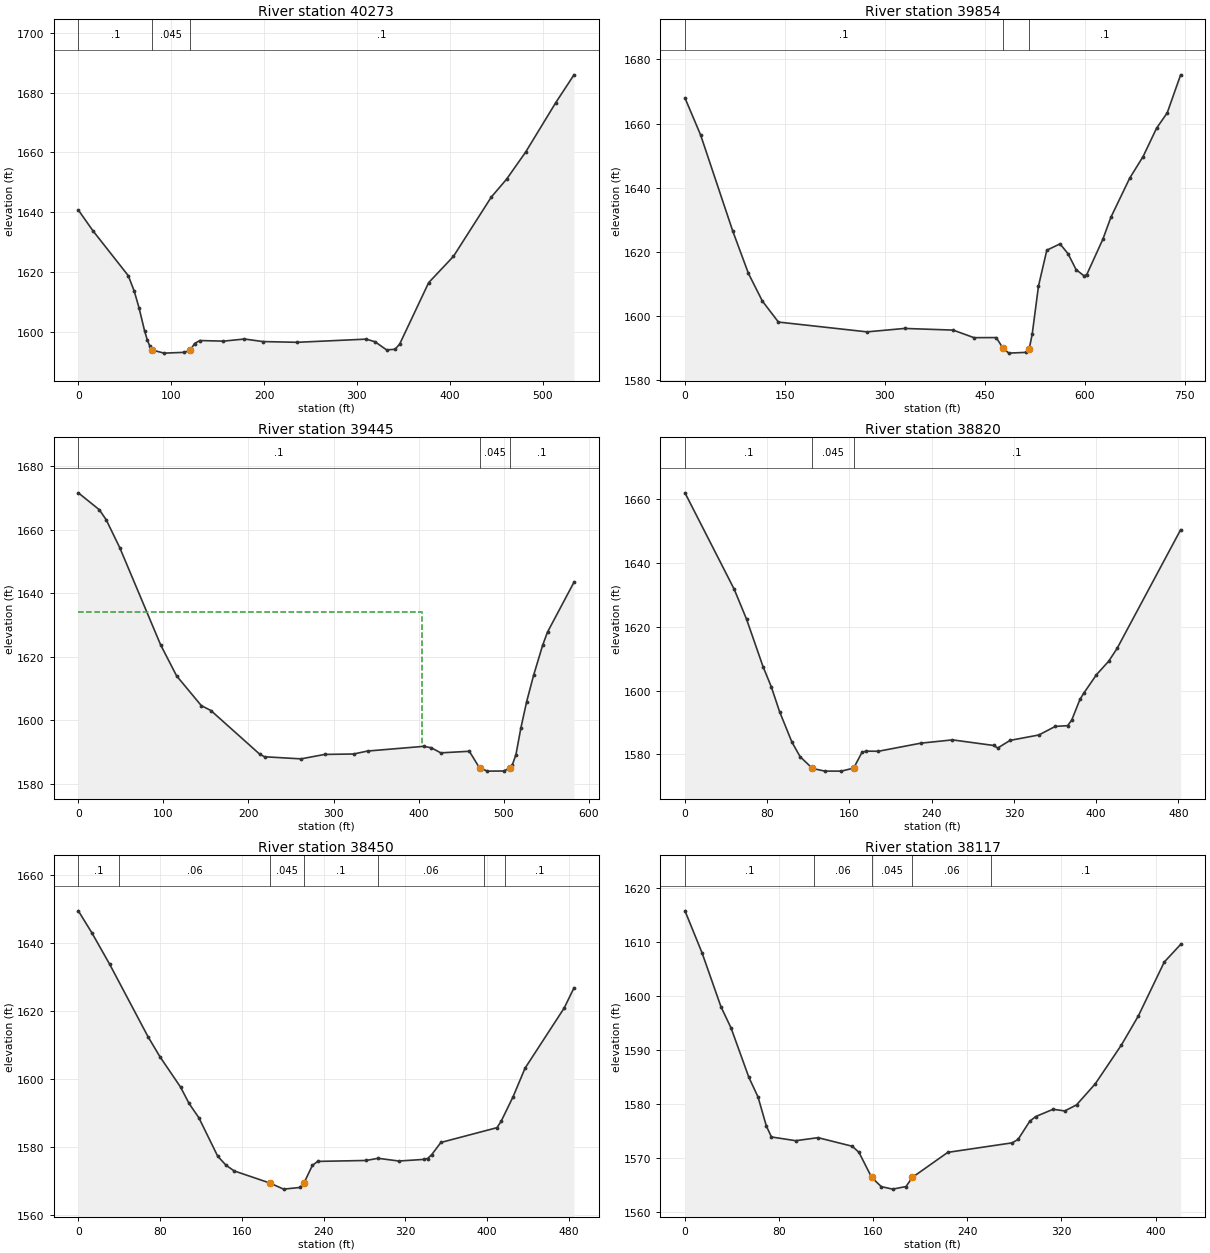
Type RM Length L Ch R = 1 ,40273   ,413.6,419.2,427.1
XS GIS Cut Line= 4
2207147.56768777713809.6572618652207196.71447729713784.537791663
2207450.09348106 713554.093956342207583.33588821713526.790184382
#Sta/Elev= 30
       0 1640.76    15.7 1633.82    53.8 1618.78    60.2 1613.61    65.3 1608.11
    71.3 1600.38    74.2 1597.36      77 1595.15    79.8 1593.89    92.3 1592.87
   113.9 1593.13  120.71 1593.91   125.1 1596.08   130.8 1597.08   156.3 1596.88
   178.8 1597.59   198.8 1596.74   235.6 1596.49   309.9 1597.55   319.4 1596.69
   331.9 1593.96     341 1594.15     346  1595.9   377.2 1616.44   403.9 1625.24
   444.7  1645.1   461.1 1651.06   481.6 1660.11   514.1 1676.69   533.7 1685.98
#Mann= 3 ,-1,0
       0      .1       0    79.8    .045       0  120.71      .1       0
Bank Sta=79.8,120.71
XS Rating Curve= 0 ,0
Exp/Cntr(USF)=0,0
Exp/Cntr=0.3,0.1

Type RM Length L Ch R = 1 ,39854   ,385.3,409.5,435.9
XS GIS Cut Line= 4
2207140.95821666713899.9360898752207536.65101694713852.134275076
2207674.74514858713789.7263501992207694.66257141713597.191262814
#Sta/Elev= 30
       0 1667.98    23.4 1656.49    71.7 1626.49    95.2 1613.29   116.1 1604.67
   140.2 1598.11   273.2 1595.05   329.6 1596.12   402.4  1595.6   433.7 1593.24
     467 1593.27   477.1 1589.99   485.8 1588.42   512.2 1588.66   516.6 1589.86
     521 1594.32   530.4 1609.31   542.9 1620.51   562.7 1622.49   574.8 1619.41
   586.9 1614.44   598.9  1612.5   602.9 1612.93   627.1 1623.99   639.1  1630.8
   667.3 1642.99   687.4 1649.73   707.5 1658.52   723.6 1663.36   743.7  1675.2
#Mann= 3 ,-1,0
       0      .1       0   477.1    .045       0   516.6      .1       0
Bank Sta=477.1,516.6
XS Rating Curve= 0 ,0
Exp/Cntr(USF)=0,0
Exp/Cntr=0.3,0.1

Type RM Length L Ch R = 1 ,39445   ,642.7,625,606.9
XS GIS Cut Line= 4
2207131.52528723713937.0265137782207246.80787994713944.307519634
2207419.12501852714121.4786621162207593.86915905714254.963769465
#Sta/Elev= 30
       0 1671.58    24.7 1666.25    32.7 1663.13    48.7 1654.32    96.8  1623.7
   115.5 1613.98   144.6  1604.6   155.8 1603.07   213.3  1589.3   218.9 1588.51
   261.8 1587.85   289.6 1589.25   323.6 1589.38   339.9 1590.31     406 1591.79
   414.9 1591.34     426 1589.74   459.6 1590.24   471.6 1584.99   480.8 1583.99
   499.9 1584.03   507.1 1584.93     510 1585.85   514.4 1589.22   520.1 1597.48
   526.9 1605.79   535.1 1614.13   545.8 1623.65   551.5 1627.77   582.6 1643.45
#Mann= 3 ,-1,0
       0      .1       0   471.6    .045       0   507.1      .1       0
#XS Ineff= 2 , 0
          404.17 1633.99
Permanent Ineff=
       F       F
Bank Sta=471.6,507.1
XS Rating Curve= 0 ,0
Exp/Cntr(USF)=0,0
Exp/Cntr=0.3,0.1

Type RM Length L Ch R = 1 ,38820   ,367.7,369.3,364.8
XS GIS Cut Line= 4
2207024.32948721 714534.462915422207281.86136098714520.979571243
2207431.52648134714520.9795712432207505.68487432714512.889564737
#Sta/Elev= 30
       0 1662.05    47.9  1631.8    59.9 1622.42    75.9 1607.57      84 1601.18
      92 1593.44     104 1583.88     112 1579.29     124  1575.6     136 1574.77
   152.1 1574.76   164.1 1575.72   172.1 1580.62   176.1 1581.03   188.1 1580.99
   229.4 1583.53   260.2 1584.56   300.2 1582.81   304.2 1582.01   316.2  1584.4
   344.2  1586.1   360.2 1588.79   372.2 1589.02   376.2 1590.79   384.2 1597.28
     388 1599.26   400.2 1604.99   412.2 1609.27   420.3 1613.25   482.1 1650.47
#Mann= 3 ,-1,0
       0      .1       0     124    .045       0   164.1      .1       0
Bank Sta=124,164.1
XS Rating Curve= 0 ,0
Exp/Cntr(USF)=0,0
Exp/Cntr=0.3,0.1

Type RM Length L Ch R = 1 ,38450   ,343.6,332.9,321
XS GIS Cut Line= 4
 2207056.9602433714806.118944336 2207169.1853861714878.289682357
2207381.53987926714853.0185665672207502.01266965714785.960662275
#Sta/Elev= 30
       0 1649.42    13.3 1642.94    30.6 1633.78    68.2 1612.48    79.9 1606.59
   100.1 1597.67   108.4 1592.87     118 1588.67   136.4 1577.41   144.5 1574.76
   152.6 1573.06   187.5 1569.51   200.9 1567.72     217 1568.21     221 1569.59
   229.1 1574.68   234.3 1575.86   281.5 1576.13   293.5 1576.77   313.7 1575.97
   337.9 1576.44   341.9 1576.71   345.9 1577.84   354.9 1581.42   409.8 1585.76
   413.8 1587.59   425.6 1594.86   437.3 1603.23   475.6 1620.89   485.2 1626.81
#Mann= 7 ,-1,0
       0      .1       0      40     .06       0   187.5    .045       0
     221      .1       0  293.43     .06       0  397.28     .07       0
  417.28      .1       0
Bank Sta=187.5,221
XS Rating Curve= 0 ,0
Exp/Cntr(USF)=0,0
Exp/Cntr=0.3,0.1

Type RM Length L Ch R = 1 ,38117   ,100.7,101.1,101.7
XS GIS Cut Line= 2
2207236.52679543715272.3776802822207575.34476241715022.023934447
#Sta/Elev= 30
       0 1615.86    14.5 1608.09    30.6  1598.1    39.2 1594.15    54.3 1585.03
    62.1 1581.39    69.2 1575.99    73.5 1573.98    94.1 1573.29   113.1 1573.85
   142.2 1572.26   147.9 1571.13   158.7 1566.48   166.9 1564.78   176.5 1564.32
   187.9  1564.8  193.251566.495   223.4 1571.13   278.1 1572.89   283.1 1573.52
     293 1576.87     298 1577.75   312.9 1579.11   322.8  1578.8   332.8 1579.92
   348.7 1583.81     371 1591.03   385.3 1596.37   407.4 1606.38   421.3 1609.64
#Mann= 5 ,-1,0
       0      .1       0     110     .06       0   158.7    .045       0
  193.25     .06       0     260      .1       0
Bank Sta=158.7,193.25
XS Rating Curve= 0 ,0
Exp/Cntr(USF)=0,0
Exp/Cntr=0.3,0.1

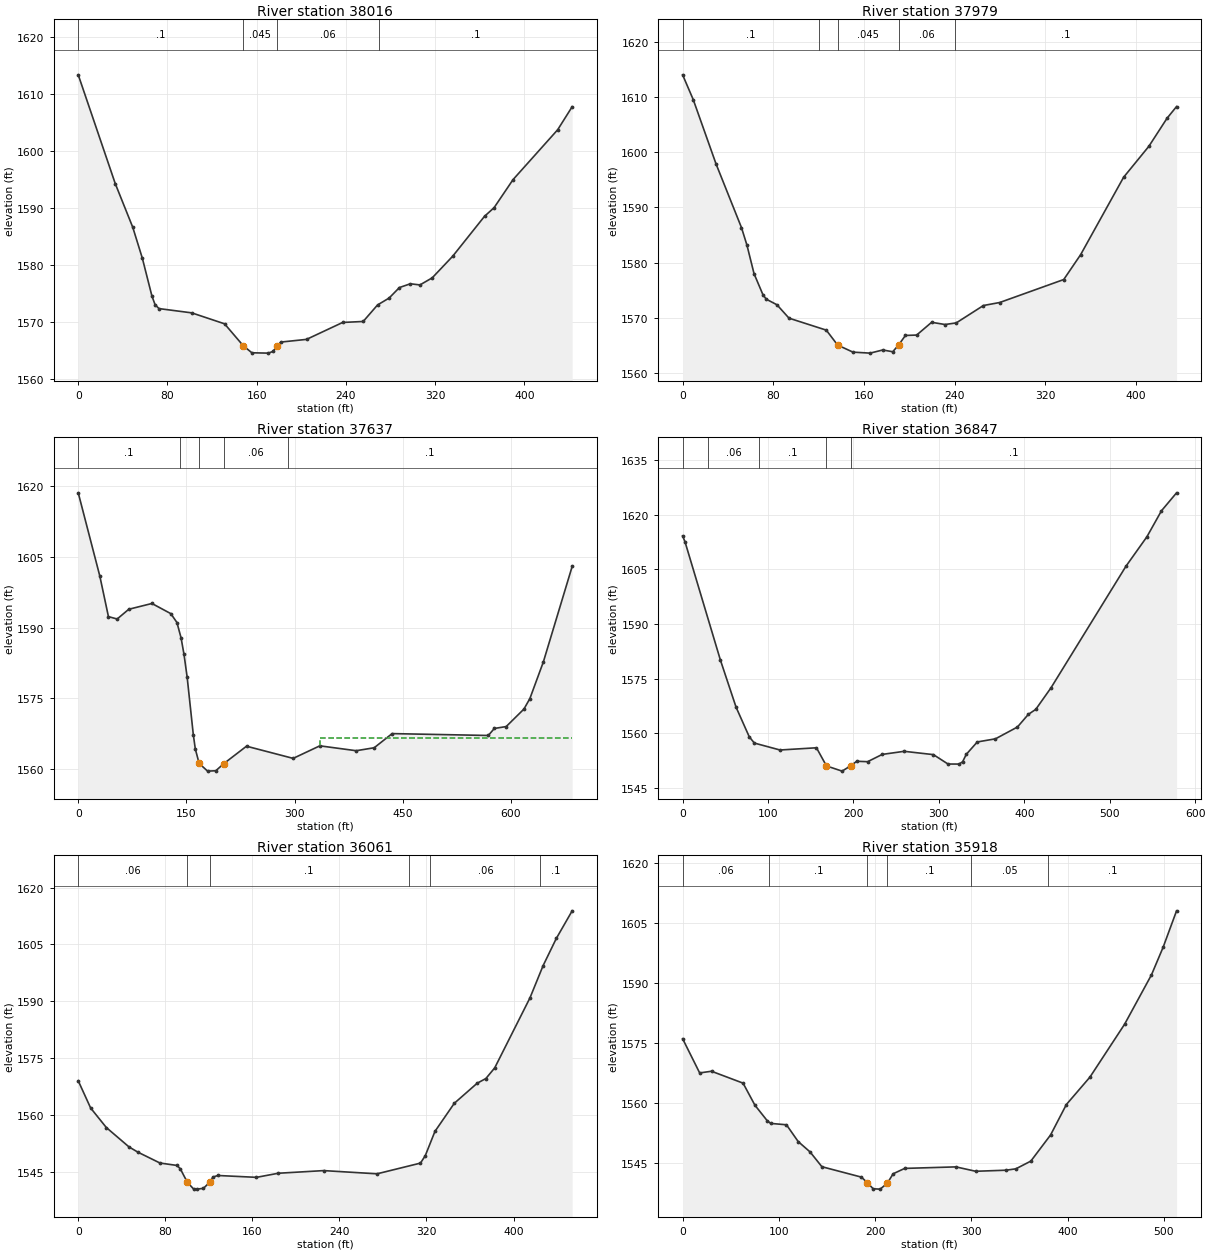
Type RM Length L Ch R = 1 ,38016   ,39.5,37.6,39.4
XS GIS Cut Line= 3
2207301.05581087715346.1620662592207578.92192947715149.506102661
 2207658.5397285715085.015685448
#Sta/Elev= 30
       0 1613.41    33.2 1594.33    48.9 1586.67    57.5 1581.24    66.1  1574.6
    68.9 1573.11    72.4 1572.42   101.8 1571.67   131.2 1569.75  148.021565.895
   155.7 1564.67   170.4 1564.61   174.8 1564.92     178 1565.84   181.7 1566.55
   204.7 1567.02   237.1 1569.99   255.5 1570.16   268.4 1573.06   278.7 1574.26
     288 1576.11   297.8 1576.77   306.4 1576.57   317.4 1577.81   335.8 1581.61
   364.3  1588.6   372.9 1590.12   389.9 1595.04   429.9 1603.78   442.9 1607.82
#Mann= 4 ,-1,0
       0      .1       0  148.02    .045       0     178     .06       0
     270      .1       0
Bank Sta=148.02,178
XS Rating Curve= 0 ,0
Exp/Cntr(USF)=0,0
Exp/Cntr=0.3,0.1

Type RM Length L Ch R = 1 ,37979   ,340.2,341.5,341.2
XS GIS Cut Line= 3
2207326.53350656 715378.805363862207615.54611703715163.837306486
2207669.68622036715111.289559127
#Sta/Elev= 30
       0 1614.01     9.4  1609.5    29.5 1597.87    51.9 1586.36    56.7  1583.2
      63 1578.01    70.9 1574.18    73.8  1573.4    83.2 1572.39    93.8 1569.97
   126.7  1567.8   136.7  1565.1   150.2 1563.82   165.3 1563.64   176.5 1564.21
   185.3 1563.89   190.4  1565.1   196.5 1566.84   206.4 1566.91   219.6 1569.22
   231.4 1568.82   241.3 1569.11   265.3 1572.26   279.6  1572.8   336.1 1576.96
     351 1581.46   388.9 1595.47   411.2 1601.08   427.2 1606.15   435.6 1608.27
#Mann= 5 ,-1,0
       0      .1       0     120     .06       0   136.7    .045       0
   190.4     .06       0     240      .1       0
Bank Sta=136.7,190.4
XS Rating Curve= 0 ,0
Exp/Cntr(USF)=0,0
Exp/Cntr=0.3,0.1

Type RM Length L Ch R = 1 ,37637   ,797.3,790.5,771.2
XS GIS Cut Line= 5
2207450.43058747715636.9358465642207561.20036091715626.293899121
2207732.44165264715480.486091467 2207800.7295616715245.961828089
2207777.49693938715143.925416726
#Sta/Elev= 30
       0 1618.64    29.9 1600.96    41.9 1592.31      54 1591.81    70.1 1593.88
   102.2 1595.11   128.4 1592.95   136.9 1591.06   142.6 1587.82   146.7 1584.29
   151.1  1579.4   159.6 1567.22   162.4 1564.16   167.7  1561.1   179.4 1559.46
   190.8 1559.54   202.1 1561.08   233.4 1564.76   298.1 1562.17   335.1 1564.84
   385.5  1563.8   410.5 1564.43   435.4 1567.44   568.8 1567.04   577.1 1568.53
   593.6 1568.94   618.2 1572.66   626.4 1574.88   645.1 1582.67   685.1 1602.99
#Mann= 5 ,-1,0
       0      .1       0  141.28     .06       0   167.7    .045       0
   202.1     .06       0  291.28      .1       0
#XS Ineff= 2 , 0
                          334.73         1566.52
Permanent Ineff=
       F       F
Bank Sta=167.7,202.1
XS Rating Curve= 0 ,0
Exp/Cntr(USF)=0,0
Exp/Cntr=0.3,0.1

Type RM Length L Ch R = 1 ,36847   ,781.3,785.1,785.1
XS GIS Cut Line= 3
 2208196.5264808715787.7587724692208346.19160116715392.696788092
2208424.39499739715257.863346325
#Sta/Elev= 30
       0 1614.15     2.8 1612.54    44.2  1580.1    62.6 1567.13      78 1559.02
      84 1557.29     114 1555.39   156.7    1556   168.4 1551.02   186.7 1549.59
   197.2 1551.12   203.8  1552.3   216.6 1552.18   233.7 1554.18   259.4 1555.03
   293.6 1554.12   310.7 1551.54   323.6 1551.53   327.8 1552.16   332.1  1554.2
     345  1557.6   366.3 1558.46     392  1561.7   404.8 1565.18   413.4 1566.53
   431.2 1572.43     519 1605.82   543.6 1613.93   560.6 1621.05   578.3 1625.99
#Mann= 5 ,-1,0
       0     .07       0      30     .06       0      90      .1       0
   168.4    .045       0   197.2      .1       0
Bank Sta=168.4,197.2
XS Rating Curve= 0 ,0
Exp/Cntr(USF)=0,0
Exp/Cntr=0.3,0.1

Type RM Length L Ch R = 1 ,36061   ,148.2,143.6,141.3
XS GIS Cut Line= 4
2208789.88176878715999.5906976412208798.61897581715926.416588794
 2208919.8477233715673.0375850262208934.04568472715574.744005978
#Sta/Elev= 30
       0 1569.01    11.4 1561.83    25.8 1556.68    46.7 1551.55    54.8 1550.18
    75.1 1547.31    90.8 1546.67    93.8 1545.78  100.211542.249   106.1 1540.43
   108.8 1540.42     115 1540.62   120.81542.227   123.8  1543.6   128.3 1544.02
   163.8 1543.53   183.8 1544.61   225.6 1545.31   274.6 1544.46   314.5 1547.29
   318.9 1549.24   327.8 1555.66   345.6 1563.08   366.6 1568.37   374.6 1569.61
   382.7 1572.41   415.1 1590.89   427.2 1599.41   439.3 1606.57   453.9 1613.87
#Mann= 6 ,-1,0
       0     .06       0  100.21    .045       0   120.8      .1       0
  303.69     .05       0  323.69     .06       0  424.58      .1       0
Bank Sta=100.21,120.8
XS Rating Curve= 0 ,0
Exp/Cntr(USF)=0,0
Exp/Cntr=0.3,0.1

Type RM Length L Ch R = 1 ,35918   ,34,32,31.9
XS GIS Cut Line= 3
2208912.78545585716090.5000229452209003.01896141 715681.79532127
2209004.78824583715587.138604649
#Sta/Elev= 30
       0 1576.08    17.7 1567.52      30 1567.94    62.8 1564.96    75.1 1559.44
    87.8 1555.58    91.5 1554.88   107.9 1554.53   120.1 1550.32   132.4 1547.74
   144.7 1544.03   185.7 1541.43  192.081540.011     198  1538.5   205.3 1538.42
   212.8 1539.94   218.7 1542.26   230.7 1543.61     284 1543.99   304.5 1542.89
   336.1 1543.16   346.2  1543.5   361.8 1545.44   382.3 1551.98   398.7  1559.6
   423.2 1566.47   459.2 1579.71   487.1 1592.06   499.2 1598.96   513.2 1608.11
#Mann= 6 ,-1,0
       0     .06       0      90      .1       0  192.08    .045       0
   212.8      .1       0     300     .05       0     380      .1       0
Bank Sta=192.08,212.8
XS Rating Curve= 0 ,0
Exp/Cntr(USF)=0,0
Exp/Cntr=0.3,0.1

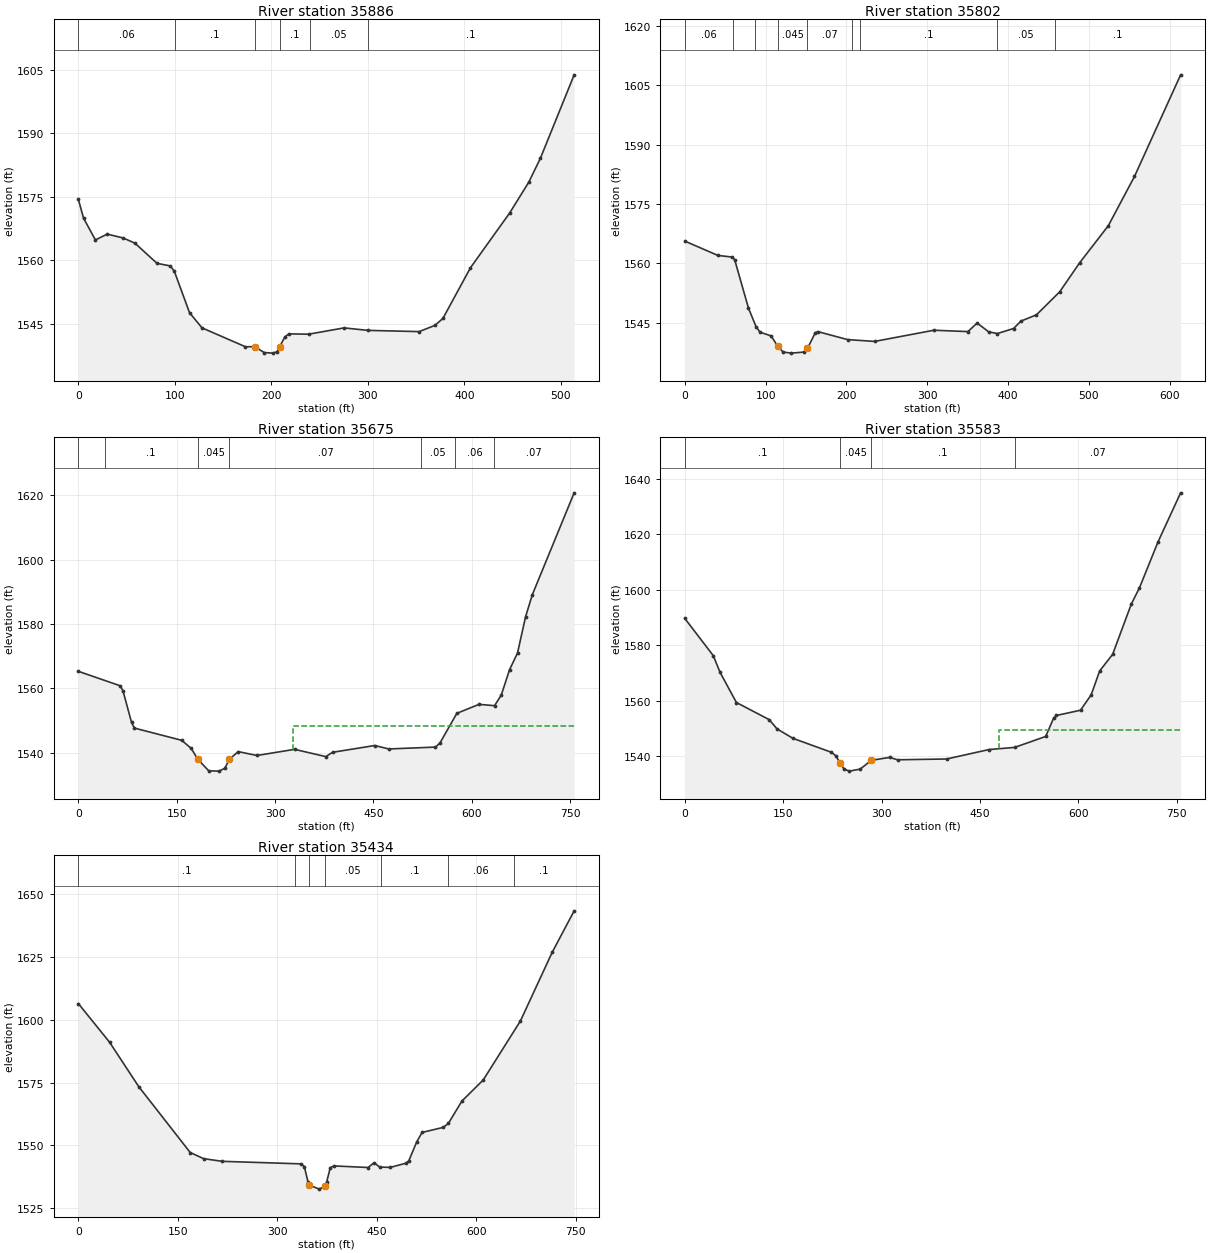
Type RM Length L Ch R = 1 ,35886   ,74,83.5,87.9
XS GIS Cut Line= 3
2208944.63257546716098.4618028482209033.98143881 715681.79532127
2209034.86608102 715594.21574234
#Sta/Elev= 30
       0 1574.42     5.4 1569.95    17.7 1564.79    29.9 1566.17    46.3 1565.27
    58.6 1564.04    81.5 1559.26    95.4 1558.64    99.5 1557.35   115.2 1547.59
   128.1    1544   173.1 1539.53   182.6 1539.54   192.7 1538.15   201.8 1538.02
   205.9 1538.36   208.51539.521     214 1541.86   218.1 1542.57   238.6  1542.5
   275.4 1543.99     300  1543.4   353.1 1543.11   369.5 1544.59   377.7 1546.22
   406.3 1558.23   446.8 1571.14   466.8  1578.5   478.8 1584.16   513.7 1603.85
#Mann= 6 ,-1,0
       0     .06       0     100      .1       0   182.6    .045       0
   208.5      .1       0     240     .05       0     300      .1       0
Bank Sta=182.6,208.5
XS Rating Curve= 0 ,0
Exp/Cntr(USF)=0,0
Exp/Cntr=0.3,0.1

Type RM Length L Ch R = 1 ,35802   ,92.7,127.8,138
XS GIS Cut Line= 4
2208960.60769608716068.5593188962209003.38455371716017.240890755
2209219.88937985715728.2938493182209177.03654337715547.616013081
#Sta/Elev= 30
       0 1565.62    40.9    1562    58.9 1561.58    61.7 1560.92    78.8 1548.68
    88.1 1544.03    93.1 1542.59   106.9 1541.65   115.11538.997   121.7 1537.57
   131.9  1537.3   146.9 1537.56   151.81538.473   161.5 1542.46   164.6 1542.74
   201.5 1540.72   234.9 1540.26   308.3 1543.09   350.3 1542.74   361.8  1544.9
     376 1542.69   386.8 1542.25   406.8 1543.52     416  1545.4   435.2 1546.98
     464 1552.81   488.6 1560.13   524.1  1569.5   556.5 1581.96   613.6 1607.65
#Mann= 9 ,-1,0
       0     .06       0      60      .1       0   86.81     .07       0
   115.1    .045       0   151.8     .07       0  206.81     .05       0
  216.81      .1       0  386.81     .05       0  457.87      .1       0
Bank Sta=115.1,151.8
XS Rating Curve= 0 ,0
Exp/Cntr(USF)=0,0
Exp/Cntr=0.3,0.1

Type RM Length L Ch R = 1 ,35675   ,103.3,92.1,98.2
XS GIS Cut Line= 6
2208965.86398853716072.8071787162209029.62015271716019.693260343
2209107.24104517716013.820413959 2209333.4168051715961.221400023
2209465.04195514715889.0641003172209672.69311545715932.149067101
#Sta/Elev= 30
       0 1565.28    63.9 1560.78    68.2 1559.13    81.1 1549.45    85.5 1547.64
   157.7 1543.83   172.2 1541.31   182.3 1537.92   198.9 1534.35   214.5 1534.26
   223.3 1535.14  230.41 1537.94   243.8 1540.32   272.4 1539.12   329.8 1541.03
   377.5 1538.77   387.7 1540.11   452.1 1542.22   473.4 1541.15   544.7 1541.73
   551.4 1542.96   577.3 1552.22   611.1 1555.01   634.8  1554.6     645 1557.87
   657.6 1565.75   669.8 1570.96   682.1 1582.22   692.3 1589.04   756.2 1620.75
#Mann= 7 ,-1,0
       0     .06       0      40      .1       0   182.3    .045       0
  230.41     .07       0  523.29     .05       0  574.09     .06       0
  634.09     .07       0
#XS Ineff= 2 , 0
                          327.43         1548.18
Permanent Ineff=
       F       F
Bank Sta=182.3,230.41
XS Rating Curve= 0 ,0
Exp/Cntr(USF)=0,0
Exp/Cntr=0.3,0.1

Type RM Length L Ch R = 1 ,35583   ,159.2,148.3,123.8
XS GIS Cut Line= 6
2208966.85248815716163.5508684892209030.60865233716110.436950116
2209108.22954479716104.5641037332209334.40530472716051.965089796
2209466.03045476715979.8077900912209673.68161507716022.892756874
#Sta/Elev= 30
       0 1589.66    43.4 1576.22    53.8 1570.17    78.7 1559.28   128.7 1553.09
   140.7 1549.74   164.9 1546.33   223.7 1541.28   230.4 1540.02   236.71537.474
   242.8 1535.22     251 1534.48   267.6 1535.22   284.51538.397   312.3 1539.44
   324.6 1538.58   399.3 1538.87   464.1 1542.28     503 1543.05   550.4 1547.01
   562.6 1553.67   566.7 1554.59   603.5 1556.49   619.8 1562.05   632.7 1570.67
   652.5 1576.68   681.1 1594.92   693.4 1600.71   721.9 1617.42   756.2 1635.05
#Mann= 4 ,-1,0
       0      .1       0   236.7    .045       0   284.5      .1       0
  503.29     .07       0
#XS Ineff= 2 , 0
                          478.92         1549.38
Permanent Ineff=
       F       F
Bank Sta=236.7,284.5
XS Rating Curve= 0 ,0
Exp/Cntr(USF)=0,0
Exp/Cntr=0.3,0.1

Type RM Length L Ch R = 1 ,35434   ,517.4,529.7,541.4
XS GIS Cut Line= 5
2208986.12287491716278.8300853622209138.31864886716200.533344259
2209293.75318423716190.258145359 2209380.9046795716107.844804342
2209681.15243014 716123.40614303
#Sta/Elev= 30
       0 1606.52    47.3 1591.02      91 1573.42   168.7 1547.12     189 1544.67
   217.1 1543.61   335.8  1542.6   340.7 1541.54   346.4 1535.24   348.51534.104
   363.3 1532.53   371.8 1533.72   374.3 1535.28   379.8 1541.09   385.3 1541.78
   436.9 1541.15   445.9 1543.04   454.2 1541.33   470.3 1541.19   494.2 1542.89
   498.2 1543.83   510.2 1551.39   518.2 1555.12   550.3 1557.16   557.9 1558.74
   578.3 1567.65   610.4 1576.04   666.4 1599.53   714.5    1627   747.5 1643.48
#Mann= 7 ,-1,0
       0      .1       0  326.93     .05       0   348.5    .045       0
   371.8     .05       0  456.88      .1       0  556.88     .06       0
  656.88      .1       0
Bank Sta=348.5,371.8
XS Rating Curve= 0 ,0
Exp/Cntr(USF)=0,0
Exp/Cntr=0.3,0.1