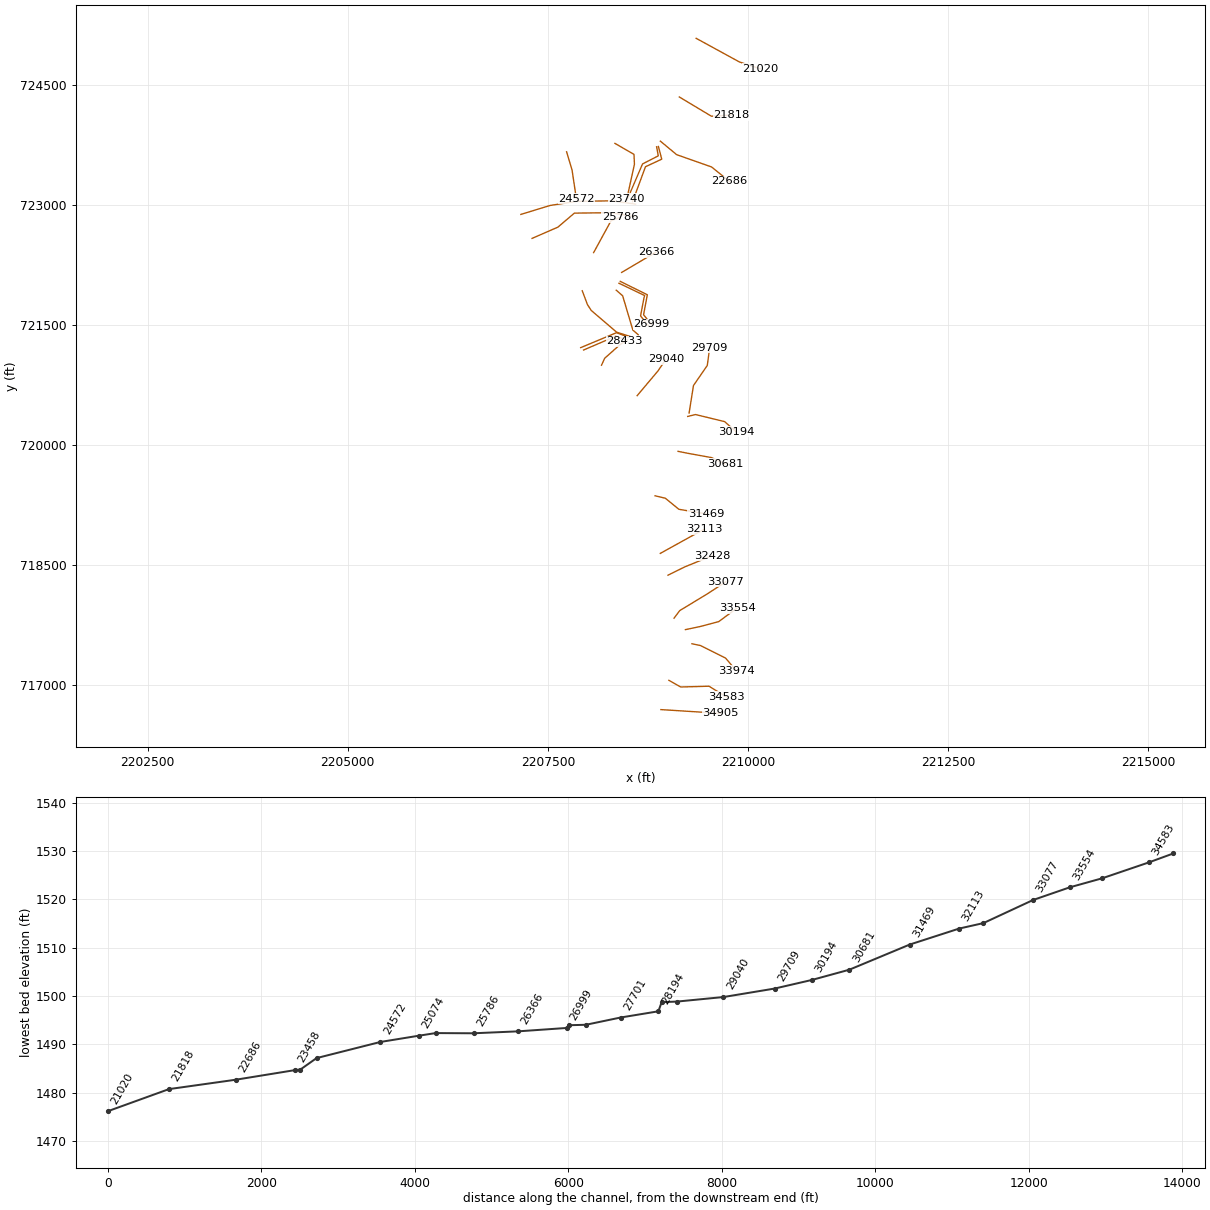
HEC-RAS study SANDRN1.prj: SANDRN1

--- SANDRN1.g01 (geometry) --- (continued)

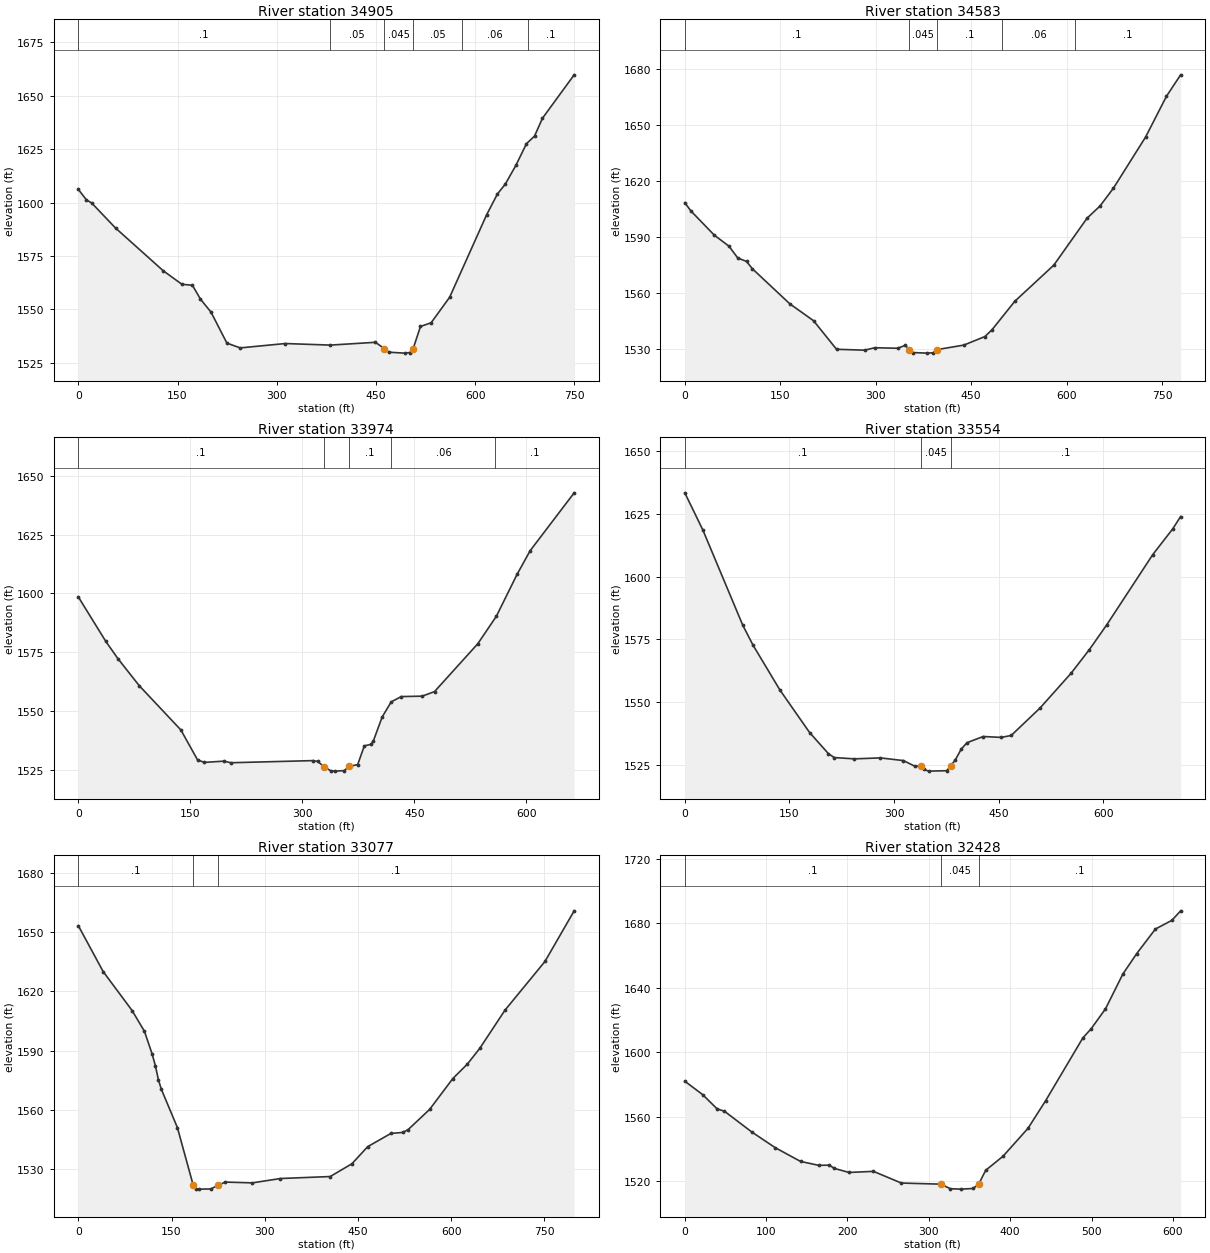
Type RM Length L Ch R = 1 ,34905   ,318.4,321.6,323.3
XS GIS Cut Line= 2
2208911.97736105716695.6681467562209659.98724077716648.456477819
#Sta/Elev= 30
       0 1606.17    12.2 1601.32    20.2 1599.82    56.3 1588.09   128.5 1568.06
   156.5 1561.79   172.5 1561.29   184.6 1554.83   200.6 1548.71   224.6 1534.22
   244.7 1531.99   312.8 1534.03     381  1533.3   449.1 1534.61   462.5 1531.67
   469.1 1529.98   493.2 1529.54   501.2 1529.83   506.2  1531.7   517.2 1542.03
   533.3 1543.75   561.3 1555.71     617 1594.18   633.5 1604.04   645.5 1608.71
   661.5  1617.5   677.4  1627.6   689.6 1631.14   701.6 1639.51   749.5 1659.83
#Mann= 6 ,-1,0
       0      .1       0     380     .05       0   462.5    .045       0
   506.2     .05       0     580     .06       0     680      .1       0
Bank Sta=462.5,506.2
XS Rating Curve= 0 ,0
Exp/Cntr(USF)=0,0
Exp/Cntr=0.3,0.1

Type RM Length L Ch R = 1 ,34583   ,623.6,608.6,598.7
XS GIS Cut Line= 4
2209011.77395856717061.5289617592209158.94803158716978.117245946
2209513.21215077716987.5462776622209731.05005395716853.966431376
#Sta/Elev= 30
       0 1608.22     9.7 1603.75    46.4 1590.82    69.4 1584.94    83.2 1578.62
      97 1576.76   106.2 1572.84   164.9  1554.1   202.4    1545   238.4 1529.73
   282.5 1529.25   298.4 1530.55   334.5 1530.28   346.5 1531.85   352.6 1529.56
   358.5 1527.97     381 1527.67   390.5 1527.88  396.69 1529.57   438.5 1531.97
   471.5 1536.54   482.5 1540.09   518.5 1555.41   579.8 1574.77   632.1 1599.92
   652.5 1606.46   673.5 1615.98   724.1 1643.39   756.9 1665.21   779.1 1676.67
#Mann= 5 ,-1,0
       0      .1       0   352.6    .045       0  396.69      .1       0
  499.17     .06       0  613.56      .1       0
Bank Sta=352.6,396.69
XS Rating Curve= 0 ,0
Exp/Cntr(USF)=0,0
Exp/Cntr=0.3,0.1

Type RM Length L Ch R = 1 ,33974   ,400.3,420.2,431.7
XS GIS Cut Line= 4
2209300.21849802 717518.053996362209407.08237505717495.448176219
 2209719.4537079717339.2625097922209853.03355419717183.076843365
#Sta/Elev= 30
       0 1598.52    36.8 1579.59    53.1 1572.22    81.7  1560.7   137.3 1541.92
   159.6 1529.19   168.6  1528.1   195.2 1528.63   204.2 1527.95   314.5 1528.86
   320.6 1528.49     329  1526.3   338.3 1524.45   344.3 1524.38   356.2  1524.6
   362.2 1526.37   374.1 1527.15     383 1535.13     392 1535.79     395 1537.16
   406.9 1547.43     419 1553.85   432.4 1556.11   460.5 1556.29     477 1558.23
   534.9 1578.58   559.8 1590.28   587.5  1608.1   605.1 1618.22     664 1642.83
#Mann= 5 ,-1,0
       0      .1       0     329    .045       0   362.2      .1       0
  419.23     .06       0  558.47      .1       0
Bank Sta=329,362.2
XS Rating Curve= 0 ,0
Exp/Cntr(USF)=0,0
Exp/Cntr=0.3,0.1

Type RM Length L Ch R = 1 ,33554   ,468.6,477.4,486.1
XS GIS Cut Line= 4
2209218.85320914717694.4900177122209407.69988489717734.324863378
2209634.90604165717794.8148142042209862.11219841717963.006384794
#Sta/Elev= 30
       0 1633.43    25.9 1618.61    83.1 1580.68    97.9 1572.68   136.3 1554.88
   178.9 1537.91   205.9 1529.48   214.2 1527.93   243.2 1527.41   280.4 1527.79
   313.5 1526.72   330.1 1524.43   338.4 1524.59   342.5 1523.27   349.4 1522.52
   375.5 1522.69  381.18 1524.62     388 1527.08   396.3 1531.31   404.6 1533.85
   427.8 1536.32   453.6 1535.96   467.9 1536.73   509.3 1547.68   553.7 1561.51
     580 1570.96   605.2 1580.95   670.9 1608.83   699.5 1619.08   710.8 1623.99
#Mann= 3 ,-1,0
       0      .1       0   338.4    .045       0  381.18      .1       0
Bank Sta=338.4,381.18
XS Rating Curve= 0 ,0
Exp/Cntr(USF)=0,0
Exp/Cntr=0.3,0.1

Type RM Length L Ch R = 1 ,33077   ,647,648.5,643.2
XS GIS Cut Line= 4
2209076.08773792717837.2856796222209147.66598478717932.168471976
2209490.57572557718140.2447709982209723.62118047718291.724316687
#Sta/Elev= 30
       0 1653.19      40 1629.97    86.5 1610.28   106.4 1599.75   118.9 1588.14
   124.1 1582.21   128.8 1575.34   133.5 1570.49   159.4 1551.06     185 1521.74
   189.6 1520.08   194.3  1519.9   213.1 1519.97   224.8 1521.84   236.4 1523.47
   280.1 1523.07   325.3 1525.27   405.3 1526.27   440.3 1532.75   465.7  1541.4
   503.1  1548.1   521.9 1548.57   530.5 1549.95   565.2  1560.2   602.7 1575.87
   625.9 1583.12   645.9 1591.08   686.6 1610.47   750.9 1635.09   797.9 1660.72
#Mann= 3 ,-1,0
       0      .1       0     185    .045       0   224.8      .1       0
Bank Sta=185,224.8
XS Rating Curve= 0 ,0
Exp/Cntr(USF)=0,0
Exp/Cntr=0.3,0.1

Type RM Length L Ch R = 1 ,32428   ,311.7,315.4,318.5
XS GIS Cut Line= 4
 2209000.4992403718374.6331233412209210.00102121718477.908649142
2209354.58675733718536.9232353132209558.18707963718619.543655954
#Sta/Elev= 30
       0 1582.09    21.9 1573.78    39.8 1564.89    48.7 1563.47    82.3 1550.59
   111.1 1540.85   142.3  1532.3   164.6 1529.87   177.6 1529.99   183.9 1527.97
   201.8 1525.46   231.9 1526.14   266.2 1518.88   314.5  1518.2   326.6 1515.35
   339.6 1515.11   354.3  1515.5   361.2 1518.19   369.9  1526.8   391.2 1535.53
   421.9 1552.85   443.4 1569.86   489.4 1609.02   499.4 1614.56   517.1 1626.96
   538.5 1648.59   555.5 1661.27   578.5 1676.52   598.7 1681.89   609.5 1687.82
#Mann= 3 ,-1,0
       0      .1       0   314.5    .045       0   361.2      .1       0
Bank Sta=314.5,361.2
XS Rating Curve= 0 ,0
Exp/Cntr(USF)=0,0
Exp/Cntr=0.3,0.1

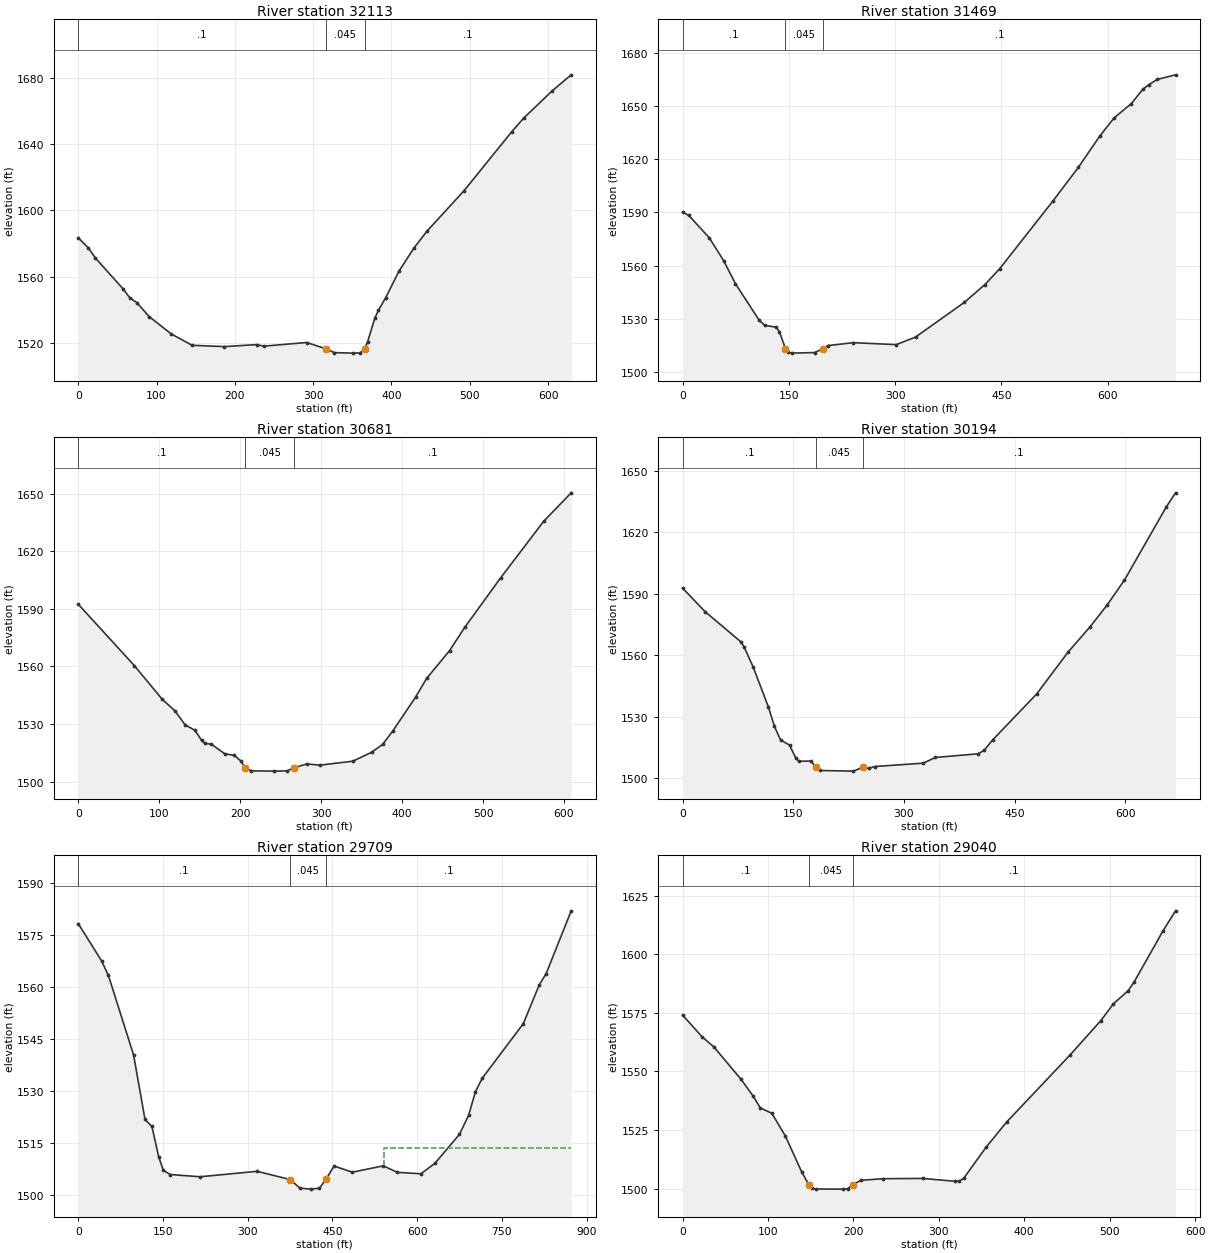
Type RM Length L Ch R = 1 ,32113   ,660.7,644.3,580.3
XS GIS Cut Line= 3
2208904.87766659718646.7260342892209322.69487503718878.106878802
2209457.52831679718948.020515274
#Sta/Elev= 30
       0 1583.52    13.1 1577.34    22.1 1571.23    57.2 1552.77      66 1547.23
    74.9 1544.44    90.6 1535.99     119 1525.51   145.4  1518.7   186.7 1517.91
   227.8 1519.12     237 1518.18   291.8 1520.38   316.2 1516.62   327.1 1514.28
   351.3 1513.98   360.3 1514.13  365.79 1516.66   369.6 1520.86   378.7 1534.96
   383.3 1539.69   392.7 1547.44   409.6  1563.4     429 1577.52   445.6 1587.62
   492.9 1611.99   553.8 1647.55   569.4 1655.88   605.4 1672.13   629.5 1681.72
#Mann= 3 ,-1,0
       0      .1       0   316.2    .045       0  365.79      .1       0
Bank Sta=316.2,365.79
XS Rating Curve= 0 ,0
Exp/Cntr(USF)=0,0
Exp/Cntr=0.3,0.1

Type RM Length L Ch R = 1 ,31469   ,761.1,787.3,792.8
XS GIS Cut Line= 4
2208839.49246075719366.2694925282208967.32670651719335.988524627
2209136.52335934719197.7447705232209477.59311108719140.622306033
#Sta/Elev= 30
       0 1590.18     8.9 1588.29    37.7 1575.71      58 1562.84    74.7 1549.78
   107.8 1529.45   115.8  1526.3   132.5 1525.31   136.8 1522.57   145.3 1513.18
   148.5 1511.27   153.9 1510.67   186.4 1510.99  198.41 1513.17     205 1514.93
   240.9 1516.56   301.7 1515.47   328.8 1519.73   397.5 1539.23   426.6 1549.29
   447.3 1558.13   522.8  1596.5   558.5 1615.35   588.8 1633.05   609.1 1643.34
   633.4 1651.39   649.6 1659.45   657.7 1661.92   669.9    1665   695.7 1667.59
#Mann= 3 ,-1,0
       0      .1       0   145.3    .045       0  198.41      .1       0
Bank Sta=145.3,198.41
XS Rating Curve= 0 ,0
Exp/Cntr(USF)=0,0
Exp/Cntr=0.3,0.1

Type RM Length L Ch R = 1 ,30681   ,489.4,487.3,485.3
XS GIS Cut Line= 4
2209126.67706078719921.2389950682209246.52900901 719897.26860542
2209544.66073025719843.3352287142209710.95530843 719765.43146236
#Sta/Elev= 30
       0  1592.4    69.3 1560.43   103.5 1543.01   119.8  1536.7     132 1529.55
   144.2 1526.72   152.4 1521.45   156.4 1519.86   164.5 1519.51   180.8 1514.55
     193 1513.63   201.1 1510.62   206.3 1507.24   213.3 1505.63   241.8 1505.46
     258 1505.59   266.2 1507.19   282.4 1509.18   298.7 1508.58   339.3 1510.65
   362.4 1515.29   375.9 1519.36   388.8 1526.55   416.6 1543.98   430.3 1553.74
   458.6  1568.2   477.4 1580.35   521.8 1606.17   574.8 1635.55   608.8 1650.38
#Mann= 3 ,-1,0
       0      .1       0   206.3    .045       0   266.2      .1       0
Bank Sta=206.3,266.2
XS Rating Curve= 0 ,0
Exp/Cntr(USF)=0,0
Exp/Cntr=0.3,0.1

Type RM Length L Ch R = 1 ,30194   ,428.6,485.1,517
XS GIS Cut Line= 4
  2209247.182268 720357.389753932209344.34002789720381.193682538
2209708.26085096720292.6734010162209853.73478377720164.980074775
#Sta/Elev= 30
       0 1592.84    30.4 1581.34    79.3 1566.48    83.4 1564.07    95.7 1554.25
   116.3 1534.77   124.6 1525.21   132.8 1518.58   145.1 1516.03   153.4  1509.8
   157.5  1508.2     174 1508.24  181.11 1505.16   186.3 1503.65   231.6 1503.34
   243.9 1505.14   252.2 1504.66   260.4 1505.59   326.3 1507.24   342.7 1510.02
   400.4 1511.81   408.6 1513.46   420.7 1518.76   479.9 1541.05   522.3 1561.44
   552.6 1574.01   575.6 1584.63   598.9 1596.72   655.5 1632.43   668.1 1639.36
#Mann= 3 ,-1,0
       0      .1       0  181.11    .045       0   243.9      .1       0
Bank Sta=181.11,243.9
XS Rating Curve= 0 ,0
Exp/Cntr(USF)=0,0
Exp/Cntr=0.3,0.1

Type RM Length L Ch R = 1 ,29709   ,653.6,668.5,659.9
XS GIS Cut Line= 4
2209264.47860118 720400.320607952209319.22526269 720743.71239287
2209491.64931514720994.4298699832209521.30296327  721213.2347182
#Sta/Elev= 30
       0 1578.22    41.4 1567.44    53.5 1563.24    98.1 1540.27   118.3 1521.67
   130.5 1519.65   142.6 1510.83   150.7    1507   162.9 1505.78   215.5 1505.13
   316.8  1506.7   375.4 1504.32   392.6 1501.82   412.7 1501.56   427.2 1501.85
   438.6 1504.36     453 1508.22   485.4 1506.45     540 1508.28   565.2  1506.4
   606.8 1505.99   631.4 1508.99     675 1517.37   691.1 1522.83   703.2 1529.63
   715.3 1533.56     788 1549.31   816.3 1560.52   828.4 1563.74   872.8 1581.89
#Mann= 3 ,-1,0
       0      .1       0   375.4    .045       0   438.6      .1       0
#XS Ineff= 2 , 0
                          540.79         1513.39
Permanent Ineff=
       F       F
Bank Sta=375.4,438.6
XS Rating Curve= 0 ,0
Exp/Cntr(USF)=0,0
Exp/Cntr=0.3,0.1

Type RM Length L Ch R = 1 ,29040   ,607.1,607,597.7
XS GIS Cut Line= 3
2208615.89100655720617.1467844392208876.88547544720927.463042734
2208973.47397968721069.263187253
#Sta/Elev= 30
       0 1574.07    22.9 1564.74    36.6  1560.5    68.4 1546.67    82.6 1539.53
    91.1 1534.38   104.6 1532.15   120.3 1522.49   139.3 1507.31   147.8 1501.65
   151.6  1500.2   155.8 1499.84   188.2  1499.8   193.3 1499.96   199.3 1501.71
   209.1 1503.58   235.2 1504.25   281.3 1504.35   318.9 1503.16   324.1 1503.27
   329.3 1504.49   355.1 1517.56   379.5 1528.45     454 1557.15   489.7 1571.68
   504.4 1578.83   521.4 1584.34   528.6 1588.12   562.4 1609.91   577.1 1618.48
#Mann= 3 ,-1,0
       0      .1       0   147.8    .045       0   199.3      .1       0
Bank Sta=147.8,199.3
XS Rating Curve= 0 ,0
Exp/Cntr(USF)=0,0
Exp/Cntr=0.3,0.1

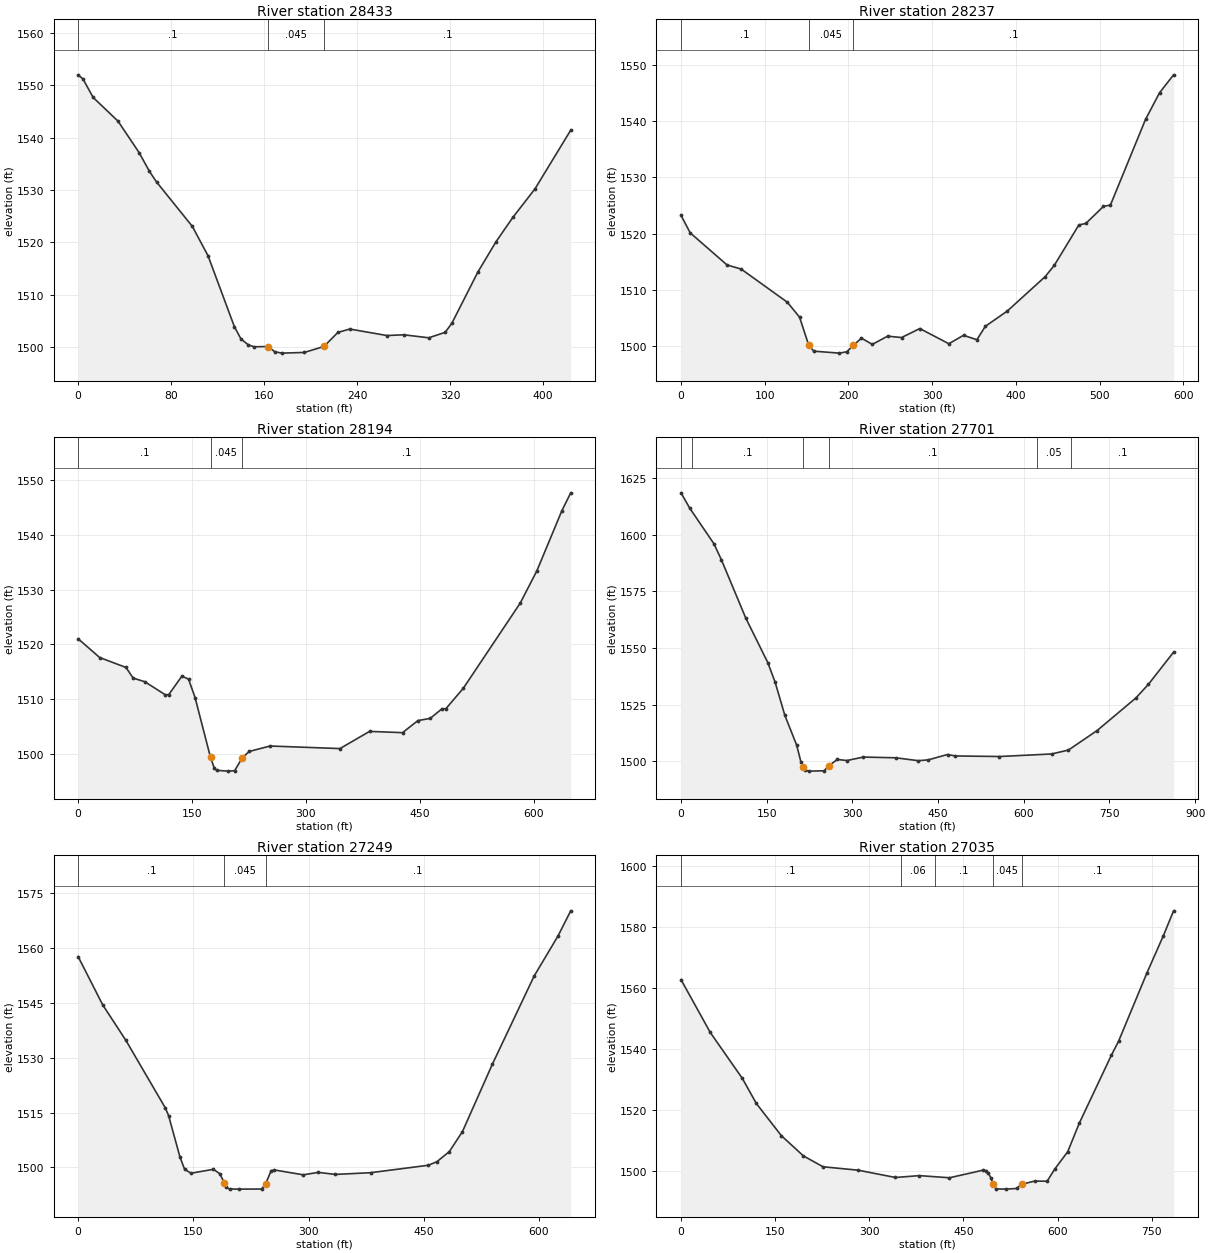
Type RM Length L Ch R = 1 ,28433   ,212.8,196.6,192.3
XS GIS Cut Line= 4
2208170.51627582720997.4440856512208209.61797393721083.737488382
2208402.42979566721254.9759594262208461.75651004721294.077657538
#Sta/Elev= 30
       0    1552     4.1 1551.22    12.9 1547.68    34.3 1543.15    52.4 1537.16
    61.2 1533.61    67.5 1531.52    98.2 1523.06   111.7 1517.46   134.4  1503.9
   140.1 1501.55   146.3 1500.46   151.1 1500.07   163.2 1500.12   169.2 1499.12
   175.2 1498.86   194.5 1498.99   211.4 1500.13   223.4 1502.81   233.6 1503.46
   265.6 1502.22   280.1 1502.36   301.6 1501.79   315.7 1502.83   321.4 1504.54
   343.9 1514.37   359.5 1520.15   373.9 1524.77     393 1530.24   423.7 1541.43
#Mann= 3 ,-1,0
       0      .1       0   163.2    .045       0   211.4      .1       0
Bank Sta=163.2,211.4
XS Rating Curve= 0 ,0
Exp/Cntr(USF)=0,0
Exp/Cntr=0.3,0.1

Type RM Length L Ch R = 1 ,28237   ,39.9,43.2,41.1
XS GIS Cut Line= 3
2207946.08820645721187.1176228752208345.81542791721358.585310767
 2208492.1636456721312.714973879
#Sta/Elev= 30
       0 1523.25      11 1520.13    54.9 1514.44    71.9 1513.69     127  1507.8
   141.6 1505.14   152.4 1500.21   158.5  1499.1     189 1498.75     198 1498.99
   205.8 1500.12   215.5 1501.41   228.5 1500.31   246.8 1501.77   263.4 1501.52
   285.2 1503.12   319.9 1500.42   337.4 1501.92   353.4 1501.13   363.5 1503.52
   389.6 1506.22     435 1512.36   445.8 1514.35   475.2 1521.55   483.5 1521.81
   504.5 1524.83   512.9 1525.09   554.8 1540.31   571.6 1545.06   588.3 1548.24
#Mann= 3 ,-1,0
       0      .1       0   152.4    .045       0   205.8      .1       0
Bank Sta=152.4,205.8
XS Rating Curve= 0 ,0
Exp/Cntr(USF)=0,0
Exp/Cntr=0.3,0.1

Type RM Length L Ch R = 1 ,28194   ,530,493,455.5
XS GIS Cut Line= 3
2207910.04722747721216.6056965892208356.73693669721403.363496777
2208510.73021053721345.479500228
#Sta/Elev= 30
       0 1521.03    28.3 1517.61      63 1515.79    72.4 1513.85    87.7 1513.19
     115 1510.78   119.4 1510.85   136.7 1514.22   145.4 1513.64     154 1510.28
   174.3 1499.35   179.4 1497.35   182.4 1496.99   197.4 1496.85   206.1 1496.93
   216.1 1499.28   225.2 1500.44   252.8 1501.44   344.8 1500.97   383.8 1504.11
   427.2 1503.88   447.4 1506.08   463.7 1506.49   479.2 1508.25   484.2 1508.24
   507.2 1511.98   582.2 1527.55   604.1 1533.44   636.9 1544.38   648.7  1547.7
#Mann= 3 ,-1,0
       0      .1       0   174.3    .045       0   216.1      .1       0
Bank Sta=174.3,216.1
XS Rating Curve= 0 ,0
Exp/Cntr(USF)=0,0
Exp/Cntr=0.3,0.1

Type RM Length L Ch R = 1 ,27701   ,457.1,451.7,443
XS GIS Cut Line= 5
2207929.38450129721927.3112108782207994.30054608721754.693546326
2208042.66615673721680.5745456642208359.33339513721409.725228716
2208523.95645697721357.820454321
#Sta/Elev= 30
       0  1618.6    15.1 1611.87    57.8    1596    70.7 1588.98   113.4  1563.2
   151.9 1543.53   164.7  1534.9   181.8 1520.18   202.5 1506.99   210.1 1499.42
   213.31497.436   217.1 1496.02   224.4 1495.56   250.5 1495.71   258.7 1497.97
   273.6 1500.71   290.6 1500.25     319 1501.78   375.7 1501.46   415.4 1500.17
   432.8 1500.54   466.5 1502.91   480.2 1502.27   557.3 1502.02   648.6 1503.14
   678.2 1504.88   728.3 1513.49     796 1527.85   818.3 1533.98   862.2 1548.16
#Mann= 6 ,-1,0
       0     .06       0      20      .1       0   213.3    .045       0
   258.7      .1       0  622.92     .05       0  682.92      .1       0
Bank Sta=213.3,258.7
XS Rating Curve= 0 ,0
Exp/Cntr(USF)=0,0
Exp/Cntr=0.3,0.1

Type RM Length L Ch R = 1 ,27249   ,233.8,214.3,202.9
XS GIS Cut Line= 4
2208354.46321968 721934.252972932208434.55428409721863.869916328
2208561.97188656721435.5040718362208628.71444023721378.469525968
#Sta/Elev= 30
       0  1557.6    31.9 1544.44    62.2 1534.69   113.6 1516.21   117.8  1514.1
   132.6 1502.79   138.6 1499.47     147 1498.41   176.2 1499.48   184.5 1498.24
   190.5 1495.67   192.9 1494.55   197.1 1494.09   209.6 1494.06   238.8 1494.09
  243.911495.449   251.3  1499.1   255.5  1499.3   293.1 1497.97   312.7 1498.64
   334.8 1498.08   380.7 1498.55   455.8 1500.58   467.1 1501.56   483.2 1504.31
   500.3 1509.76   539.3 1528.21   593.6 1552.27   624.8 1563.26   641.3 1570.12
#Mann= 3 ,-1,0
       0      .1       0   190.5    .045       0  243.91      .1       0
Bank Sta=190.5,243.91
XS Rating Curve= 0 ,0
Exp/Cntr(USF)=0,0
Exp/Cntr=0.3,0.1

Type RM Length L Ch R = 1 ,27035   ,60.1,35.8,34.2
XS GIS Cut Line= 5
2208388.00100723722021.3256583932208709.57876583721867.211034456
  2208701.084259721840.5140129862208658.12773212721612.908095318
2208763.24746117721481.027947619
#Sta/Elev= 30
       0  1562.7    46.6 1545.37    97.8 1530.27     120 1522.08   159.9  1511.5
   195.1 1504.86   226.4  1501.3   282.1 1500.19   341.7 1497.79   379.7  1498.4
   427.8  1497.7   481.6  1500.2   485.7 1500.05   489.8 1499.23   493.8 1497.63
   497.4 1495.54     502 1494.06   518.1 1493.97   534.6 1494.18   542.7 1495.56
   563.3  1496.6   583.4 1496.57   595.6 1500.56   616.2 1506.24   634.6 1515.58
   685.8 1537.91   697.2 1542.46   742.7 1565.03   768.4    1577   784.9 1585.28
#Mann= 5 ,-1,0
       0      .1       0     350     .06       0  404.62      .1       0
   497.4    .045       0   542.7      .1       0
Bank Sta=497.4,542.7
XS Rating Curve= 0 ,0
Exp/Cntr(USF)=0,0
Exp/Cntr=0.3,0.1

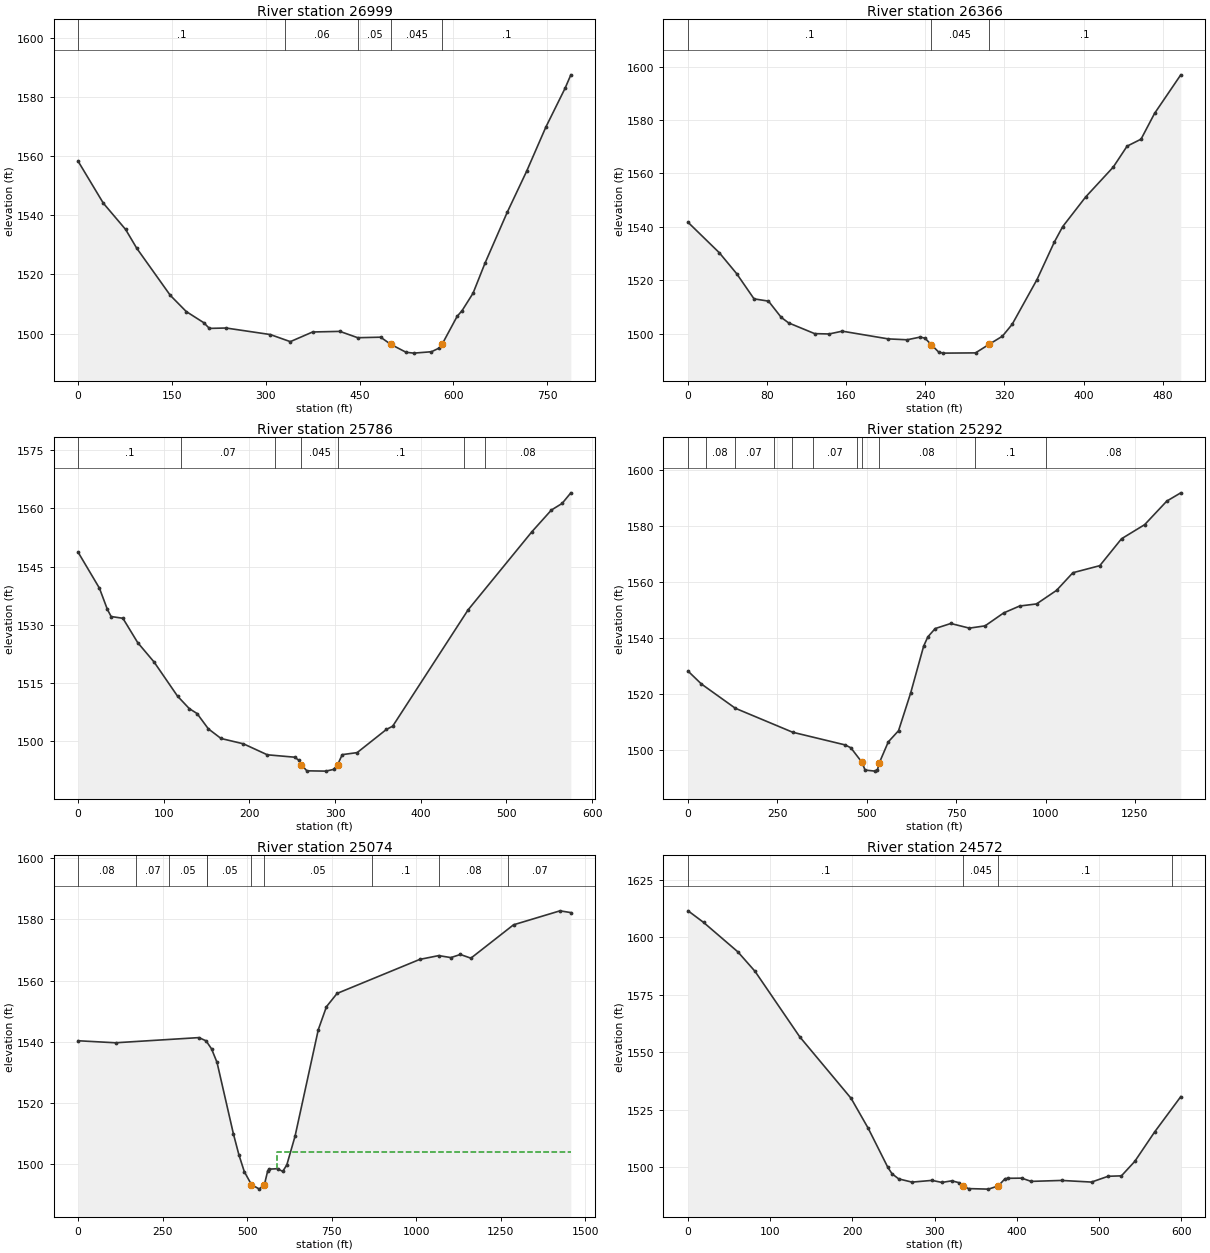
Type RM Length L Ch R = 1 ,26999   ,538.8,633.1,708.5
XS GIS Cut Line= 5
2208404.16180925722044.7245080022208742.72858152 721877.26137333
2208721.98330284721767.2562875252208695.61537694721628.026232698
2208793.37978908721505.874258945
#Sta/Elev= 30
       0 1558.23    40.2 1544.09    75.9 1535.19    93.7 1528.84   147.3 1512.93
   172.8 1507.46   200.8 1503.69   209.8 1501.76   236.5 1501.89   307.2 1499.68
   339.2 1497.28   374.9 1500.55   418.5 1500.75     447 1498.61   483.6 1498.79
   499.8 1496.38   524.3 1493.69   536.6  1493.4   564.9 1493.87   577.3 1495.12
     582 1496.43   605.9 1505.81   613.9 1507.78   631.4 1513.65   650.4 1523.75
   686.2 1541.07     717 1554.84   747.7 1569.75   778.5 1582.91   787.8 1587.47
#Mann= 5 ,-1,0
       0      .1       0     330     .06       0  447.72     .05       0
   499.8    .045       0     582      .1       0
Bank Sta=499.8,582
XS Rating Curve= 0 ,0
Exp/Cntr(USF)=0,0
Exp/Cntr=0.3,0.1

Type RM Length L Ch R = 1 ,26366   ,565.7,580.2,600.1
XS GIS Cut Line= 2
2208421.89549292722156.1273046762208850.99506068722409.517997707
#Sta/Elev= 30
       0 1541.66    31.6 1530.27    49.1 1522.46    66.7 1513.01    81.3 1512.17
    94.2 1506.08   101.7 1504.01     128    1500   142.6 1499.87   155.9 1500.92
   202.4 1498.03   221.5  1497.7   234.9 1498.72   239.6 1498.28   245.9  1495.9
   253.5 1493.07   258.1  1492.7   290.7 1492.79   304.6 1496.03   317.9 1499.04
   327.8 1503.51   352.9 1520.26   370.4 1534.28   378.9 1540.08   402.1 1551.17
     430 1562.35     444 1570.19   458.1  1572.8   471.8 1582.46   498.3 1596.89
#Mann= 3 ,-1,0
       0      .1       0   245.9    .045       0   304.6      .1       0
Bank Sta=245.9,304.6
XS Rating Curve= 0 ,0
Exp/Cntr(USF)=0,0
Exp/Cntr=0.3,0.1

Type RM Length L Ch R = 1 ,25786   ,504.3,493.8,482.5
XS GIS Cut Line= 3
 2208071.6630839722403.3797114522208289.91200199722802.886205575
2208402.73559523722843.576681828
#Sta/Elev= 30
       0 1548.67    24.8 1539.44    34.1 1533.96    38.5 1532.13    52.2 1531.68
    69.5 1525.41    88.7 1520.39     116 1511.62   129.7 1508.41   138.8 1507.14
     152 1503.19   166.8 1500.71     193 1499.33   220.8 1496.51   252.7 1495.89
   257.3 1495.16  260.491493.963     267 1492.38   289.2  1492.3   298.3 1492.75
   302.9 1493.96   308.3 1496.55   325.7 1497.07   359.8 1503.03   367.2 1503.88
   455.2 1533.84   529.9 1554.02   552.5 1559.57     565 1561.27   575.2    1564
#Mann= 7 ,-1,0
       0      .1       0     120     .07       0     230     .06       0
  260.49    .045       0   302.9      .1       0     450     .07       0
  475.23     .08       0
Bank Sta=260.49,302.9
XS Rating Curve= 0 ,0
Exp/Cntr(USF)=0,0
Exp/Cntr=0.3,0.1

Type RM Length L Ch R = 1 ,25292   ,230.4,218.3,204.2
XS GIS Cut Line= 5
2207302.91513061722581.4205453722207625.16705643722721.647324808
2207831.46222233722896.9307991032208285.85092108722902.324136774
2208583.83282738722853.784097738
#Sta/Elev= 30
       0 1528.08    37.2 1523.49   132.2 1514.81   292.6 1506.24   439.4 1501.71
   455.4 1500.68   486.6 1495.47   495.1 1492.71   523.5 1492.34   529.9 1492.88
  535.25 1495.38   560.1 1502.79   588.8 1506.79   622.9 1520.36   659.1 1537.05
   670.9 1540.36   691.4 1543.31   734.9 1545.12   786.9 1543.46   830.9 1544.27
   882.9 1548.89   927.5 1551.36   974.9 1552.11  1030.9 1556.96  1076.6 1563.27
  1151.9 1565.79  1212.7 1575.41  1277.5 1580.46  1339.4 1588.88  1378.5 1591.83
#Mann= 11 ,-1,0
       0     .07       0      50     .08       0     130     .07       0
     240      .1       0     290     .03       0     350     .07       0
  471.44     .08       0   486.6    .045       0  535.25     .08       0
  802.15      .1       0 1002.15     .08       0
Bank Sta=486.6,535.25
XS Rating Curve= 0 ,0
Exp/Cntr(USF)=0,0
Exp/Cntr=0.3,0.1

Type RM Length L Ch R = 1 ,25074   ,548.2,502.1,472.2
XS GIS Cut Line= 5
2207162.68835117722880.7507860912207528.08697836722992.662542757
 2207859.7772451723043.8992506282208303.37926851723050.640922716
2208595.96783714723008.842555768
#Sta/Elev= 30
       0 1540.31   110.4 1539.65     357 1541.34   378.1 1540.29   394.4 1537.67
   410.6 1533.24   459.1 1509.86   475.3 1503.03   491.4 1497.48   512.4 1493.29
     536  1491.8   548.2 1493.19   552.2 1493.95   560.3 1497.68   564.4 1498.33
   589.5 1498.48   604.9 1497.59     617 1499.72   641.3 1509.07   710.1 1543.93
   734.2 1551.44   765.6 1555.78  1010.2 1566.91  1066.2 1568.15  1102.2  1567.5
  1130.2 1568.52  1161.4 1567.31  1287.5 1578.22  1424.9 1582.79    1457 1582.21
#Mann= 10 ,-1,0
       0     .08       0     170     .07       0     270     .05       0
     380     .07       0  382.15     .05       0   512.4    .045       0
   548.2     .05       0  867.78      .1       0 1067.78     .08       0
 1271.43     .07       0
#XS Ineff= 2 , 0
                          589.03          1503.8
Permanent Ineff=
       F       F
Bank Sta=512.4,548.2
XS Rating Curve= 0 ,0
Exp/Cntr(USF)=0,0
Exp/Cntr=0.3,0.1

Type RM Length L Ch R = 1 ,24572   ,829,831.2,823
XS GIS Cut Line= 3
 2207734.0210177723663.1646445062207802.63499998723434.100244645
2207855.72890817723077.752722027
#Sta/Elev= 30
       0 1611.58    18.8 1606.55    60.5 1593.75    81.4 1585.27   135.7 1556.82
   198.3    1530   219.2 1516.92   243.1 1499.91   248.1 1497.18   256.2 1494.96
   272.4 1493.55   296.7  1494.3   308.8 1493.42   320.9 1494.11     329 1493.36
  334.58 1491.88   341.2 1490.73   365.4  1490.5   377.31491.894   385.6 1495.03
   389.1 1495.21   405.9 1495.28   417.3 1493.87   454.4 1494.28   490.8 1493.57
     511 1496.09   527.2 1496.28   543.4 1502.56   567.6 1515.38   599.4 1530.74
#Mann= 4 ,-1,0
       0      .1       0  334.58    .045       0   377.3      .1       0
  589.12     .05       0
Bank Sta=334.58,377.3
XS Rating Curve= 0 ,0
Exp/Cntr(USF)=0,0
Exp/Cntr=0.3,0.1

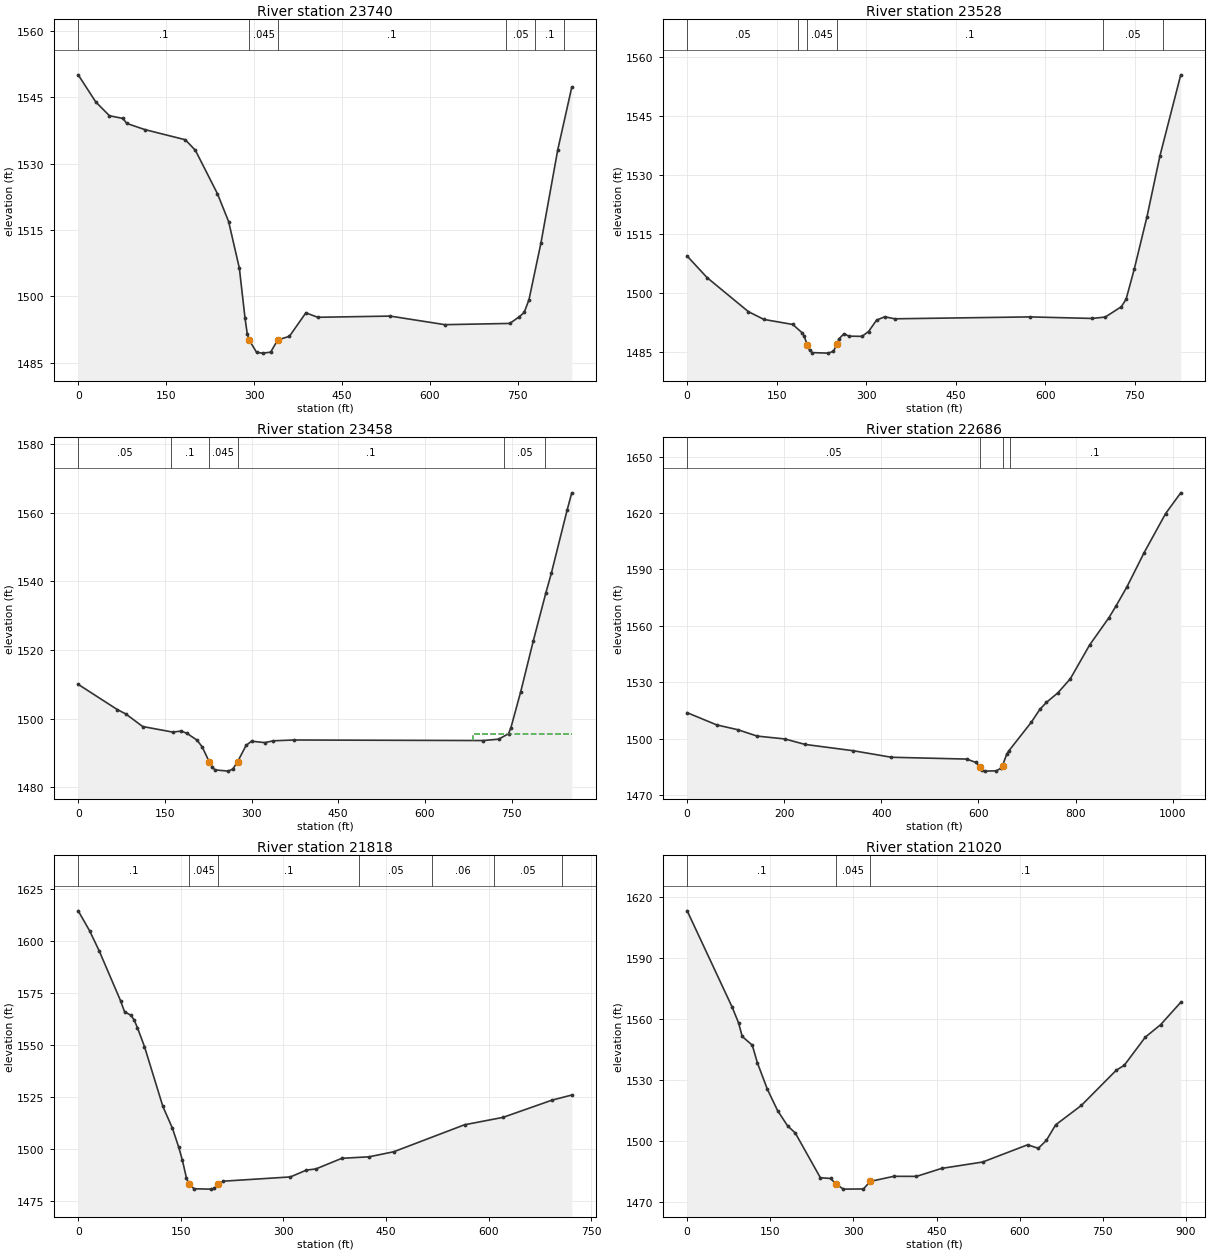
Type RM Length L Ch R = 1 ,23740   ,238.1,211.9,174.7
XS GIS Cut Line= 4
2208338.00175736723768.0468911382208576.03728293723630.529168298
2208581.38180984723506.2570717752208486.41476999723073.865756352
#Sta/Elev= 30
       0 1550.13      30 1543.98    53.3 1540.87    76.4 1540.26    82.7 1539.14
   113.4 1537.75   182.7 1535.44   199.9 1533.05   237.6 1523.21   256.6 1516.92
   274.9 1506.39   284.5 1495.15   288.3 1491.59   291.7 1490.12   304.3 1487.33
   314.7 1487.16   328.3 1487.38   340.3 1490.14   360.3 1490.97   388.4 1496.28
   408.6 1495.27   532.2 1495.54   625.6  1493.6   736.2 1493.88   752.6  1495.4
   760.8 1496.37     769 1499.25   789.5 1512.15   818.1 1533.18     842 1547.34
#Mann= 6 ,-1,0
       0      .1       0   291.7    .045       0   340.3      .1       0
  729.29     .05       0  779.29      .1       0  829.29     .07       0
Bank Sta=291.7,340.3
XS Rating Curve= 0 ,0
Exp/Cntr(USF)=0,0
Exp/Cntr=0.3,0.1

Type RM Length L Ch R = 1 ,23528   ,68.2,70.8,67.4
XS GIS Cut Line= 4
2208858.61592406723726.0227968592208879.49245853723612.174786776
2208682.68281922723511.1726746612208489.50581074723061.111346409
#Sta/Elev= 30
       0 1509.43    33.4 1503.95   102.5 1495.32   128.5 1493.34   176.9 1492.06
   192.4 1489.96   195.9 1489.12   201.11486.868   204.9 1485.55   209.6 1484.91
   236.3 1484.78     245 1485.26   250.61486.975   254.1 1488.38   262.5 1489.69
   271.2 1489.09   292.8 1489.04   303.8 1490.27   317.3 1493.17   330.8 1494.01
   347.8  1493.5   574.2 1493.98   678.7 1493.59   700.4 1493.95   727.2 1496.57
   735.2 1498.48     749 1506.21   770.1  1519.4   791.8 1534.85   826.7 1555.47
#Mann= 6 ,-1,0
       0     .05       0  185.75      .1       0   201.1    .045       0
   250.6      .1       0  696.96     .05       0  796.96     .07       0
Bank Sta=201.1,250.6
XS Rating Curve= 0 ,0
Exp/Cntr(USF)=0,0
Exp/Cntr=0.3,0.1

Type RM Length L Ch R = 1 ,23458   ,712.7,771.8,844.3
XS GIS Cut Line= 4
2208881.10794716723728.9726454892208922.61109191 723570.99743092
2208719.67416127723476.2364071712208557.32327117723038.505526268
#Sta/Elev= 30
       0 1509.95    67.8 1502.59    82.5 1501.32   111.5 1497.67   163.3 1496.05
   178.6 1496.34   188.1 1495.68   205.5 1493.72   214.6 1491.73   226.61487.443
   232.2  1485.8   236.7 1485.03   259.8 1484.67   267.6  1485.3     2761487.456
   290.5 1492.16     300 1493.39     323 1492.98   337.8 1493.51   373.5 1493.74
   700.5 1493.58   727.6 1493.98   744.7 1495.57   748.9 1497.34   765.9 1507.84
   787.6 1522.62   809.4 1536.63   818.8  1542.3     846 1560.63   854.2 1565.75
#Mann= 6 ,-1,0
       0     .05       0     160      .1       0   226.6    .045       0
     276      .1       0  737.31     .05       0  807.31     .07       0
#XS Ineff= 2 , 0
                          683.96         1495.57
Permanent Ineff=
       F       F
Bank Sta=226.6,276
XS Rating Curve= 0 ,0
Exp/Cntr(USF)=0,0
Exp/Cntr=0.3,0.1

Type RM Length L Ch R = 1 ,22686   ,864.5,868.3,856.3
XS GIS Cut Line= 4
2208905.47492966723796.104024885 2209108.6989693723627.131227874
2209544.83623574 723473.615769352209770.89443715723292.104761206
#Sta/Elev= 30
       0 1513.78    60.8 1507.28   104.7 1504.69     144 1501.33   201.2  1499.8
   242.8 1496.89   342.5 1493.52   420.6 1490.06   575.9 1489.09   594.8 1487.28
   602.31485.128   607.2  1483.2   613.6 1482.68   636.9 1482.85   645.4 1484.13
   649.51485.601   658.1 1491.69   662.4 1493.43     709 1508.77   726.5 1515.59
   740.1 1519.29   763.5 1524.33   789.1 1531.79   828.9  1549.8   868.8 1564.36
     883 1570.42   905.8 1580.73   941.3 1598.98   985.4 1619.71  1016.6 1630.76
#Mann= 4 ,-1,0
       0     .05       0   602.3    .045       0   649.5     .05       0
  664.29      .1       0
Bank Sta=602.3,649.5
XS Rating Curve= 0 ,0
Exp/Cntr(USF)=0,0
Exp/Cntr=0.3,0.1

Type RM Length L Ch R = 1 ,21818   ,794.9,797.5,792.3
XS GIS Cut Line= 3
2209141.96053887724347.8374162512209543.31660009724107.393692937
2209796.70729312724122.190229756
#Sta/Elev= 30
       0 1614.37    16.6 1604.81    30.6  1595.2    61.9  1571.2    67.7 1565.93
    77.2 1564.19    81.9 1561.89    86.5 1558.32    96.9 1549.18   123.8 1520.42
   137.7 1510.04   147.1 1500.73   152.3 1494.66   158.1 1486.31     162 1482.98
   169.8  1480.9   193.8 1480.74   198.9 1481.05   204.8 1482.98   212.4 1484.56
   310.3  1486.6   333.6 1489.87   347.6 1490.44   385.5 1495.54   425.5 1496.27
   461.4 1498.69   564.9 1511.65     621 1515.18   693.1  1523.5   721.7 1525.92
#Mann= 7 ,-1,0
       0      .1       0     162    .045       0   204.8      .1       0
     410     .05       0  517.87     .06       0  607.87     .05       0
  707.87      .1       0
Bank Sta=162,204.8
XS Rating Curve= 0 ,0
Exp/Cntr(USF)=0,0
Exp/Cntr=0.3,0.1

Type RM Length L Ch R = 1 ,21020   ,785.9,799.4,815.1
XS GIS Cut Line= 3
2209353.07578746725080.1318574872209891.96200495724785.571170806
2210154.55486517724698.801356125
#Sta/Elev= 30
       0 1612.98    81.2 1565.62    92.9 1557.77    99.3  1551.2   117.5 1546.95
   126.6 1538.33   144.8 1525.22   163.1  1514.8   181.3 1507.22     195 1503.81
   240.3  1481.8   258.8 1481.39   268.61478.674   281.9 1476.16   318.1 1476.25
   330.31479.945   372.8 1482.46   413.8 1482.43   459.4 1486.36   533.3 1489.49
   614.4 1497.96   633.6 1496.23   648.1 1500.08   664.9 1507.75   711.3  1517.3
   774.4 1534.62   788.8 1537.04   826.8 1550.89   854.5 1557.03   890.7    1568
#Mann= 3 ,-1,0
       0      .1       0   268.6    .045       0   330.3      .1       0
Bank Sta=268.6,330.3
XS Rating Curve= 0 ,0
Exp/Cntr(USF)=0,0
Exp/Cntr=0.3,0.1