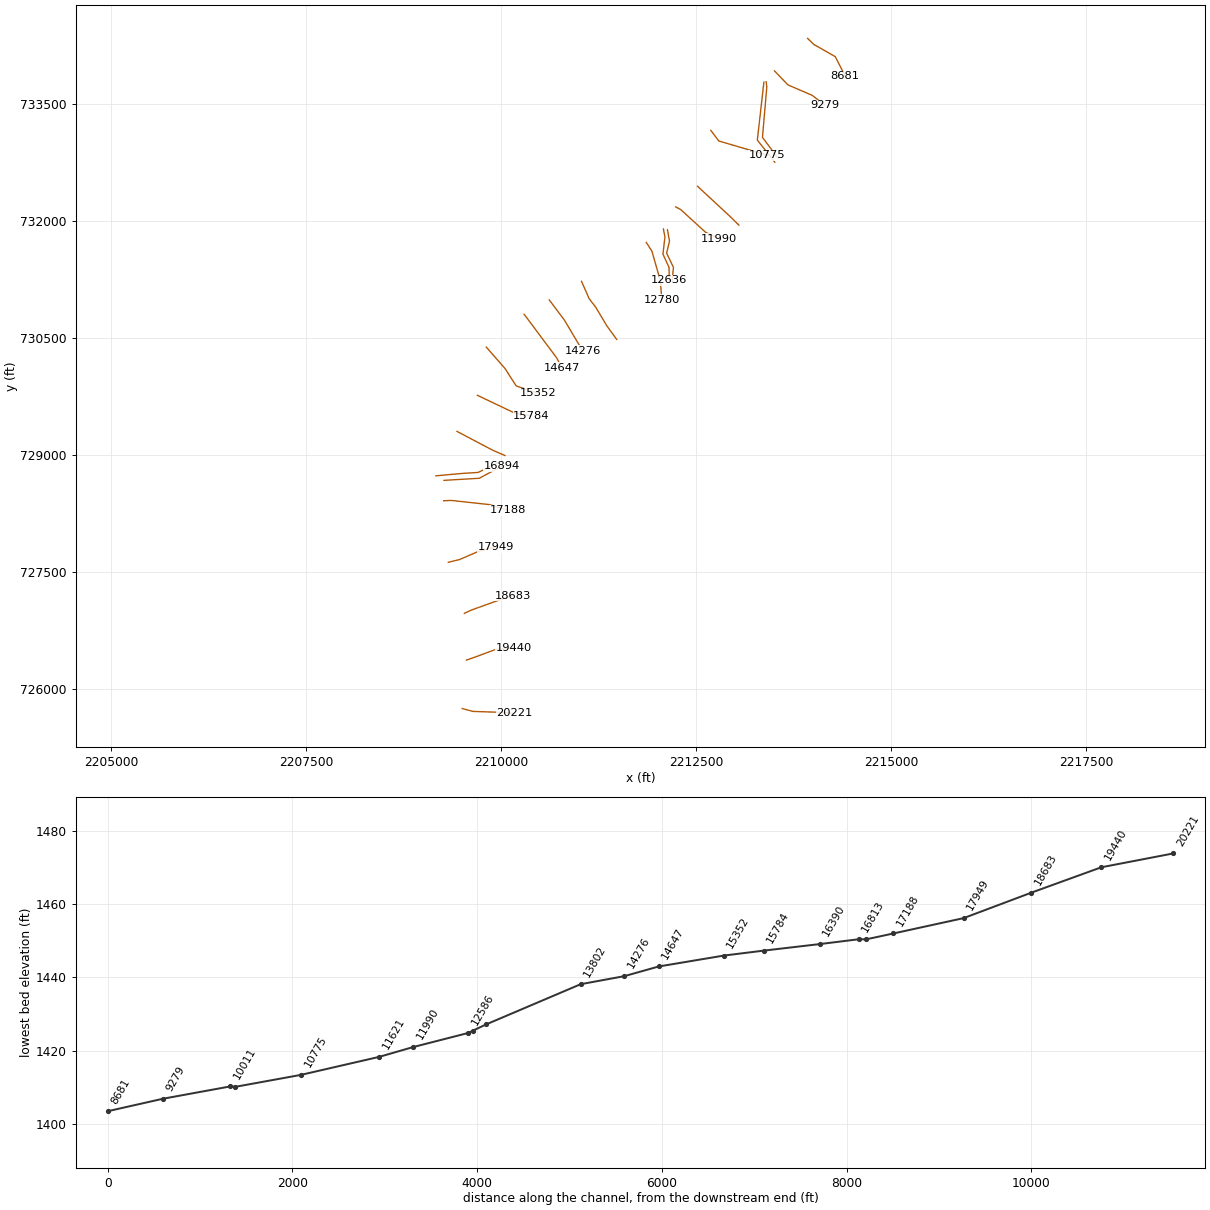
HEC-RAS study SANDRN1.prj: SANDRN1

--- SANDRN1.g01 (geometry) --- (continued)

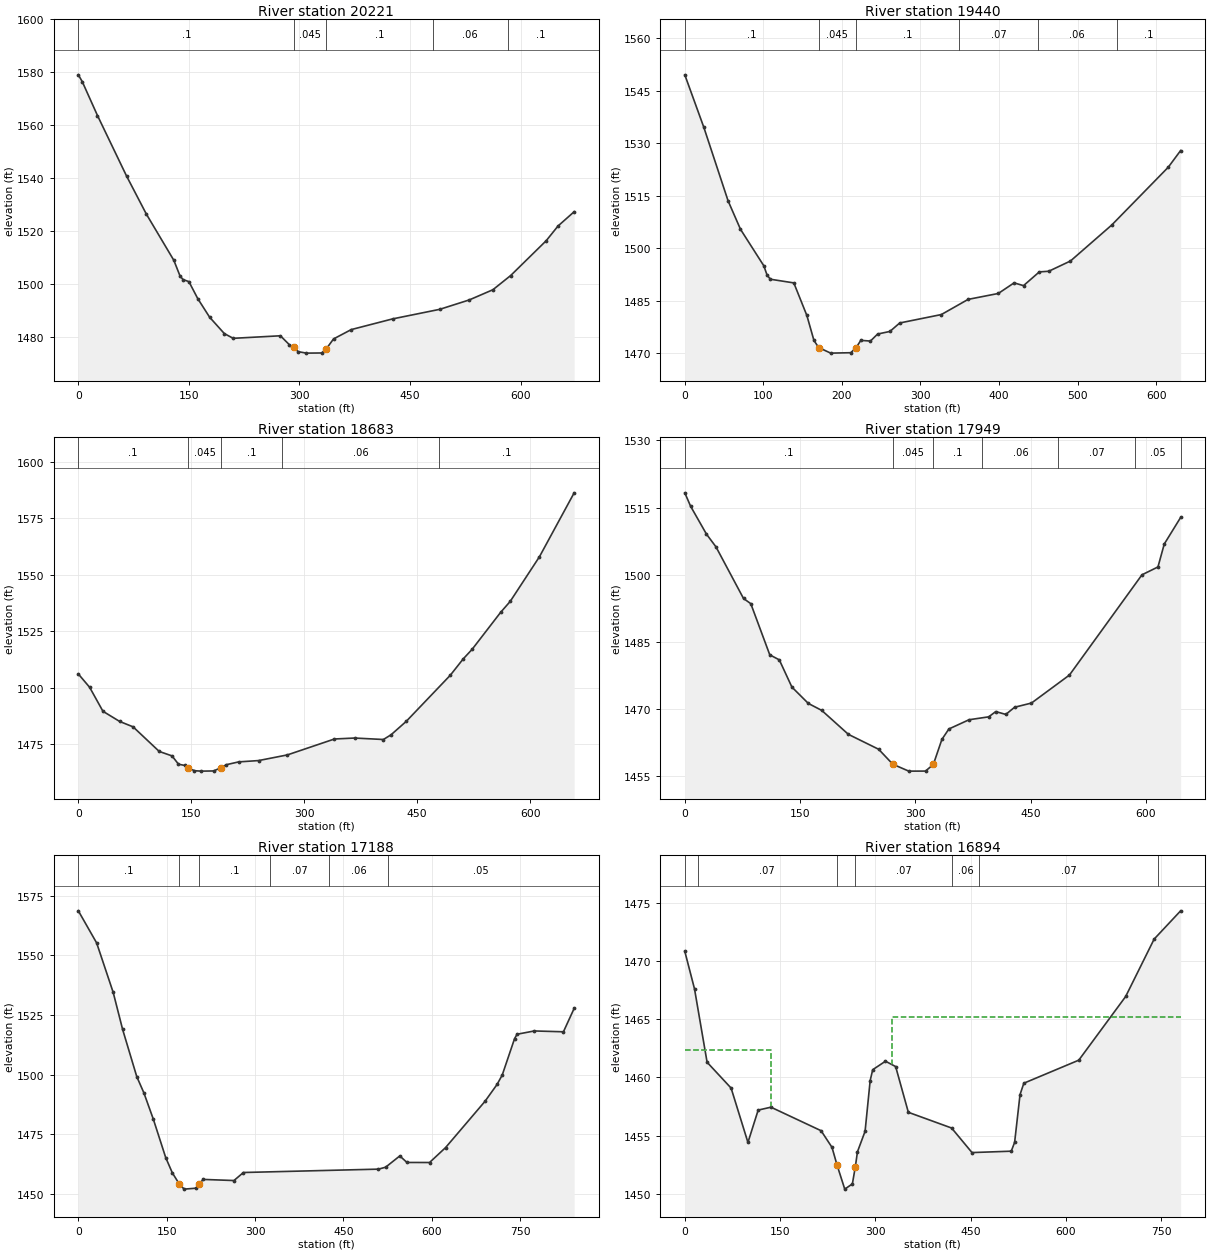
Type RM Length L Ch R = 1 ,20221   ,768.1,781,789.2
XS GIS Cut Line= 4
2209503.09560604725744.5613753792209638.73052688 725707.57003333
2210000.42364913725695.2395859812210170.08209745725682.226932812
#Sta/Elev= 30
       0 1579.06     5.3  1576.5      26 1563.65    65.5 1540.74    92.3 1526.38
   129.6 1508.89   137.9 1503.02     142 1501.64     150 1500.85     162 1494.43
   178.1 1487.39   198.1 1481.19   210.1 1479.41   274.1 1480.37   286.1 1477.04
   292.81475.964   298.1 1474.37   309.5 1473.81   330.1 1473.87   336.51475.485
   346.2 1479.18   370.2 1482.71   426.2 1486.75   490.2 1490.37   530.3 1493.93
   562.4 1497.79   586.5 1503.16   634.7 1516.33   650.7 1521.88   672.6 1527.29
#Mann= 5 ,-1,0
       0      .1       0   292.8    .045       0   336.5      .1       0
  480.59     .06       0  582.49      .1       0
Bank Sta=292.8,336.5
XS Rating Curve= 0 ,0
Exp/Cntr(USF)=0,0
Exp/Cntr=0.3,0.1

Type RM Length L Ch R = 1 ,19440   ,746.3,757.1,747.9
XS GIS Cut Line= 4
2209557.21334524 726365.93154687  2209679.284774726408.471590225
2209932.67546703726502.7995124482210163.70350369726518.102807256
#Sta/Elev= 30
       0 1549.61    24.3 1534.55    55.1 1513.58    70.9 1505.44   100.6    1495
   104.8 1492.31     109 1491.16   138.8 1490.11   155.4 1480.79   164.4 1473.66
   170.4 1471.63   185.7 1470.03   211.3 1470.15     218 1471.59   224.1 1473.68
   236.3 1473.48   245.5 1475.49   261.1 1476.23   273.6 1478.65   326.6 1481.06
   360.7  1485.4   399.1 1487.09   419.2 1490.12   431.2 1489.33   451.3 1493.26
   463.3 1493.44     491 1496.38   543.5 1506.66   615.5  1523.2   631.2 1527.96
#Mann= 6 ,-1,0
       0      .1       0   170.4    .045       0     218      .1       0
  349.27     .07       0  449.65     .06       0  549.65      .1       0
Bank Sta=170.4,218
XS Rating Curve= 0 ,0
Exp/Cntr(USF)=0,0
Exp/Cntr=0.3,0.1

Type RM Length L Ch R = 1 ,18683   ,727,733.3,734
XS GIS Cut Line= 4
2209530.69994525726965.1437244812209612.49406377727004.489686031
2209968.15955631727132.9364520122210147.93747867 727192.86242613
#Sta/Elev= 30
       0 1506.13      15 1500.24    32.7 1489.61    54.9 1485.11    72.7 1482.73
   107.4 1471.84   124.4 1469.86     133 1466.19   141.5 1465.62   145.7 1464.64
   154.2 1463.29   163.5 1463.12   179.7  1463.2  189.81 1464.71   196.7 1465.98
   212.9 1467.21   239.3 1467.79   277.6  1470.3   340.1 1477.35   366.9 1477.77
   405.1 1477.12   415.3 1479.22   435.3 1485.11   493.9 1505.56   511.1 1512.81
   522.9 1517.04   560.8 1533.43   573.5 1538.27   612.3 1558.03   658.4 1586.33
#Mann= 5 ,-1,0
       0      .1       0   145.7    .045       0  189.81      .1       0
  270.77     .06       0  478.91      .1       0
Bank Sta=145.7,189.81
XS Rating Curve= 0 ,0
Exp/Cntr(USF)=0,0
Exp/Cntr=0.3,0.1

Type RM Length L Ch R = 1 ,17949   ,771.9,761.6,745.2
XS GIS Cut Line= 4
2209324.75645376727620.2099764292209467.67990203727655.266671288
2209723.86344139727765.8300935362209936.90027938727817.066801407
#Sta/Elev= 30
       0 1518.31     7.6  1515.3    28.2 1509.09    40.6 1506.24    76.4 1494.73
    85.9 1493.56   110.6 1482.14     123 1481.02   139.4 1474.94   160.8 1471.29
   178.2 1469.74   212.9 1464.39   252.3 1461.06   270.7 1457.72   291.5 1456.18
   313.3 1456.19   323.51457.683   334.6 1463.26   343.7 1465.59   369.9 1467.65
   395.5  1468.3   404.7 1469.47   417.8 1468.84   429.2 1470.44   451.2 1471.38
   500.6 1477.63     595 1500.01   615.8 1501.76     624 1506.88   645.3 1512.81
#Mann= 7 ,-1,0
       0      .1       0   270.7    .045       0   323.5      .1       0
  387.16     .06       0  486.18     .07       0  586.18     .05       0
   645.3     .07       0
Bank Sta=270.7,323.5
XS Rating Curve= 0 ,0
Exp/Cntr(USF)=0,0
Exp/Cntr=0.3,0.1

Type RM Length L Ch R = 1 ,17188   ,288.5,293.8,294.6
XS GIS Cut Line= 4
2209265.06256568728409.8949531612209360.79430933728413.939956415
2209855.63304062728360.0065797082210092.93989812728287.196521155
#Sta/Elev= 30
       0 1568.66    31.1 1555.19    59.2 1534.45    75.2 1518.93    99.2 1499.16
   111.3 1492.34   127.4 1481.26   148.4 1465.18   159.6 1458.81   171.6 1454.05
   179.7 1451.99   199.8 1452.38   204.8 1453.99   211.9 1456.06   264.2 1455.59
   280.3 1458.96   509.6 1460.37   521.7 1461.18   545.8 1465.91   557.9 1463.17
   596.3 1463.15   623.4 1469.38   690.4 1488.79   710.9 1495.87   719.7 1499.83
   740.6 1515.05   744.8 1516.92   774.1  1518.3   823.6 1517.95   841.8 1527.77
#Mann= 6 ,-1,0
       0      .1       0   171.6    .045       0   204.8      .1       0
  325.82     .07       0  425.82     .06       0  525.82     .05       0
Bank Sta=171.6,204.8
XS Rating Curve= 0 ,0
Exp/Cntr(USF)=0,0
Exp/Cntr=0.3,0.1

Type RM Length L Ch R = 1 ,16894   ,80.1,81.3,86.9
XS GIS Cut Line= 4
2209268.85371159728671.4100814652209721.62773826728698.043847739
2209916.38715415728802.9143024462210009.60533611728852.852614211
#Sta/Elev= 30
       0 1470.83    15.3  1467.6    35.1  1461.3    72.9 1459.08    99.4 1454.41
   115.5 1457.19   135.6 1457.44   214.5 1455.42   231.7 1453.99   239.7 1452.46
   251.8  1450.4   263.8 1450.85  268.511452.343   271.8 1453.61   283.8 1455.37
   291.8 1459.73   295.8 1460.66   315.9 1461.39   331.9 1460.93   351.9    1457
     420 1455.65   452.1 1453.54   513.9 1453.66   519.2 1454.42   527.7 1458.52
   533.7  1459.5   620.2 1461.48     694 1466.95   738.8 1471.88   780.5 1474.31
#Mann= 7 ,-1,0
       0     .06       0      20     .07       0   239.7    .045       0
  268.51     .07       0     420     .06       0  463.56     .07       0
  744.76     .08       0
#XS Ineff= 2 , 0
          135.27 1462.39  325.93         1465.19
Permanent Ineff=
       F       F
Bank Sta=239.7,268.51
XS Rating Curve= 0 ,0
Exp/Cntr(USF)=0,0
Exp/Cntr=0.3,0.1

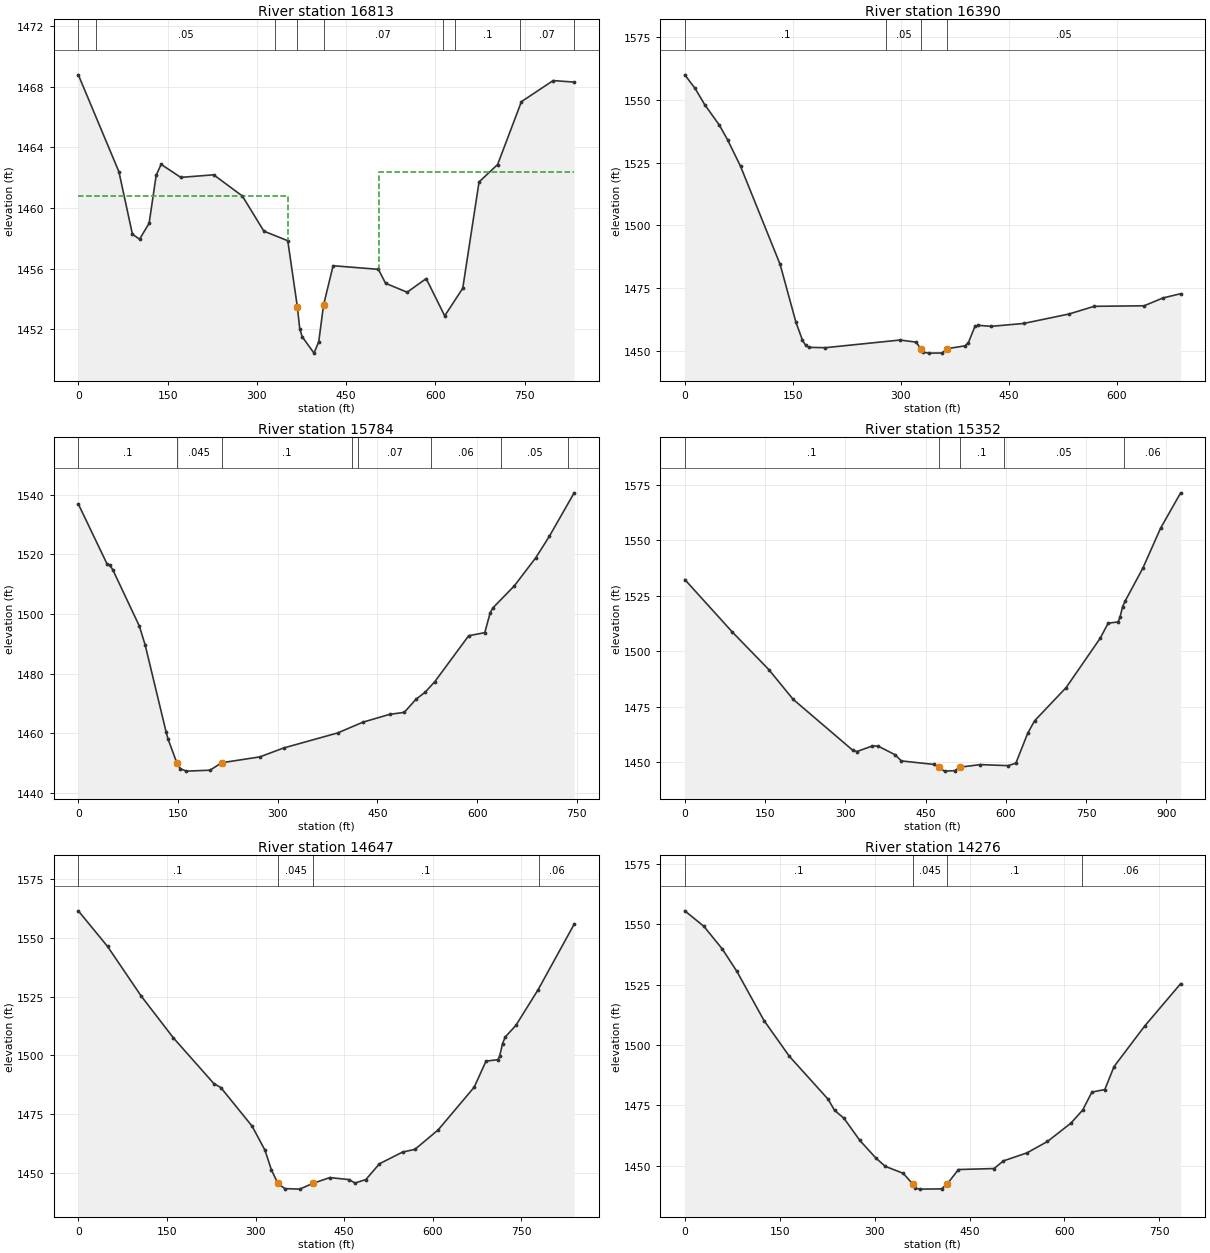
Type RM Length L Ch R = 1 ,16813   ,435.1,422.4,406.4
XS GIS Cut Line= 4
2209165.64786728 728729.671445192209496.90533532728759.634432249
2209706.64624473728772.951315387 2209967.9900763728899.461705191
#Sta/Elev= 30
       0 1468.79    68.2 1462.39    90.9 1458.27   102.9 1457.94     119    1459
   130.8 1462.16   139.1 1462.88   172.1 1462.02   227.5 1462.19   275.6 1460.79
   311.8 1458.47   351.9 1457.84     368 1453.48     372 1452.04     376 1451.51
     396 1450.42     404 1451.18     412 1453.59   428.1 1456.19   504.2 1455.95
   516.2 1455.03   552.5 1454.44   584.5 1455.34   615.6 1452.88   645.9  1454.7
   673.3 1461.72   704.5 1462.87   744.5 1467.02   797.8 1468.41   833.1 1468.31
#Mann= 9 ,-1,0
       0     .07       0      30     .05       0     330     .07       0
     368    .045       0     412     .07       0  612.77     .08       0
  632.77      .1       0  742.77     .07       0  832.77     .06       0
#XS Ineff= 2 , 0
          351.85 1460.76   504.8         1462.38
Permanent Ineff=
       F       F
Bank Sta=368,412
XS Rating Curve= 0 ,0
Exp/Cntr(USF)=0,0
Exp/Cntr=0.3,0.1

Type RM Length L Ch R = 1 ,16390   ,599.5,606,589
XS GIS Cut Line= 3
2209435.56278171729299.5157397352209900.33365548729054.388542605
2210050.80777649728990.072990883
#Sta/Elev= 30
       0 1560.01    14.3  1554.6    27.8 1548.07    47.9 1540.02    59.5  1534.1
    77.6 1523.48   132.5 1484.44   154.4 1461.46   163.5 1454.27     168 1452.18
   172.5 1451.41   195.1 1451.26   299.2 1454.32   321.8 1453.47   327.9 1450.72
   330.8  1449.5   339.4  1449.1   357.5 1449.15   365.1 1450.89   389.6 1452.02
   394.1 1453.27   403.2 1459.72   407.7 1460.19   425.8 1459.77     471 1460.93
     534 1464.69   568.9 1467.75   638.4 1467.97   664.5 1471.08   689.1 1472.78
#Mann= 4 ,-1,0
       0      .1       0     280     .05       0   327.9    .045       0
   365.1     .05       0
Bank Sta=327.9,365.1
XS Rating Curve= 0 ,0
Exp/Cntr(USF)=0,0
Exp/Cntr=0.3,0.1

Type RM Length L Ch R = 1 ,15784   ,443.8,432,409.7
XS GIS Cut Line= 4
2209697.38069272729762.3388354652209788.71733976729718.953928124
  2210181.464922729531.713801707  2210389.255794729502.029391422
#Sta/Elev= 30
       0 1536.84    42.9 1516.89    47.4 1516.31    51.8 1514.84    91.7 1495.99
   100.5 1489.66     132 1460.52     135 1458.09  148.331450.026   153.7 1448.11
   162.6 1447.32   198.2 1447.63   215.7 1450.13   273.1 1452.09   308.8 1455.07
   390.1 1460.11   428.4 1463.74   468.3 1466.34   490.5 1467.02   508.2 1471.43
   521.5  1473.7   536.2 1477.24   587.4  1492.7   611.6 1493.73   619.8 1500.45
   623.8 1502.02   656.1 1509.43   688.5 1518.88   708.7    1526   746.1 1540.59
#Mann= 8 ,-1,0
       0      .1       0  148.33    .045       0   215.7      .1       0
  411.12     .05       0  421.12     .07       0  531.12     .06       0
  636.21     .05       0  736.21     .06       0
Bank Sta=148.33,215.7
XS Rating Curve= 0 ,0
Exp/Cntr(USF)=0,0
Exp/Cntr=0.3,0.1

Type RM Length L Ch R = 1 ,15352   ,705.6,704.9,703.6
XS GIS Cut Line= 4
 2209810.5823063730381.3261168072210051.82018972730105.333623064
2210194.92740869729882.4952392272210475.00868012 729788.45335247
#Sta/Elev= 30
       0 1532.31    89.1 1508.58   157.1 1491.71   202.5 1478.33   313.6 1455.45
   321.6  1454.8   350.8 1457.33   361.5 1457.23     393 1453.36   404.8 1450.57
   466.6 1448.97  474.321447.695   485.5 1445.97   504.6 1446.19   514.1 1447.74
   552.1 1448.91   604.4 1448.44   618.8 1449.54   641.1 1463.12   653.8 1468.64
   712.9 1483.65   776.2 1505.76   791.4 1512.65   809.9  1513.2   813.5 1515.33
   818.4 1520.15   822.9 1522.53   856.3  1537.5   889.3 1555.42   926.8 1571.38
#Mann= 5 ,-1,0
       0      .1       0  474.32    .045       0   514.1      .1       0
  596.56     .05       0   821.4     .06       0
Bank Sta=474.32,514.1
XS Rating Curve= 0 ,0
Exp/Cntr(USF)=0,0
Exp/Cntr=0.3,0.1

Type RM Length L Ch R = 1 ,14647   ,375.3,371.3,367.7
XS GIS Cut Line= 3
2210296.38124572730802.5901591712210714.01566288730241.877284281
2210779.75441373730118.133753271
#Sta/Elev= 30
       0 1561.54    49.5 1546.36   106.6 1525.17   160.9 1507.43   229.5 1487.93
   241.2 1486.27   294.3 1469.77     316 1459.54   326.7 1451.26   337.71445.467
   349.6 1443.22   374.6    1443  397.351445.481   425.7 1447.92   458.2 1447.06
   468.4 1445.59   486.8  1447.1   509.7  1453.8   548.8 1458.78   569.7 1459.93
     609  1468.2   670.1 1486.43   690.1 1497.53   710.1 1498.12   713.1 1499.57
   718.1 1505.01   722.6 1507.78   740.7 1512.76   778.2 1527.91   839.3 1555.85
#Mann= 4 ,-1,0
       0      .1       0   337.7    .045       0  397.35      .1       0
  779.15     .06       0
Bank Sta=337.7,397.35
XS Rating Curve= 0 ,0
Exp/Cntr(USF)=0,0
Exp/Cntr=0.3,0.1

Type RM Length L Ch R = 1 ,14276   ,478.1,473.6,470.2
XS GIS Cut Line= 3
 2210618.1158991  730986.46521422210814.37722798730724.783442354
2211047.43755603730332.260784586
#Sta/Elev= 30
       0 1555.48    30.1 1549.09    59.5 1539.61    82.4 1530.39   125.2  1510.1
   165.2 1495.33   226.6 1477.52   236.6 1472.99   251.6 1469.67   276.6 1460.52
   301.6 1453.33   316.7 1449.81   345.2 1446.91  360.741442.339   363.9 1440.79
   371.9 1440.37   405.7 1440.47     415 1442.62   432.5 1448.48   488.7 1448.88
   503.4 1452.04   540.6 1455.35   573.2 1460.08   610.4  1467.7   628.8 1473.07
   643.4 1480.51   663.8 1481.56   678.4 1491.07   726.7 1507.79   783.6 1525.34
#Mann= 4 ,-1,0
       0      .1       0  360.74    .045       0     415      .1       0
   627.1     .06       0
Bank Sta=360.74,415
XS Rating Curve= 0 ,0
Exp/Cntr(USF)=0,0
Exp/Cntr=0.3,0.1

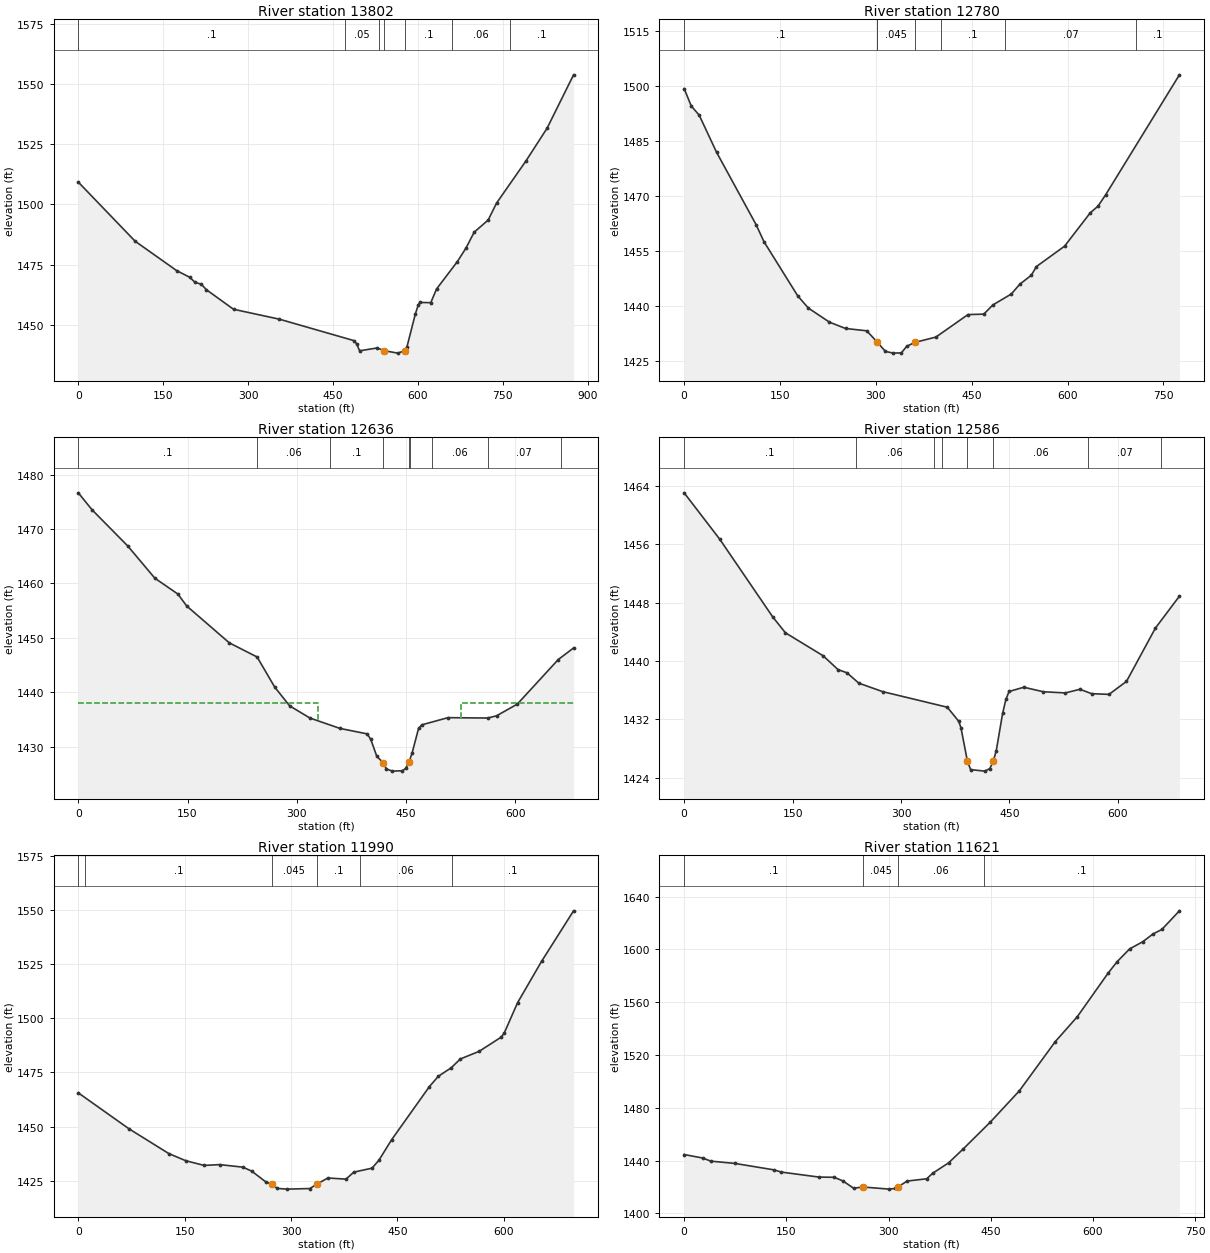
Type RM Length L Ch R = 1 ,13802   ,1031.6,1022.2,1007
XS GIS Cut Line= 5
2211032.52838003731224.6351768882211129.62838202 731002.24484975
 2211214.1993515730892.6158152462211358.28322542730651.431939337
2211483.57355057730479.157742259
#Sta/Elev= 30
       0 1509.27   100.3 1484.72     174 1472.44   196.8 1469.72   205.9 1467.69
   217.6 1466.75   226.4 1464.52   274.3  1456.4   355.2 1452.29   487.6 1443.33
   492.3 1441.83     497 1439.13     528 1440.32     541 1439.17   564.4 1438.17
   577.6 1439.23   580.8 1440.85   595.6 1454.51   600.9 1458.33   604.1 1459.24
   622.8 1459.15     633 1464.83   669.8 1476.24   685.1 1481.89   699.5 1488.46
   724.2  1493.5     739 1500.54   790.7 1517.98   828.3 1531.67   875.1 1553.88
#Mann= 7 ,-1,0
       0      .1       0  471.12     .05       0  531.12      .1       0
     541    .045       0   577.6      .1       0  661.12     .06       0
  762.07      .1       0
Bank Sta=541,577.6
XS Rating Curve= 0 ,0
Exp/Cntr(USF)=0,0
Exp/Cntr=0.3,0.1

Type RM Length L Ch R = 1 ,12780   ,139.1,143.9,148.3
XS GIS Cut Line= 4
2211862.16184257731723.8044551282211934.08945211731612.830428983
 2212043.0084037 731232.641635712212061.50407472730986.032688722
#Sta/Elev= 30
       0 1499.32    11.1  1494.6    23.6 1492.07    50.8 1481.95   112.8 1462.18
   124.8 1457.64   177.7 1442.85   194.3 1439.52   227.4 1435.67   252.5 1433.95
   285.8 1433.31   302.5 1430.16     315 1427.69   327.4 1427.23   339.9  1427.3
   348.3 1429.09   360.7 1430.13     394 1431.61   444.1 1437.73   468.9 1437.86
     483 1440.35   512.1 1443.36   525.2 1446.01   543.2 1448.44   551.3 1450.83
   595.3 1456.38   635.5 1465.47   647.5 1467.26   659.6 1470.39     775 1503.08
#Mann= 7 ,-1,0
       0      .1       0  302.25     .06       0   302.5    .045       0
   360.7     .06       0  402.25      .1       0  502.25     .07       0
  707.73      .1       0
Bank Sta=302.5,360.7
XS Rating Curve= 0 ,0
Exp/Cntr(USF)=0,0
Exp/Cntr=0.3,0.1

Type RM Length L Ch R = 1 ,12636   ,50.2,50.5,50.3
XS GIS Cut Line= 5
2212082.04527435731895.7604110912212102.02059906731792.554566776
 2212075.9472361731573.2715739482212154.05538156 731404.40786564
  2212156.952742731236.574695793
#Sta/Elev= 30
       0 1476.64    18.9 1473.52    67.8 1466.89   105.1 1460.96   136.7 1458.05
   148.8 1455.86   207.4 1449.08   245.5 1446.49   269.6 1440.97   290.1 1437.52
     318 1435.28   359.3 1433.37   396.6 1432.37   401.5 1431.36   409.8 1428.24
   418.6 1427.08     423 1425.92   431.3 1425.53     445 1425.61   449.5 1426.03
   453.9 1427.17   458.3 1428.88   467.1 1433.36   471.5 1434.03   507.5 1435.35
     562 1435.28   574.2 1435.69   602.7 1437.84   658.8 1446.01   679.9 1448.15
#Mann= 9 ,-1,0
       0      .1       0  245.12     .06       0  345.95      .1       0
   418.6    .045       0   453.9      .1       0  455.95     .07       0
  485.95     .06       0     562     .07       0     662     .05       0
#XS Ineff= 2 , 0
          328.57 1438.01  525.34         1438.04
Permanent Ineff=
       F       F
Bank Sta=418.6,453.9
XS Rating Curve= 0 ,0
Exp/Cntr(USF)=0,0
Exp/Cntr=0.3,0.1

Type RM Length L Ch R = 1 ,12586   ,586.3,596.2,600.8
XS GIS Cut Line= 5
2212133.64819651731885.7727487372212160.28196279731740.951644619
 2212123.2423924731586.3588083212212210.80523407731403.273340411
2212193.57417063731228.251643832
#Sta/Elev= 30
       0 1463.04    49.4 1456.66   122.6 1446.02   140.1 1443.85   192.3  1440.7
   212.8 1438.81   225.2 1438.37   241.6 1436.95   274.5 1435.79     364 1433.65
   379.8 1431.72   382.8 1430.86   391.7 1426.31   396.2  1425.1   415.8 1424.89
   422.8 1425.24   427.8 1426.32   431.7  1427.7   440.5 1432.81     445 1434.71
   449.4 1435.81   469.8 1436.39   496.8 1435.77   527.3 1435.61   547.4 1436.11
   563.5 1435.51   587.6 1435.41   611.8 1437.19   651.9 1444.51     685 1448.87
#Mann= 8 ,-1,0
       0      .1       0  237.25     .06       0  346.22      .1       0
  356.22     .06       0   391.7    .045       0   427.8     .06       0
  559.17     .07       0  659.17     .05       0
Bank Sta=391.7,427.8
XS Rating Curve= 0 ,0
Exp/Cntr(USF)=0,0
Exp/Cntr=0.3,0.1

Type RM Length L Ch R = 1 ,11990   ,366.9,369.1,367.3
XS GIS Cut Line= 4
2212238.32597245732180.3729499592212306.14343288 732143.38160791
2212622.62491484731853.6160951992212797.30625229731773.468187428
#Sta/Elev= 30
       0 1465.57    71.5 1448.95   127.9 1437.45   151.6 1434.19   177.6 1432.01
   199.3 1432.39   231.9 1431.22   244.5  1429.4   264.1 1424.47   272.8 1423.24
   280.7 1421.39   293.8 1421.05   326.6 1421.32  336.391423.346     352  1426.2
   377.5 1425.67   388.5  1428.9   414.3 1430.75   424.1 1434.46   441.8 1443.85
   495.1 1468.44   507.8 1473.25   525.7 1477.11   538.9 1481.26   565.2 1484.75
   596.1 1491.27   600.5 1493.06   619.5 1507.25   653.3 1526.35   698.5 1549.76
#Mann= 6 ,-1,0
       0     .06       0      10      .1       0   272.8    .045       0
  336.39      .1       0  397.25     .06       0  526.35      .1       0
Bank Sta=272.8,336.39
XS Rating Curve= 0 ,0
Exp/Cntr(USF)=0,0
Exp/Cntr=0.3,0.1

Type RM Length L Ch R = 1 ,11621   ,819.2,845.5,848.5
XS GIS Cut Line= 3
2212519.59085061732443.8770555652212932.88917844732060.263138028
 2213049.3434034731946.092329237
#Sta/Elev= 30
       0 1444.58    27.5 1441.89    39.1 1439.57    74.5 1437.84   131.8 1432.96
   142.7 1431.27     198 1427.49   220.3 1427.34   233.3 1424.53   248.6 1419.09
   262.7 1419.97     301 1418.37   309.7 1418.85   313.7 1420.02   327.4 1424.49
   356.1  1426.2   364.6 1430.31   388.3 1438.32   409.9 1448.93   449.5 1469.17
     492 1492.78   544.9 1530.17   576.9 1548.82   622.1  1581.8   635.7 1590.71
     654 1600.34   673.1 1605.71   688.3 1611.65   701.3 1615.07     727 1629.16
#Mann= 4 ,-1,0
       0      .1       0   262.7    .045       0   313.7     .06       0
     440      .1       0
Bank Sta=262.7,313.7
XS Rating Curve= 0 ,0
Exp/Cntr(USF)=0,0
Exp/Cntr=0.3,0.1

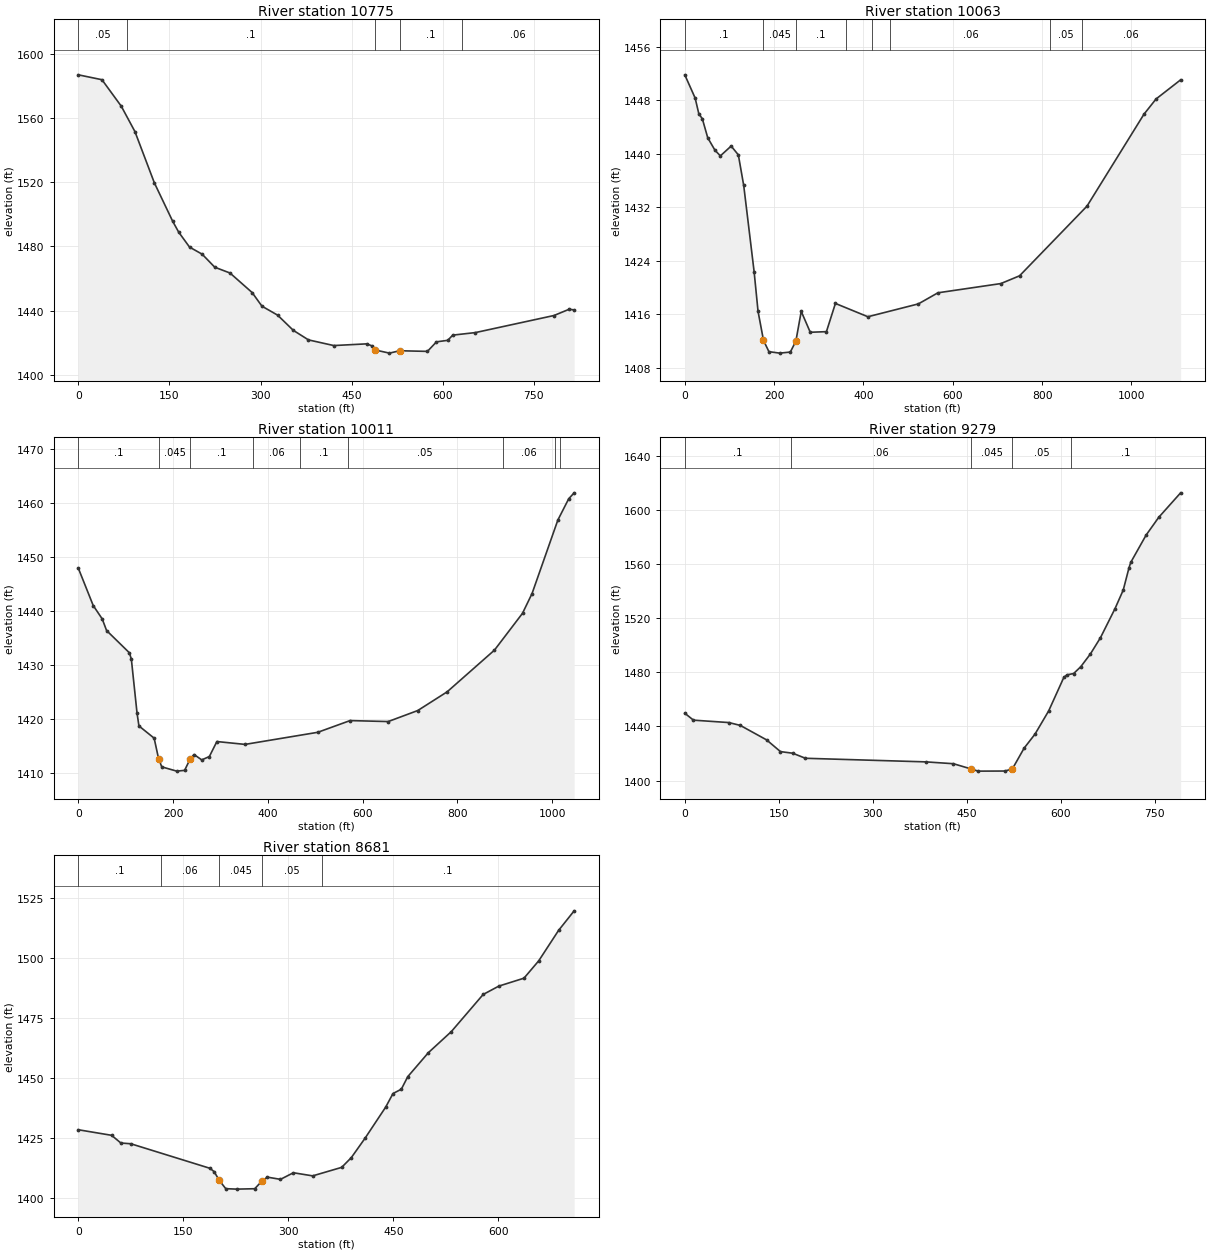
Type RM Length L Ch R = 1 ,10775   ,762.7,712.1,660.2
XS GIS Cut Line= 3
2212689.56016817733161.0702776712212792.76601248733024.572225513
2213412.00107837732843.129692767
#Sta/Elev= 30
       0 1586.93    38.9 1583.88    70.7 1567.38    93.2 1551.55   125.2 1519.58
   155.3 1495.69   165.3 1488.84   183.1 1479.56   203.9 1475.13   224.7    1467
   249.7 1463.41   286.2 1451.22   302.3 1442.74   328.1 1437.15   353.9 1427.69
   378.9 1421.72   420.6 1418.19   474.8 1419.25   483.1 1418.05   489.11415.398
   512.3 1413.47   529.11414.951   574.8 1414.56   589.7  1420.5   608.2 1421.45
   616.5 1424.69   653.7 1426.27   783.2 1436.92   808.2 1440.82   816.4  1440.4
#Mann= 5 ,-1,0
       0     .05       0      80      .1       0   489.1    .045       0
   529.1      .1       0  631.12     .06       0
Bank Sta=489.1,529.1
XS Rating Curve= 0 ,0
Exp/Cntr(USF)=0,0
Exp/Cntr=0.3,0.1

Type RM Length L Ch R = 1 ,10063   ,49.1,52.4,54.3
XS GIS Cut Line= 3
 2213370.5089959733780.2721256832213286.25093901733036.335135604
2213510.25406586732752.734846568
#Sta/Elev= 30
       0 1451.82    23.2 1448.34    31.3 1446.02    39.3 1445.24    51.4  1442.4
    67.5 1440.55    79.6  1439.7   103.8 1441.17   119.9 1439.85   131.9 1435.28
   155.2 1422.39     164 1416.45   176.2 1412.12   188.3 1410.43   212.4 1410.21
   236.3 1410.37   248.7 1412.01   260.7 1416.45   280.9 1413.33   317.1 1413.42
   337.2 1417.64   409.9 1415.65   522.9 1417.57   566.7 1419.23   707.6 1420.61
   749.5 1421.77   900.5 1432.19    1028 1445.93  1055.1 1448.21  1110.1 1451.07
#Mann= 8 ,-1,0
       0      .1       0   176.2    .045       0   248.7      .1       0
     360     .06       0     420     .07       0     460     .06       0
  818.69     .05       0  888.69     .06       0
Bank Sta=176.2,248.7
XS Rating Curve= 0 ,0
Exp/Cntr(USF)=0,0
Exp/Cntr=0.3,0.1

Type RM Length L Ch R = 1 ,10011   ,653.5,731.7,756.1
XS GIS Cut Line= 4
2213399.28003971  733784.38227482213407.50033795733716.564814378
2213352.01332487733071.2714030932213549.30048247732806.166785082
#Sta/Elev= 30
       0 1447.91    31.4    1441    50.4 1438.52    59.6 1436.37   107.8 1432.24
   111.9 1431.07   123.9 1421.07   127.9  1418.7     160 1416.43   169.4 1412.62
   176.1 1411.12   207.6 1410.33   224.3 1410.47   236.3 1412.64   244.3  1413.4
   260.4 1412.41   276.5 1413.03   292.4 1415.81   351.8 1415.28   505.3 1417.52
   573.5 1419.69   653.9 1419.51   716.3 1421.55   778.4 1425.02   878.2 1432.74
   937.4 1439.56   957.5 1443.21    1012 1456.83  1034.9 1460.77  1046.4 1461.87
#Mann= 9 ,-1,0
       0      .1       0   169.4    .045       0   236.3      .1       0
  368.31     .06       0  468.31      .1       0  568.31     .05       0
  895.99     .06       0 1005.99     .05       0 1015.99      .1       0
Bank Sta=169.4,236.3
XS Rating Curve= 0 ,0
Exp/Cntr(USF)=0,0
Exp/Cntr=0.3,0.1

Type RM Length L Ch R = 1 ,9279    ,600.7,597.7,593.2
XS GIS Cut Line= 4
2213506.87077902733923.4263127282213678.56599639733744.345762788
2213989.76392976733610.1938193792214151.78249839 733485.23017495
#Sta/Elev= 30
       0 1449.73    13.8  1444.6    70.4 1442.82    88.6 1440.72   130.6 1430.03
   152.7 1421.38   172.3 1420.18   192.6 1416.45   384.9 1413.79   428.9 1412.43
  457.161408.553   468.3 1406.96   511.2 1407.03     5231408.616   541.7 1423.91
   559.1 1434.28   580.9  1451.4   605.2 1476.23   610.2 1478.05   620.8 1479.03
   632.2 1484.07   647.6 1493.51   663.6 1505.47   686.9 1527.01     700  1540.7
   709.2 1557.15     712 1561.12   736.5 1581.27   756.7  1594.4   791.6 1612.47
#Mann= 5 ,-1,0
       0      .1       0     170     .06       0  457.16    .045       0
     523     .05       0  616.97      .1       0
Bank Sta=457.16,523
XS Rating Curve= 0 ,0
Exp/Cntr(USF)=0,0
Exp/Cntr=0.3,0.1

Type RM Length L Ch R = 1 ,8681    ,1203.5,1190.4,1169.4
XS GIS Cut Line= 4
2213930.59766998734341.5302371432214006.71154251734265.416364616
2214285.34100459734106.9914717752214412.26144006733857.303359777
#Sta/Elev= 30
       0 1428.33    47.5 1426.01    60.8 1422.79    74.9 1422.49   188.1 1412.24
     194 1410.85   201.4 1407.19   210.6 1403.75   226.2 1403.56     252 1403.73
  262.891407.119   270.2 1408.55   288.8 1407.64   307.2 1410.39   334.8 1409.09
   376.2 1412.64     390 1416.72   409.6  1424.8   439.2 1437.84   449.5 1443.44
   461.4 1445.24   470.6 1450.47     500 1460.47   532.8 1469.26   578.3 1484.76
   600.7 1488.25   636.6 1491.55   657.7  1498.8     686 1511.47   708.3 1519.65
#Mann= 5 ,-1,0
       0      .1       0  117.64     .06       0   201.4    .045       0
  262.89     .05       0  347.64      .1       0
Bank Sta=201.4,262.89
XS Rating Curve= 0 ,0
Exp/Cntr(USF)=0,0
Exp/Cntr=0.3,0.1