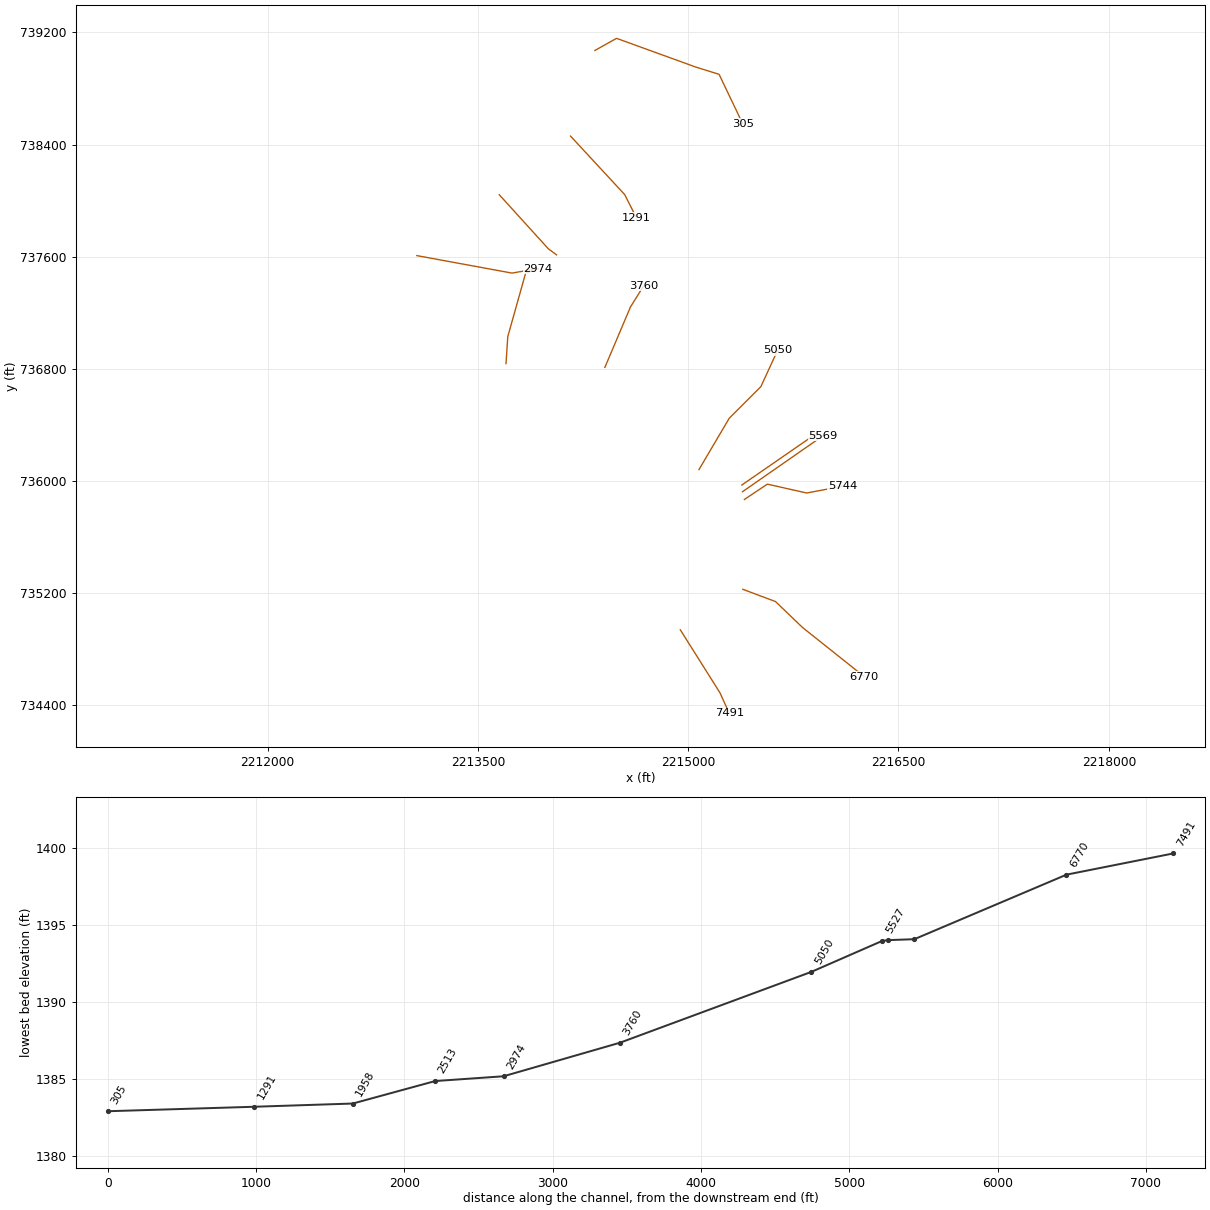
HEC-RAS study SANDRN1.prj: SANDRN1

--- SANDRN1.g01 (geometry) --- (continued)

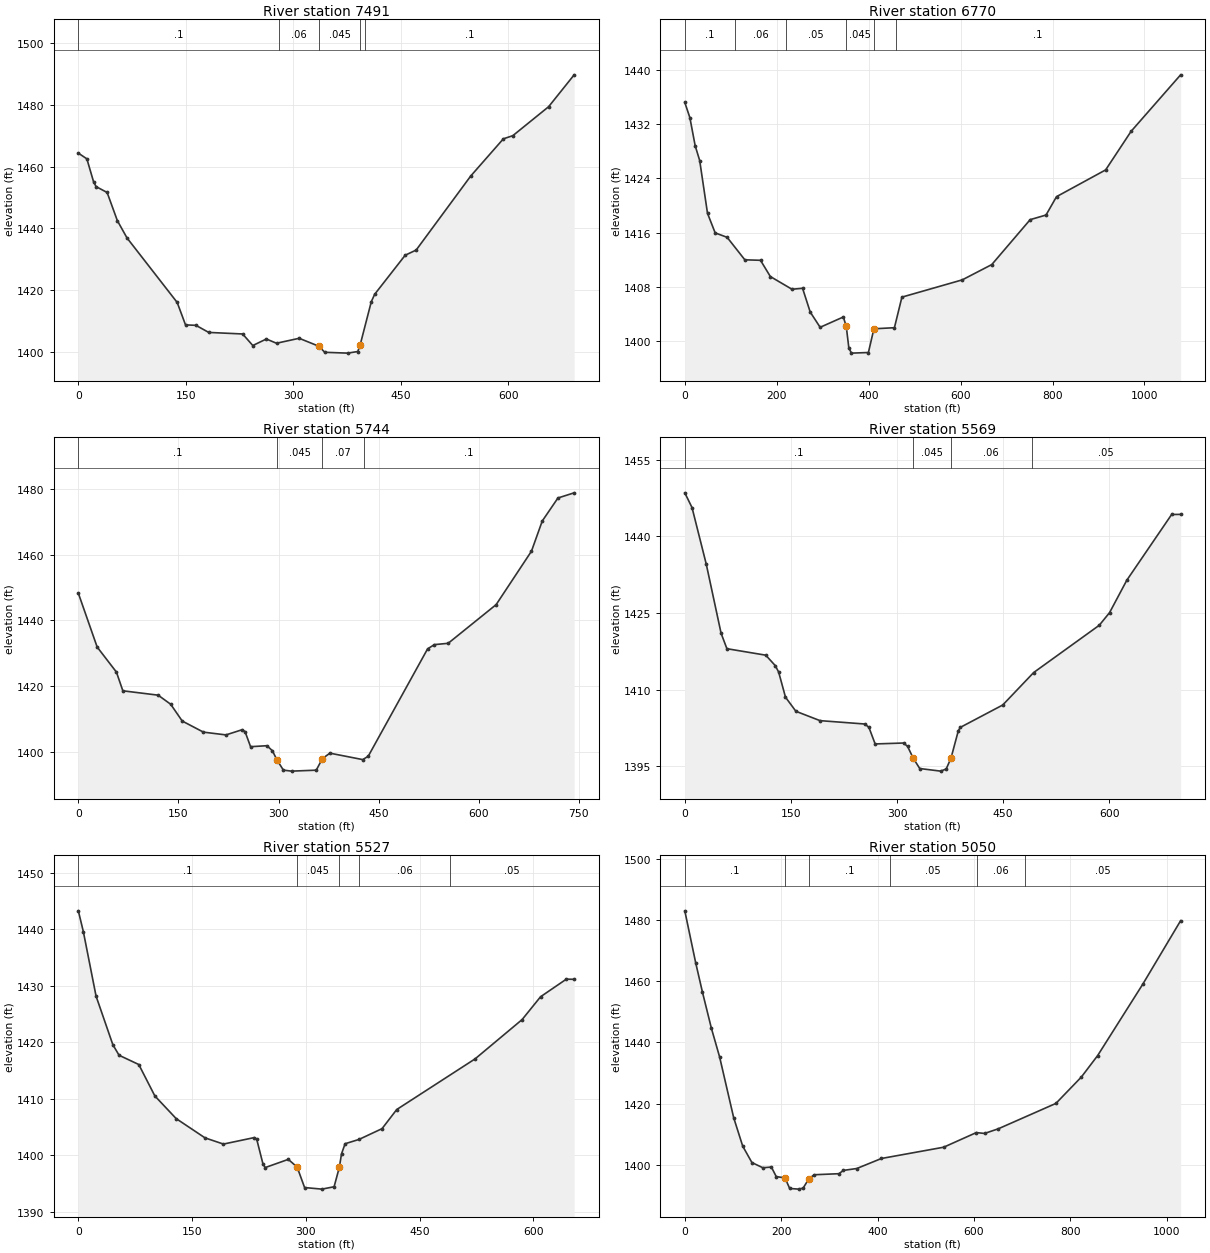
Type RM Length L Ch R = 1 ,7491    ,710.4,721.1,727.4
XS GIS Cut Line= 3
2214943.97911777 734939.232468242215227.12272357734489.399481604
2215293.34179266734343.260846352
#Sta/Elev= 30
       0 1464.39    11.9 1462.54    21.3 1455.09    24.8 1453.55    40.2 1451.65
    54.4 1442.57    67.9 1436.95     138 1416.05   149.6  1408.8   164.1 1408.66
     182 1406.36   229.3 1405.86   243.5 1402.12   262.4 1404.23   276.6 1402.86
   308.2 1404.46   335.71401.892   343.9 1399.93   375.8 1399.66     390 1400.18
   393.3 1402.29   408.9 1416.32   413.6 1418.71   456.2 1431.35   471.5 1433.02
   547.6 1456.97   593.2 1469.02   606.4 1470.04   656.4 1479.42     692 1489.73
#Mann= 5 ,-1,0
       0      .1       0     280     .06       0   335.7    .045       0
   393.3     .06       0     400      .1       0
Bank Sta=335.7,393.3
XS Rating Curve= 0 ,0
Exp/Cntr(USF)=0,0
Exp/Cntr=0.3,0.1

Type RM Length L Ch R = 1 ,6770    ,994.9,1025.8,1027.1
XS GIS Cut Line= 4
2215389.86193123735227.9569487532215622.68883702735140.922793719
2215815.93556487 734955.538654852216255.80534257734605.332332853
#Sta/Elev= 30
       0 1435.16      11 1432.94    22.6 1428.79    32.4 1426.62    49.4 1418.85
    66.1 1415.97    92.1 1415.32   130.6 1412.01   164.7 1411.94   186.1 1409.55
   233.1 1407.68   256.2 1407.82   272.8 1404.33   294.4 1402.08   344.9  1403.6
  351.23 1402.21   356.9 1399.02   362.6 1398.28   399.4 1398.37   411.4 1401.86
     456 1402.02   472.3 1406.52   603.6 1409.06   667.8 1411.31   751.3 1417.92
   785.8  1418.6   808.6  1421.3   915.5 1425.24   970.8 1430.91  1078.6 1439.23
#Mann= 6 ,-1,0
       0      .1       0     110     .06       0     220     .05       0
  351.23    .045       0   411.4     .05       0  458.56      .1       0
Bank Sta=351.23,411.4
XS Rating Curve= 0 ,0
Exp/Cntr(USF)=0,0
Exp/Cntr=0.3,0.1

Type RM Length L Ch R = 1 ,5744    ,155,174.8,212
XS GIS Cut Line= 4
2215400.68915046735868.6884533542215564.88820137735978.126749834
2215845.15798953735914.9916598632216099.08694086735962.533559939
#Sta/Elev= 30
       0 1448.27    28.2 1431.88    57.1 1424.24    66.7 1418.55   119.6 1417.22
   138.4 1414.45   155.7 1409.34   187.5 1405.96   221.2 1405.12   245.8 1406.72
   249.9 1406.08   258.1 1401.53   282.7 1401.83   290.9 1400.28   297.41397.578
   307.3 1394.39   319.6 1394.09   356.5 1394.38   365.81397.919     377 1399.56
   426.2  1397.6   434.4 1398.62   523.4 1431.33   533.6 1432.61   554.2 1433.01
   626.1 1444.79     679 1461.05   695.2 1470.25   718.7 1477.26     743 1478.83
#Mann= 4 ,-1,0
       0      .1       0   297.4    .045       0   365.8     .07       0
  427.33      .1       0
Bank Sta=297.4,365.8
XS Rating Curve= 0 ,0
Exp/Cntr(USF)=0,0
Exp/Cntr=0.3,0.1

Type RM Length L Ch R = 1 ,5569    ,42.4,41.6,41.8
XS GIS Cut Line= 2
2215387.30162526735923.8731306612215962.59097679736323.879007899
#Sta/Elev= 30
       0 1448.49    10.2 1445.61    30.3 1434.55    51.3    1421    59.5 1417.99
   114.4 1416.72   127.7  1414.7   132.6 1413.43   142.3  1408.5     157 1405.74
   191.1 1403.91   254.5 1403.25   260.2 1402.59     269 1399.35   309.1 1399.53
   314.8 1398.88   322.6 1396.62     332 1394.54   361.6 1394.03   369.4 1394.45
   376.2 1396.58   386.6 1401.96   389.5  1402.6   449.3 1406.97     493 1413.32
   585.7 1422.57   600.3 1425.05   624.7  1431.4     688 1444.25   700.7 1444.27
#Mann= 4 ,-1,0
       0      .1       0   322.6    .045       0   376.2     .06       0
     490     .05       0
Bank Sta=322.6,376.2
XS Rating Curve= 0 ,0
Exp/Cntr(USF)=0,0
Exp/Cntr=0.3,0.1

Type RM Length L Ch R = 1 ,5527    ,467.4,477.4,497.4
XS GIS Cut Line= 2
2215382.76757932735971.8535078382215920.60319703736343.394547369
#Sta/Elev= 30
       0 1443.27     6.6 1439.59    23.4 1428.15    45.5 1419.56    53.7 1417.69
    79.7 1416.05   100.9 1410.48     129 1406.47     167 1403.06   191.3 1401.96
     232 1403.11   235.1 1402.86   243.5  1398.4   246.4  1397.8   276.8 1399.25
   288.5 1397.88   298.3 1394.26   321.1 1393.98   337.2  1394.4   344.1 1397.84
     347 1400.23   351.7 1402.02     370 1402.78   400.4 1404.69   419.8 1408.08
   523.1 1417.05   585.1 1424.01   609.4 1428.05   643.4 1431.17   653.7 1431.14
#Mann= 5 ,-1,0
       0      .1       0   288.5    .045       0   344.1      .1       0
     370     .06       0     490     .05       0
Bank Sta=288.5,344.1
XS Rating Curve= 0 ,0
Exp/Cntr(USF)=0,0
Exp/Cntr=0.3,0.1

Type RM Length L Ch R = 1 ,5050    ,1276.5,1290.5,1285.9
XS GIS Cut Line= 4
2215076.86130373736081.6723061512215293.17322238736448.270976449
2215518.43690679736673.3522349512215637.63123117736932.291629289
#Sta/Elev= 30
       0 1483.08    22.6 1466.07    36.6 1456.48    55.2 1444.64    72.2 1435.28
   101.4 1415.39   120.2 1406.05   139.3 1400.67     162 1398.97   179.7  1399.2
   189.8 1396.08     2081395.647   217.7 1392.19   236.3 1391.97   245.6  1392.3
   257.81395.437   268.8 1396.68   319.9 1397.02   329.2  1398.1     357 1398.72
   408.1    1402   537.3 1405.69   605.2 1410.48   622.2  1410.2   650.4  1411.7
   770.3 1420.03   823.2 1428.68   856.9 1435.68   950.9 1459.13  1029.2 1479.85
#Mann= 6 ,-1,0
       0      .1       0     208    .045       0   257.8      .1       0
  425.66     .05       0  605.66     .06       0  705.66     .05       0
Bank Sta=208,257.8
XS Rating Curve= 0 ,0
Exp/Cntr(USF)=0,0
Exp/Cntr=0.3,0.1

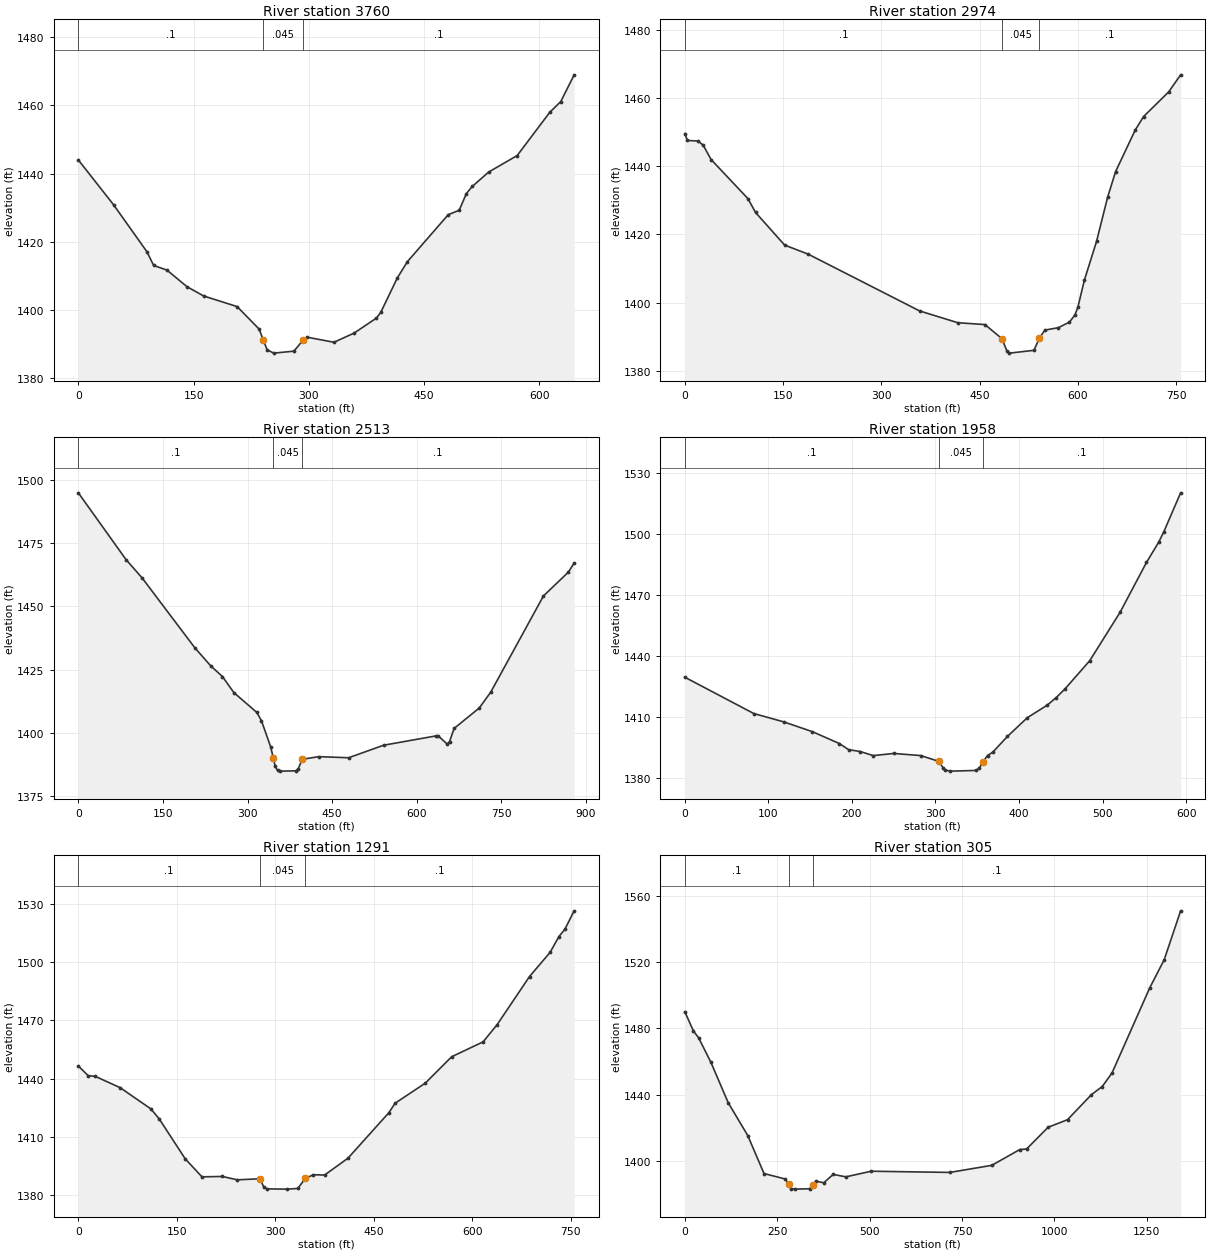
Type RM Length L Ch R = 1 ,3760    ,778.8,785.2,787.4
XS GIS Cut Line= 3
2214406.06790641736810.9071186232214588.74120048737242.219062943
2214682.61497659737391.909678914
#Sta/Elev= 30
       0 1443.99    45.9 1430.84    89.3 1417.07      98 1413.07   115.4 1411.69
   141.5 1406.82   163.2 1404.11   206.6 1401.01   235.3  1394.4   240.61391.224
   245.7 1388.31   254.4 1387.37   280.5 1387.95   292.6 1391.22   297.9 1392.03
   332.6 1390.55   358.7 1393.23   387.8 1397.63   393.4 1399.28   415.1 1409.44
   428.2  1414.2   481.3 1427.95   495.5 1429.24   504.9 1434.15   512.5 1436.22
     534 1440.46     571 1445.29   613.5 1457.99   627.7 1461.11   645.1 1468.94
#Mann= 3 ,-1,0
       0      .1       0   240.6    .045       0   292.6      .1       0
Bank Sta=240.6,292.6
XS Rating Curve= 0 ,0
Exp/Cntr(USF)=0,0
Exp/Cntr=0.3,0.1

Type RM Length L Ch R = 1 ,2974    ,504.5,461,414.6
XS GIS Cut Line= 4
2213700.82924711736837.1227871992213713.51489253737029.944597601
2213840.37134675737481.5535745952213929.17086469 737514.53625269
#Sta/Elev= 30
       0 1449.54     4.1 1447.56    20.1 1447.39    28.1 1446.18    40.1 1441.97
    96.3 1430.53     108 1426.45   152.4 1416.88   188.5 1414.21   358.6 1397.56
   416.8 1394.11   458.4 1393.56   484.1 1389.45   491.6 1385.95   495.7 1385.19
   533.1 1386.01   541.4 1389.56   549.8 1391.94   570.5 1392.66   587.3 1394.29
   595.5 1396.31   600.2 1398.63   610.1 1406.56   628.7 1417.94   645.6 1430.89
   657.8 1438.43   687.7 1450.58   700.5 1454.57   738.9 1461.81   757.1 1466.81
#Mann= 3 ,-1,0
       0      .1       0   484.1    .045       0   541.4      .1       0
Bank Sta=484.1,541.4
XS Rating Curve= 0 ,0
Exp/Cntr(USF)=0,0
Exp/Cntr=0.3,0.1

Type RM Length L Ch R = 1 ,2513    ,573.6,555.4,534.6
XS GIS Cut Line= 3
2213064.89682224737607.9426693982213743.26194336737483.337145955
2213929.77357835737515.618005858
#Sta/Elev= 30
       0 1494.81    84.7  1468.4   113.1 1461.19   206.7 1433.55   235.1 1426.37
   255.5 1422.23   275.8 1415.89   316.5 1408.05   324.6 1404.81   340.9 1394.53
  345.691390.048     349 1386.72   353.1 1385.15   357.2 1384.88   385.6 1384.99
   389.7  1385.7   396.9 1389.56   426.3  1390.6   479.2 1390.16   541.2 1395.11
   633.9 1398.79   637.8 1398.84     654 1395.55   658.1 1396.56   666.2 1401.75
   710.9 1409.84   731.2 1416.11   824.6 1454.09   868.6 1463.46     879 1467.06
#Mann= 3 ,-1,0
       0      .1       0  345.69    .045       0   396.9      .1       0
Bank Sta=345.69,396.9
XS Rating Curve= 0 ,0
Exp/Cntr(USF)=0,0
Exp/Cntr=0.3,0.1

Type RM Length L Ch R = 1 ,1958    ,665.1,667,667
XS GIS Cut Line= 3
2213652.62379451738042.2591022122214002.74760814737656.615481408
2214061.10157707737613.484286976
#Sta/Elev= 30
       0 1429.59    82.6 1411.73   118.3 1407.65   152.7 1402.82   185.1 1396.96
     196 1393.98     210 1393.06   225.5 1391.05     250 1392.11   282.4 1391.06
     304 1388.22   309.4 1384.87   311.9 1383.95   317.6 1383.42   348.7 1383.75
   352.6 1384.95   357.2 1388.12   362.3  1391.1   368.6 1392.73   386.1 1400.47
   409.9 1409.68   433.7 1415.83   444.5 1419.59   455.3 1423.97   484.7 1437.76
   520.9 1461.47   552.5    1486   567.3 1496.08     573 1500.83   593.4 1520.24
#Mann= 3 ,-1,0
       0      .1       0     304    .045       0   357.2      .1       0
Bank Sta=304,357.2
XS Rating Curve= 0 ,0
Exp/Cntr(USF)=0,0
Exp/Cntr=0.3,0.1

Type RM Length L Ch R = 1 ,1291    ,963.7,985.9,997.2
XS GIS Cut Line= 3
 2214161.0948459738460.1669616382214547.44886284738042.986826317
2214631.70691973  737876.5257871
#Sta/Elev= 30
       0 1446.53      15 1441.55    25.9 1441.18    63.7 1435.37   110.5 1424.46
   123.2 1419.32   162.8  1398.8   188.3 1389.53   219.4 1389.72   242.1 1387.99
   276.7 1388.54   282.1 1384.49   287.1 1383.33   318.5 1383.21   334.2 1383.54
     346  1388.8   358.1 1390.61   375.1 1390.45   410.7 1399.12   472.9 1422.47
   482.6  1427.4   528.5 1437.71   568.6 1451.26   616.5 1458.93   637.9 1467.78
   687.2 1492.52   718.6 1504.95     732 1513.08     741 1516.76   755.2 1526.29
#Mann= 3 ,-1,0
       0      .1       0   276.7    .045       0     346      .1       0
Bank Sta=276.7,346
XS Rating Curve= 0 ,0
Exp/Cntr(USF)=0,0
Exp/Cntr=0.3,0.1

Type RM Length L Ch R = 1 ,305     ,,,
XS GIS Cut Line= 5
2214334.63244556739070.9237032642214489.44121203739157.483443657
2215053.74413497 738952.736365422215220.20517419738901.133443263
 2215388.3308238738549.900650515
#Sta/Elev= 30
       0 1490.12    23.4 1478.44    37.4 1474.32    70.4 1459.64   117.4 1435.13
   170.3 1415.29   214.3 1392.33   272.1 1389.02  280.791385.823   286.7 1383.26
   299.4 1382.92   337.7 1383.14   346.2 1385.65   354.7 1387.71     376 1386.77
   401.4 1391.81   435.6 1390.34   504.5 1393.74   716.8 1393.01   830.5 1397.29
   905.8 1406.79   924.8  1407.2   982.9 1420.31  1035.3 1424.86  1100.1 1440.01
  1129.3 1444.91  1155.7 1453.09  1257.9 1504.58  1296.8 1521.44  1341.3 1551.04
#Mann= 3 ,-1,0
       0      .1       0  280.79    .045       0   346.2      .1       0
Bank Sta=280.79,346.2
XS Rating Curve= 0 ,0
Exp/Cntr(USF)=0,0
Exp/Cntr=0.3,0.1
LCMann Table=0

Chan Stop Cuts=-1
Use User Specified Reach Order=0
Composite Channel Slope=5